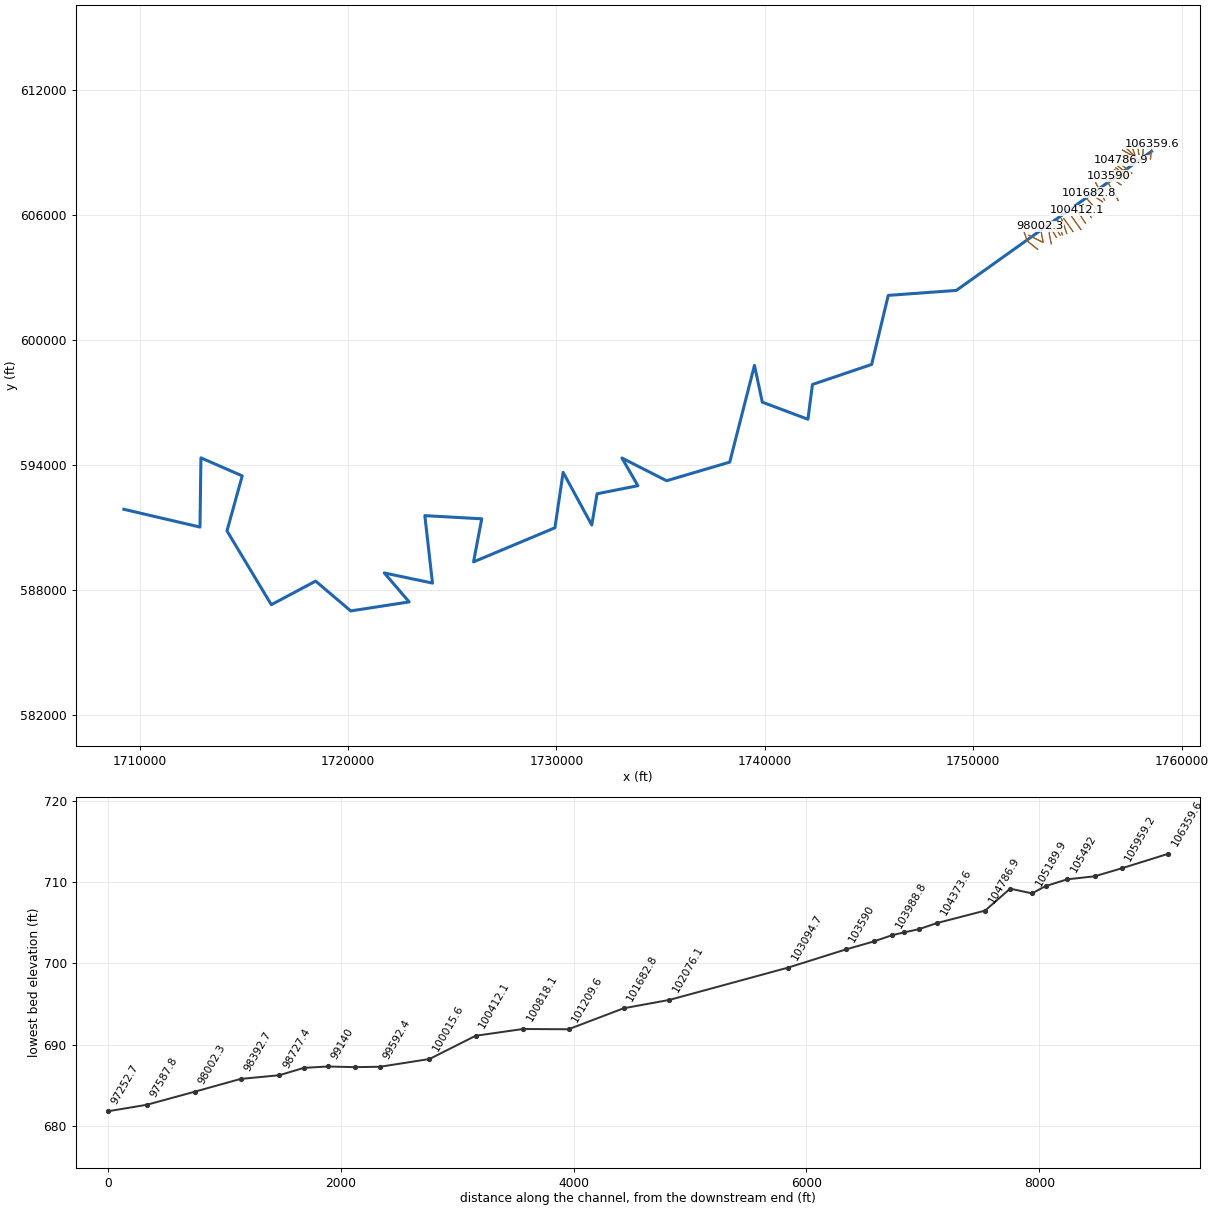
--- EightenmC1.prj (project) ---

Proj Title=EightenmC1
Current Plan=p01
Default Exp/Contr=0,0
English Units
Geom File=g01
Flow File=f01
Plan File=p01
BEGIN DESCRIPTION:
AMEC Environment & Infrastructure, 2013
Projection: NAD 1983 State Plane West Virginia South FIPS 4702 (US Feet)
Vertical Datum: NAVD 1988
END DESCRIPTION:
DSS Export Rating Curves= 0
DSS Export Rating Curve Sorted= 0
DSS Export Volume Flow Curves= 0
DXF OffsetX= 0
DXF OffsetY= 0
DXF ScaleX= 0
DXF ScaleY= 0

--- EightenmC1.p01 (plan) ---

Plan Title=Floodplain
Program Version=4.00
Geom File=g01
Flow File=f01
K Sum by GR=0
Std Step Tol=0.01
Critical Tol=0.01
Num of Std Step Trials=20
Max Error Tol=0.3
Flow Tol Ratio=0.001
Split Flow NTrial=30
Split Flow Tol=0.02
Split Flow Ratio=0.02
Log Output Level=0
Friction Slope Method=1
Unsteady Friction Slope Method=2
Unsteady Bridges Friction Slope Method=1
Global Log Level=0
CheckData=False
Run HTab=0
Run UNet=0
Run PostProcess=0
UNET Theta=0
UNET Theta Warmup=0
UNET ZTol=0
UNET ZSATol=0
UNET MxIter=0
UNET MaxInSteps=0
UNET DtIC=0
UNET DtMin=0
UNET MaxCRTS=0
UNET WFStab=0
UNET SFStab=0
UNET WFX=0
UNET SFX=0
UNET DSS MLevel=0
UNET DZMax Abort=0
UNET Convert EG Bridges=0
UNET Use Existing IB Tables=0
UNET Froude Limit=0
UNET Froude Power=0
Write IC File=0
Echo Input=False
Echo Output=False
Write Detailed=0

--- EightenmC1.f01 (steady flow) ---

Flow Title=USGS Regress. Eqn. (2010) - Western-Plateaus
Program Version=4.10
Number of Profiles= 1
Profile Names=P100yr
River Rch & RM=EightenmC1,Main            ,106359.6
    1388
River Rch & RM=EightenmC1,Main            ,105305.6
    1588
River Rch & RM=EightenmC1,Main            ,103094.7
    1628
River Rch & RM=EightenmC1,Main            ,102076.1
    1788
River Rch & RM=EightenmC1,Main            ,101682.8
    1912
River Rch & RM=EightenmC1,Main            ,100412.1
    1946
River Rch & RM=EightenmC1,Main            ,98936.4
    1999
River Rch & RM=EightenmC1,Main            ,96375.6
    2258
River Rch & RM=EightenmC1,Main            ,94565.5
    2322
River Rch & RM=EightenmC1,Main            ,92899.9
    2339
River Rch & RM=EightenmC1,Main            ,91223.5
    2378
River Rch & RM=EightenmC1,Main            ,90424.8
    2428
River Rch & RM=EightenmC1,Main            ,88682.5
    2604
River Rch & RM=EightenmC1,Main            ,88103.3
    2612
River Rch & RM=EightenmC1,Main            ,86132.9
    2635
River Rch & RM=EightenmC1,Main            ,85533.4
    2639
River Rch & RM=EightenmC1,Main            ,84591.9
    2671
River Rch & RM=EightenmC1,Main            ,81631.3
    2861
River Rch & RM=EightenmC1,Main            ,81174.1
    3939
River Rch & RM=EightenmC1,Main            ,79297.6
    3978
River Rch & RM=EightenmC1,Main            ,77183.7
    3997
River Rch & RM=EightenmC1,Main            ,74206.4
    4047
River Rch & RM=EightenmC1,Main            ,69955
    4181
River Rch & RM=EightenmC1,Main            ,68814.9
    4188
River Rch & RM=EightenmC1,Main            ,67371.3
    4195
River Rch & RM=EightenmC1,Main            ,65982.3
    4234
River Rch & RM=EightenmC1,Main            ,63138.6
    4278
River Rch & RM=EightenmC1,Main            ,62132.5
    4285
River Rch & RM=EightenmC1,Main            ,60963.6
    6091
River Rch & RM=EightenmC1,Main            ,59035.5
    6289
River Rch & RM=EightenmC1,Main            ,56413.6
    6301
River Rch & RM=EightenmC1,Main            ,54544.9
    6314
River Rch & RM=EightenmC1,Main            ,51556.5
    6347
River Rch & RM=EightenmC1,Main            ,48799.5
    6403
River Rch & RM=EightenmC1,Main            ,46436.8
    6425
River Rch & RM=EightenmC1,Main            ,45472.2
    6727
River Rch & RM=EightenmC1,Main            ,44301.9
    6731
River Rch & RM=EightenmC1,Main            ,43092
    6743
River Rch & RM=EightenmC1,Main            ,41620
    7634
River Rch & RM=EightenmC1,Main            ,41143.9
    7636
River Rch & RM=EightenmC1,Main            ,40293.7
    7639
River Rch & RM=EightenmC1,Main            ,37988.7
    7646
River Rch & RM=EightenmC1,Main            ,35917.6
    7725
River Rch & RM=EightenmC1,Main            ,34410.6
    7777
River Rch & RM=EightenmC1,Main            ,31415.5
    7794
River Rch & RM=EightenmC1,Main            ,27137.4
    7872
River Rch & RM=EightenmC1,Main            ,24017.9
    7934
River Rch & RM=EightenmC1,Main            ,21565.8
    7962
River Rch & RM=EightenmC1,Main            ,21050.2
    8304
River Rch & RM=EightenmC1,Main            ,19753.6
    8309
River Rch & RM=EightenmC1,Main            ,18410.6
    8321
River Rch & RM=EightenmC1,Main            ,15454.3
    8435
River Rch & RM=EightenmC1,Main            ,13390.4
    8451
River Rch & RM=EightenmC1,Main            ,12291.9
    8457
River Rch & RM=EightenmC1,Main            ,10223.6
    8466
River Rch & RM=EightenmC1,Main            ,9629.6
    8927
River Rch & RM=EightenmC1,Main            ,7416
    8940
River Rch & RM=EightenmC1,Main            ,1983.3
    8997
River Rch & RM=EightenmC1,Main            ,420.8
    9262
River Rch & RM=EightenmC1,Main            ,0
    9265
Boundary for River Rch & Prof#=EightenmC1,Main            , 1
Up Type= 0
Dn Type= 1
Dn Known WS=579.88
DSS Import GetInterval= 0
DSS Import GetPeak= 0
DSS Import FillOption= 0

--- EightenmC1.g01 (geometry) ---

Geom Title=USGS 3m DEM
Program Version=4.10

River Reach=EightenmC1      ,Main
Reach XY= 30
     1758558.943        609032.9     1749190.709      602360.497
     1745924.867      602122.287     1745127.963      598806.726
     1742287.107      597847.015     1742069.008      596176.008
     1739879.338      596997.406     1739503.904      598763.899
     1738316.838      594119.801     1735287.324      593225.704
      1733142.36      594315.771     1733907.985      592987.646
     1731949.651      592599.625     1731694.443      591099.625
     1730319.443      593628.271     1729926.214      590966.813
     1726020.718       589331.61     1726413.891      591398.447
     1723682.988      591550.791     1724049.307      588312.944
     1721735.071      588800.791     1722931.252      587410.166
     1720125.696      586977.874     1718441.668       588408.43
     1716314.412      587275.531     1714186.373      590821.538
     1714919.012       593458.69     1712936.035      594324.038
     1712890.896      591002.857     1709238.506      591854.759

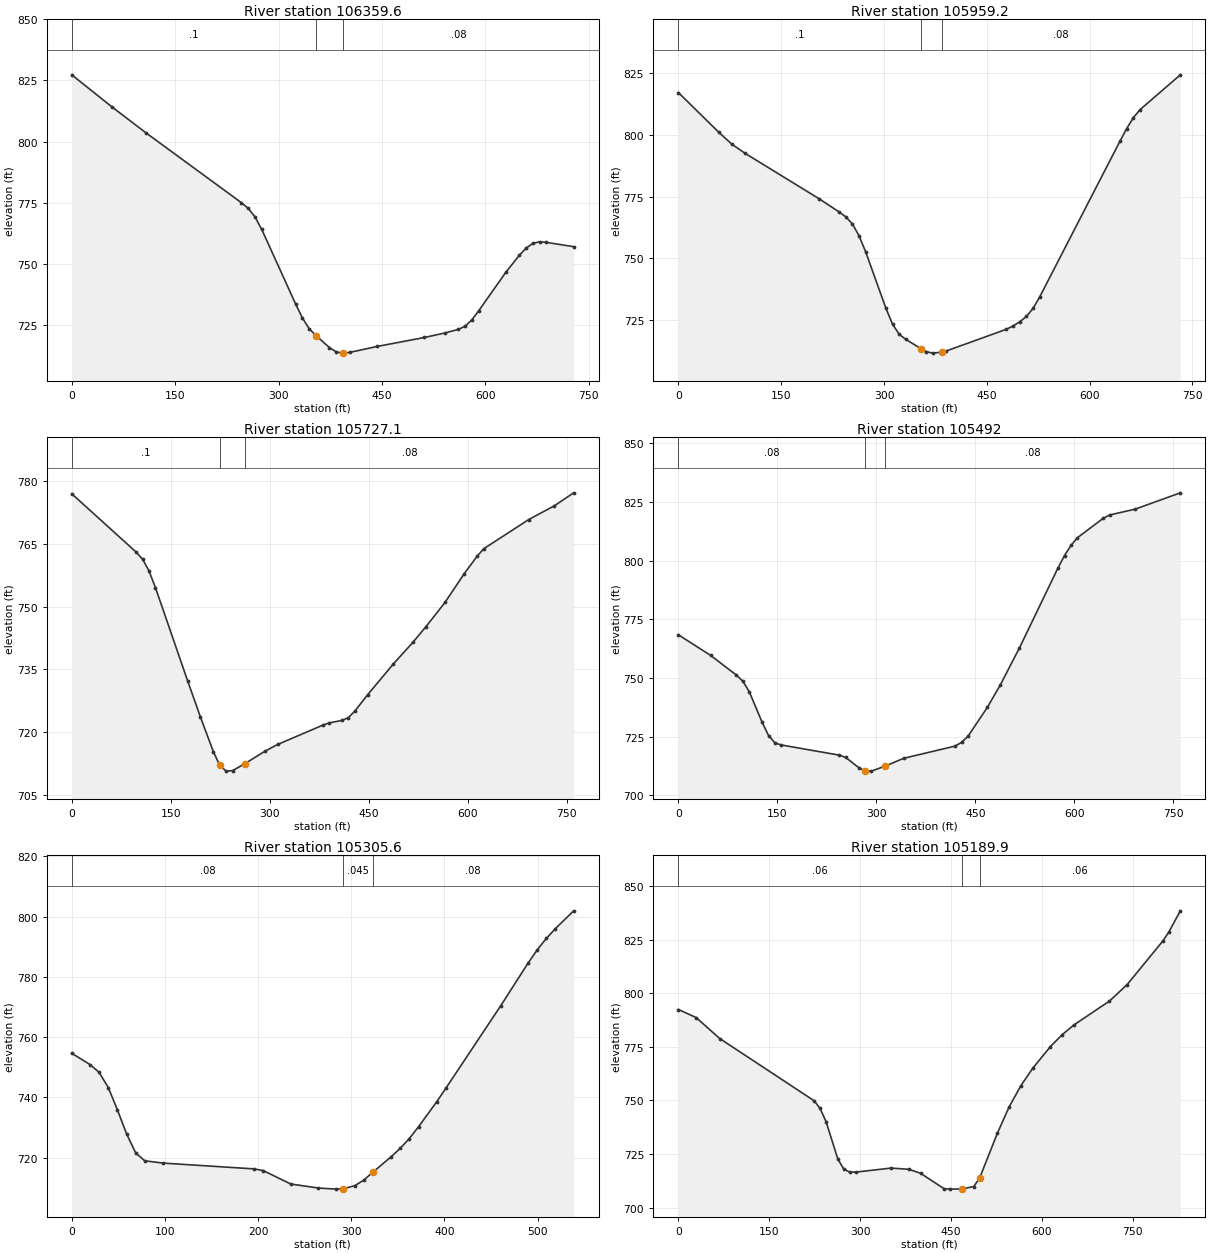
Type RM Length L Ch R = 1 ,106359.6,397.9,400.4,402.8
XS GIS Cut Line= 2
     1758510.391      608672.014     1758587.608      609395.908
#Sta/Elev= 30
       0   827.3      59  814.02   108.2  803.46     246  775.03   255.8  772.74
   265.6  769.29   275.5  764.11   324.6  733.66   334.5  727.89   344.3  723.52
   354.2  720.69   373.8  715.74   383.7     714   393.5  713.49     394  713.51
   403.4   713.8   442.7  716.21   511.6  719.89   541.1  721.72   560.8   723.2
   570.6  724.51   580.4   727.1   590.3  730.81   629.6  746.54   649.3  753.54
   659.1  756.44     669  758.39   678.8  759.04   688.6  758.77     728  757.02
#Mann= 3 , 0 , 0
       0      .1       0   354.2    .045       0     394     .08       0
Bank Sta=354.2,394
XS Rating Curve= 0 ,0
Exp/Cntr=0.3,0.1

Type RM Length L Ch R = 1 ,105959.2,223,232,241
XS GIS Cut Line= 2
     1758136.737       608729.46      1758174.13      609460.866
#Sta/Elev= 30
       0  817.09    58.6  801.12    78.1  796.19    97.6  792.47   205.1  774.18
   234.4  768.84   244.1  766.86   253.9  763.96   263.6  759.16   273.4  752.55
   302.7   729.9   312.5  723.39   322.2   719.3     332  717.24   354.3713.4371
   361.3  712.33   371.1   711.7   384.3712.1064   390.6  712.55   478.5  721.34
   488.2  722.67     498  724.36   507.8  726.52   517.5  729.79   527.3  734.49
   644.5  797.54   654.2  802.56     664     807   673.8  810.24   732.4  824.28
#Mann= 3 , 0 , 0
       0      .1       0   354.3    .045       0   384.3     .08       0
Bank Sta=354.3,384.3
XS Rating Curve= 0 ,0
Exp/Cntr=0.3,0.1

Type RM Length L Ch R = 1 ,105727.1,225.9,235.1,244.6
XS GIS Cut Line= 2
     1757962.793      608831.114     1757852.523      609583.622
#Sta/Elev= 30
       0  776.91    97.5     763   107.3   761.3     117  758.53   126.8  754.52
   175.5   732.3     195  723.63   214.5  715.39   224.3  712.07     234  710.72
   243.8  710.85   262.5712.5184   292.5  715.45     312  717.09   380.3  721.68
     390  722.23   409.5  722.82   419.3  723.51     429  725.06   448.5  728.99
   487.5  736.33   516.8  741.44   536.3  745.12   565.5  750.97   594.8  757.87
   614.3  762.02     624  763.77   692.3  770.75   731.3  774.05   760.5  777.14
#Mann= 3 , 0 , 0
       0      .1       0   224.3    .045       0   262.5     .08       0
Bank Sta=224.3,262.5
XS Rating Curve= 0 ,0
Exp/Cntr=0.3,0.1

Type RM Length L Ch R = 1 ,105492  ,164.8,186.4,207.2
XS GIS Cut Line= 2
     1757799.413      608767.142     1757536.602      609480.834
#Sta/Elev= 30
       0  768.39    48.8  759.62    87.8  751.25    97.5  748.68   107.3  744.18
   126.8  731.18   136.5  725.51   146.3  722.37     156  721.48   243.8  717.16
   253.5  716.17     273  711.88   282.8  710.46   292.5  710.35   313.6712.5441
   341.3  715.81   419.3  721.02     429  722.59   438.8  725.21     468  737.46
   487.5  746.92   516.8  762.86   575.3  796.98     585  802.11   594.8  806.44
   604.5  809.71   643.5  817.97   653.3   819.4   692.3  821.92   760.5  828.85
#Mann= 3 , 0 , 0
       0     .08       0   282.8    .045       0   313.6     .08       0
Bank Sta=282.8,313.6
XS Rating Curve= 0 ,0
Exp/Cntr=0.3,0.1

Type RM Length L Ch R = 1 ,105305.6,105.2,115.7,126.2
XS GIS Cut Line= 2
      1757746.87      608806.093     1757357.769      609178.522
#Sta/Elev= 30
       0  754.62    19.6  750.87    29.4  748.27    39.2  743.25      49  735.82
    58.8  727.89    68.6  721.55    78.3  718.92    97.9  718.16   195.9  716.22
   205.6  715.65     235  711.21   264.4  709.88     284  709.51   291.3  709.64
   303.6  710.64   313.4  712.51   323.2  715.15   342.8  720.27   352.6  723.09
   362.3  726.32   372.1  730.21   391.7  738.54   401.5  743.03   460.3  770.38
   489.6  784.52   499.4   788.9   509.2  792.74     519  796.01   538.6  801.92
#Mann= 3 , 0 , 0
       0     .08       0   291.3    .045       0   323.2     .08       0
Bank Sta=291.3,323.2
XS Rating Curve= 0 ,0
Exp/Cntr=0.3,0.1

Type RM Length L Ch R = 1 ,105189.9,179,188.5,198.5
XS GIS Cut Line= 2
     1757886.056      608678.952     1757169.925       609096.27
#Sta/Elev= 30
       0  792.42    29.2  788.67    68.3  778.86   224.3  749.81     234  746.25
   243.8  740.11   263.3  722.59     273  718.01   282.8  716.56   292.5  716.54
     351  718.44   380.3  717.88   399.8  716.02   438.8   708.8   448.6  708.62
   468.1  708.71   487.6  709.81   497.3  713.74   526.6  734.63   546.1     747
   565.6   756.9   585.1  765.02   614.3  775.13   633.8  780.69   653.3  785.26
   711.8  796.36   741.1  804.08   799.6  824.28   809.4  828.37   828.8  838.46
#Mann= 3 , 0 , 0
       0     .06       0   468.1    .045       0   497.3     .06       0
Bank Sta=468.1,497.3
XS Rating Curve= 0 ,0
Exp/Cntr=0.3,0.1

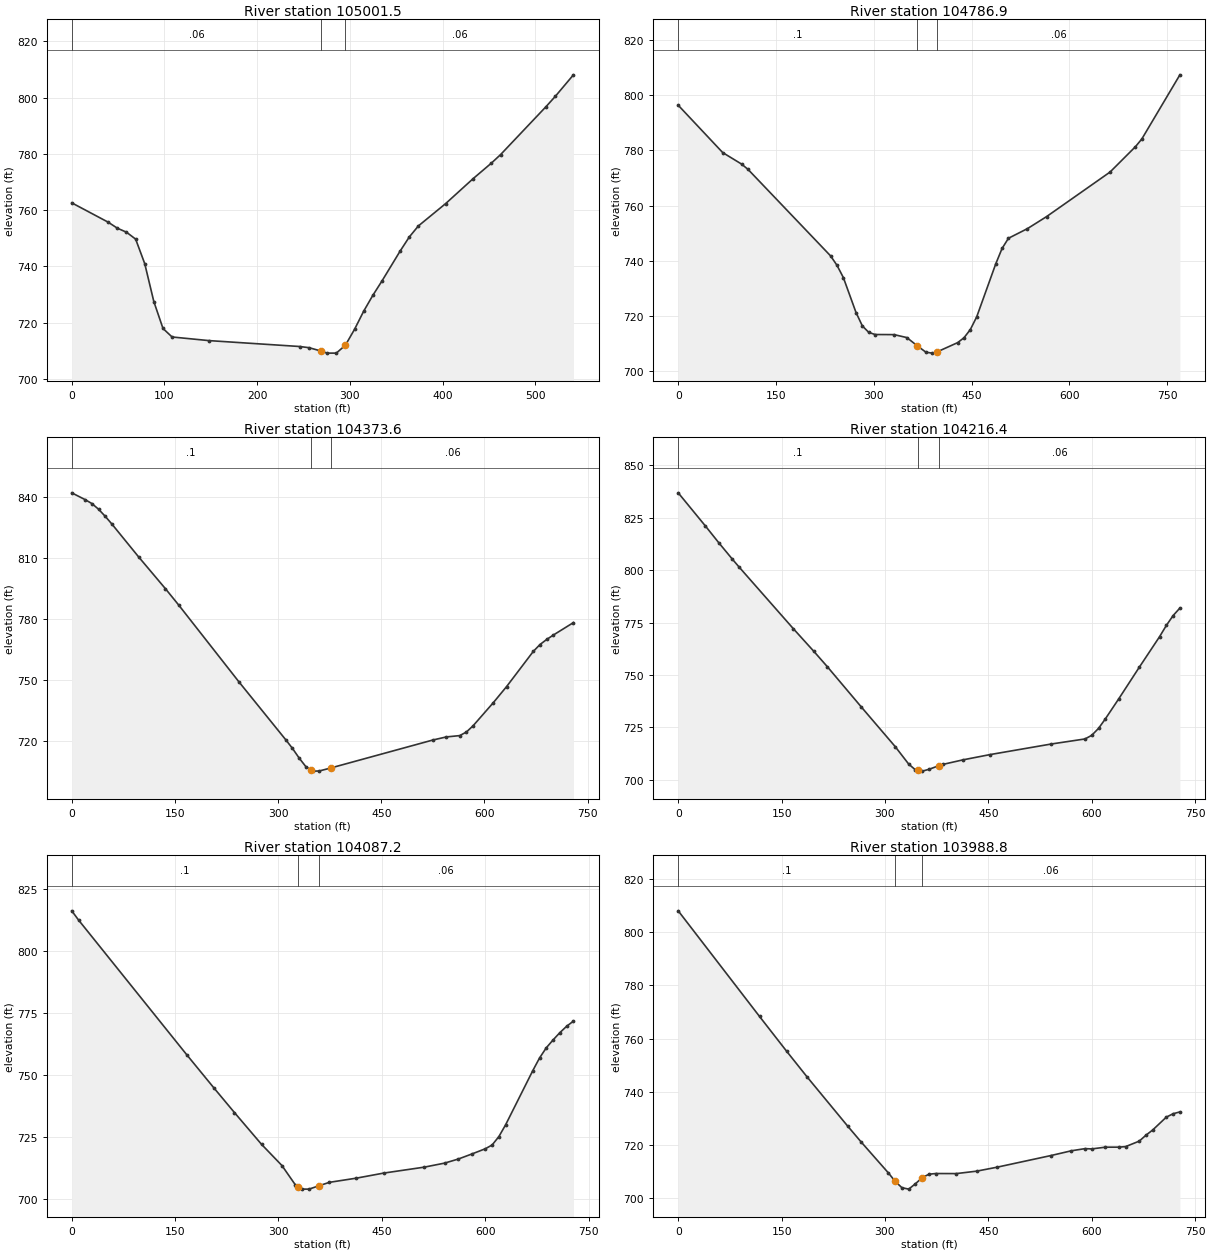
Type RM Length L Ch R = 1 ,105001.5,210.3,214.6,214
XS GIS Cut Line= 2
      1757689.19      608661.783     1757172.523      608822.379
#Sta/Elev= 30
       0  762.62    39.4  755.72    49.2   753.6      59  752.19    68.9  749.72
    78.7  741.01    88.5  727.54    98.4  717.96   108.2  714.94   147.6  713.66
   245.9  711.55   255.8  711.14   268.7  709.96   275.4  709.21   285.3   709.2
   295.1  712.02     305  717.69   314.8   724.1   324.6   729.7   334.5  734.83
   354.1  745.47     364  750.49   373.8  754.41   403.3  762.38   432.8  771.21
   452.5  776.73   462.4  779.75   511.5  796.83   521.4  800.45     541  808.12
#Mann= 3 , 0 , 0
       0     .06       0   268.7    .045       0   295.1     .06       0
Bank Sta=268.7,295.1
XS Rating Curve= 0 ,0
Exp/Cntr=0.3,0.1

Type RM Length L Ch R = 1 ,104786.9,433.7,413.2,394.5
XS GIS Cut Line= 2
     1757840.022      608480.554     1757082.368      608615.811
#Sta/Elev= 30
       0   796.4    68.2  779.24    97.4  775.03   107.2  773.11   233.8  741.75
   243.6  738.33   253.3  733.92   272.8   721.2   282.5  716.36   292.3  714.03
     302  713.25   331.2  713.21   350.7  712.14   366.6 709.178     380  706.83
   389.7   706.5   396.6706.8912   428.7  710.31   438.4  712.07   448.1  715.04
   457.9  719.66   487.1  738.87   496.8  744.46   506.6  748.16   535.8  751.66
     565     756   662.5  772.18   701.4  781.37   711.2  784.17   769.6  807.43
#Mann= 3 , 0 , 0
       0      .1       0   366.6    .045       0   396.6     .06       0
Bank Sta=366.6,396.6
XS Rating Curve= 0 ,0
Exp/Cntr=0.3,0.1

Type RM Length L Ch R = 1 ,104373.6,156.5,157.3,158
XS GIS Cut Line= 2
     1757611.256      607987.324     1757048.675      608451.578
#Sta/Elev= 30
       0  842.28    19.4  838.93    29.2  837.01    38.9  834.21    48.6  830.72
    58.4  826.86    97.2  810.68   136.2  794.98   155.6  786.87   243.1     749
   311.2  720.42   320.9  716.19   330.7  711.38   340.4  707.17   347.2705.6277
   350.1  704.97   359.8  705.03   377.2706.5844   525.2  720.34   544.6  721.84
   564.1   722.5   573.8  724.27   583.5  727.34   612.7  738.66   632.2  746.68
     671  764.02   680.8  767.44   690.5  769.93   700.2  772.11   729.4  778.26
#Mann= 3 , 0 , 0
       0      .1       0   347.2    .045       0   377.2     .06       0
Bank Sta=347.2,377.2
XS Rating Curve= 0 ,0
Exp/Cntr=0.3,0.1

Type RM Length L Ch R = 1 ,104216.4,129.1,129.1,129.1
XS GIS Cut Line= 2
     1757512.627      607872.856     1756943.594      608326.933
#Sta/Elev= 30
       0  836.81    39.4  821.03      59  812.97    78.7  805.15    88.5  801.39
   167.2  772.02   196.8  761.29   216.4  753.96   265.6  734.81   314.8  715.92
   334.5  707.55   344.3  704.79   348.2704.5615   354.2  704.21     364  705.08
   378.2706.8011   383.7  707.39   413.2  709.58   452.5  712.09   541.1  717.12
   590.3  719.54   600.1  721.28     610  724.61   619.8  729.09   639.5  738.78
     669  753.68   698.5  768.27   708.3  773.61   718.2  778.34     728  781.92
#Mann= 3 , 0 , 0
       0      .1       0   348.2    .045       0   378.2     .06       0
Bank Sta=348.2,378.2
XS Rating Curve= 0 ,0
Exp/Cntr=0.3,0.1

Type RM Length L Ch R = 1 ,104087.2,98.5,98.5,98.5
XS GIS Cut Line= 2
     1757418.856      607782.542     1756849.823      608236.619
#Sta/Elev= 30
       0  816.21     9.8  812.52   167.2  757.97   206.6  744.58   236.1  734.73
   275.5  721.87     305  713.34   324.6  705.48   328.5 704.826   334.5  703.82
   344.3  703.81   358.5705.1415   373.8  706.55   413.2  708.25   452.5  710.28
   511.6  712.69   541.1  714.32   560.8  715.95   580.4  717.98   600.1  720.11
     610  721.64   619.8  725.03   629.6   729.8     669  751.66   678.8  756.76
   688.6  760.89   698.5  764.08   708.3  767.01   718.2   769.6     728  771.67
#Mann= 3 , 0 , 0
       0      .1       0   328.5    .045       0   358.5     .06       0
Bank Sta=328.5,358.5
XS Rating Curve= 0 ,0
Exp/Cntr=0.3,0.1

Type RM Length L Ch R = 1 ,103988.8,155.1,155,155
XS GIS Cut Line= 2
     1757357.446      607705.585     1756788.413      608159.662
#Sta/Elev= 30
       0  807.96     118   768.3   157.4  755.22   186.9  745.64     246  727.11
   265.6  721.14     305  709.56   314.8  706.41   324.6  704.02   334.5  703.48
   344.3  705.51   354.2  707.84     364  709.08   373.8  709.34   403.4  709.31
   432.9  710.22   462.4   711.7   541.1   716.1   570.6  717.88   590.3  718.68
   600.1  718.58   619.8  719.23   639.5  719.24   649.3  719.45     669   721.5
   678.8  723.74   688.6   725.7   708.3  730.51   718.2  731.79     728  732.47
#Mann= 3 , 0 , 0
       0      .1       0   314.8    .045       0   354.2     .06       0
Bank Sta=314.8,354.2
XS Rating Curve= 0 ,0
Exp/Cntr=0.3,0.1

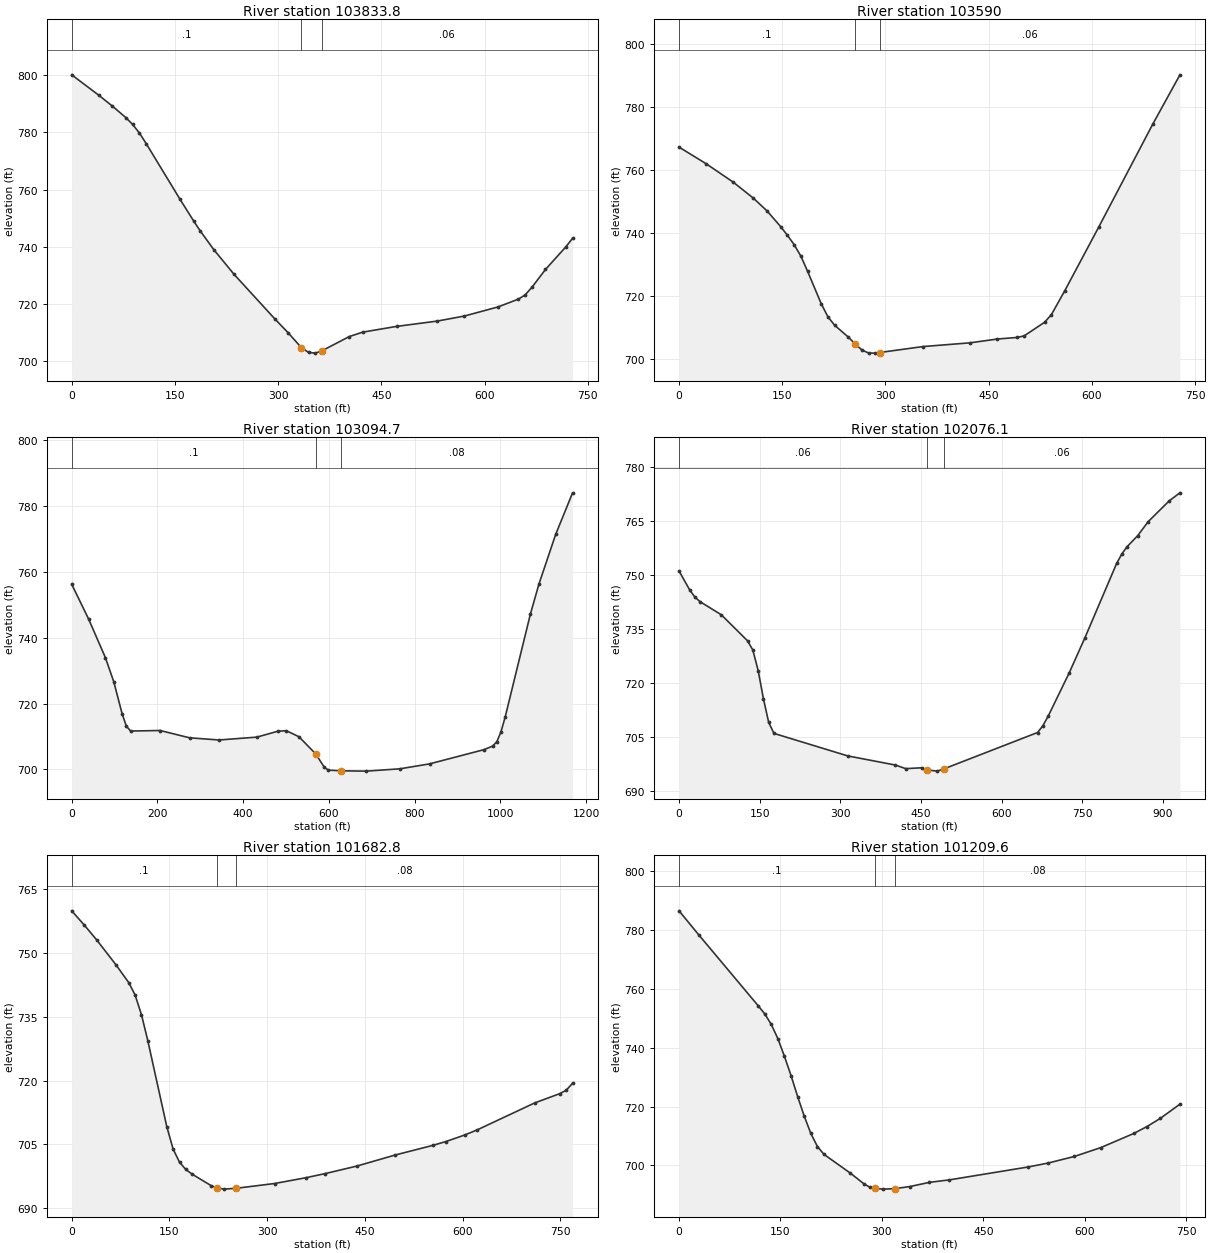
Type RM Length L Ch R = 1 ,103833.8,241.4,243.8,246.1
XS GIS Cut Line= 2
     1757270.624      607577.066     1756701.591      608031.143
#Sta/Elev= 30
       0  800.18    39.4  793.03      59  789.25    78.7   785.2    88.5  782.82
    98.4   779.8   108.2  776.13   157.4   756.6   177.1  749.06   186.9  745.49
   206.6  738.94   236.1  730.28   295.1  714.74   314.8  709.79   333.8704.6616
   344.3  702.95   354.2  702.72   363.8703.5527   403.4  708.52     423  710.07
   472.2  712.08   531.2  713.94   570.6   715.7   619.8  718.91   649.3  721.64
   659.1  723.11     669  725.81   688.6  732.02   718.2  739.94     728  742.95
#Mann= 3 , 0 , 0
       0      .1       0   333.8    .045       0   363.8     .06       0
Bank Sta=333.8,363.8
XS Rating Curve= 0 ,0
Exp/Cntr=0.3,0.1

Type RM Length L Ch R = 1 ,103590  ,499.5,495.3,467.4
XS GIS Cut Line= 2
     1757093.353      607430.509     1756500.927      607853.615
#Sta/Elev= 30
       0  767.27    39.4  761.98    78.7  756.13   108.2  750.99   127.9  746.97
   147.6     742   157.4  739.24   167.2  736.27   177.1  732.57   186.9  727.73
   206.6  717.46   216.4  713.27   226.3  710.56     246  706.83   255.8  704.68
   265.6  702.75   275.5  701.74   285.3  701.72   291.4  701.91   354.2   703.8
     423     705   462.4   706.2   491.9  706.72   501.7  707.22   531.2  711.53
   541.1  713.93   560.8  721.64     610  741.84   688.6  774.61     728  790.27
#Mann= 3 , 0 , 0
       0      .1       0   255.8    .045       0   291.4     .06       0
Bank Sta=255.8,291.4
XS Rating Curve= 0 ,0
Exp/Cntr=0.3,0.1

Type RM Length L Ch R = 1 ,103094.7,1018.5,1018.6,970.2
XS GIS Cut Line= 2
     1756961.925      606672.642     1756388.029       607690.52
#Sta/Elev= 30
       0  756.26    39.3  745.72    78.6  733.97    98.2  726.62   117.8  716.81
   127.6  713.13   137.5  711.67   206.2  711.83     275  709.61   343.7  708.95
   432.1  709.82   481.2  711.62   500.8  711.76   530.2  709.93   569.5  704.68
   589.2  700.67     599  699.79   628.4  699.58   687.4  699.49   765.9   700.2
   834.7  701.69   962.3  706.03     982   707.1   991.8  708.43  1001.6  711.48
  1011.4  716.01  1070.3  747.31    1090  756.31  1129.2  771.45  1168.5  784.03
#Mann= 3 , 0 , 0
       0      .1       0   569.5    .045       0   628.4     .08       0
Bank Sta=569.5,628.4
XS Rating Curve= 0 ,0
Exp/Cntr=0.3,0.1

Type RM Length L Ch R = 1 ,102076.1,354,393.3,413.1
XS GIS Cut Line= 2
     1756301.468      606699.232     1755879.644      607529.592
#Sta/Elev= 30
       0  751.18    19.6  745.95    29.4  743.92    39.2  742.63    78.4  739.02
   127.4  731.76   137.2   729.2   147.1   723.5   156.9  715.66   166.7  709.05
   176.5  706.01   313.7  699.75     402  697.22   421.6  696.21     451  696.45
     462695.8396   480.4  695.52     492696.1176   666.7  706.26   676.5  708.12
   686.3  710.77   725.5  722.84   754.9  732.66   813.7  753.27   823.5  755.94
   833.3  757.96   852.9     761   872.5  764.92   911.8  770.72   931.4  772.91
#Mann= 3 , 0 , 0
       0     .06       0     462    .045       0     492     .06       0
Bank Sta=462,492
XS Rating Curve= 0 ,0
Exp/Cntr=0.3,0.1

Type RM Length L Ch R = 1 ,101682.8,476.8,473.2,461.6
XS GIS Cut Line= 2
     1756203.015      606614.214     1755572.124      607053.846
#Sta/Elev= 30
       0  759.92    19.5  756.54    38.9  752.98    68.1   747.2    87.6  743.04
    97.3  740.14   107.1  735.51   116.8  729.41     146  709.17   155.7   703.9
   165.5  700.82   175.2  699.11   184.9  698.01   214.1  695.31   222.3694.8331
   233.6  694.49   252.3694.6862   311.5  695.81   360.2  697.19   389.4  698.15
     438  699.92   496.4   702.5   554.8  704.79   574.3  705.67   603.5  707.22
     623  708.45   710.6  714.74   749.5  716.95   759.2  717.74     769  719.39
#Mann= 3 , 0 , 0
       0      .1       0   222.3    .045       0   252.3     .08       0
Bank Sta=222.3,252.3
XS Rating Curve= 0 ,0
Exp/Cntr=0.3,0.1

Type RM Length L Ch R = 1 ,101209.6,398.6,391.4,389.5
XS GIS Cut Line= 2
      1755953.27      606222.547     1755448.236      606764.248
#Sta/Elev= 30
       0  786.61    29.2  778.42   116.9  754.34   126.7  751.55   136.4  747.95
   146.2  743.08   155.9  737.07   165.7  730.47   175.4  723.39   185.2  716.68
   194.9  710.84   204.6  706.41   214.4  703.72   253.4  697.34   272.9   693.8
   282.6  692.48   289.3692.1484   302.1  691.91   319.3692.0778   341.1  692.78
   370.3  694.22   399.5  695.05   516.5  699.46   545.7  700.78   584.7  703.04
   623.7  706.05   672.4  710.85   691.9  713.21   711.4  715.95   740.6  720.82
#Mann= 3 , 0 , 0
       0      .1       0   289.3    .045       0   319.3     .08       0
Bank Sta=289.3,319.3
XS Rating Curve= 0 ,0
Exp/Cntr=0.3,0.1

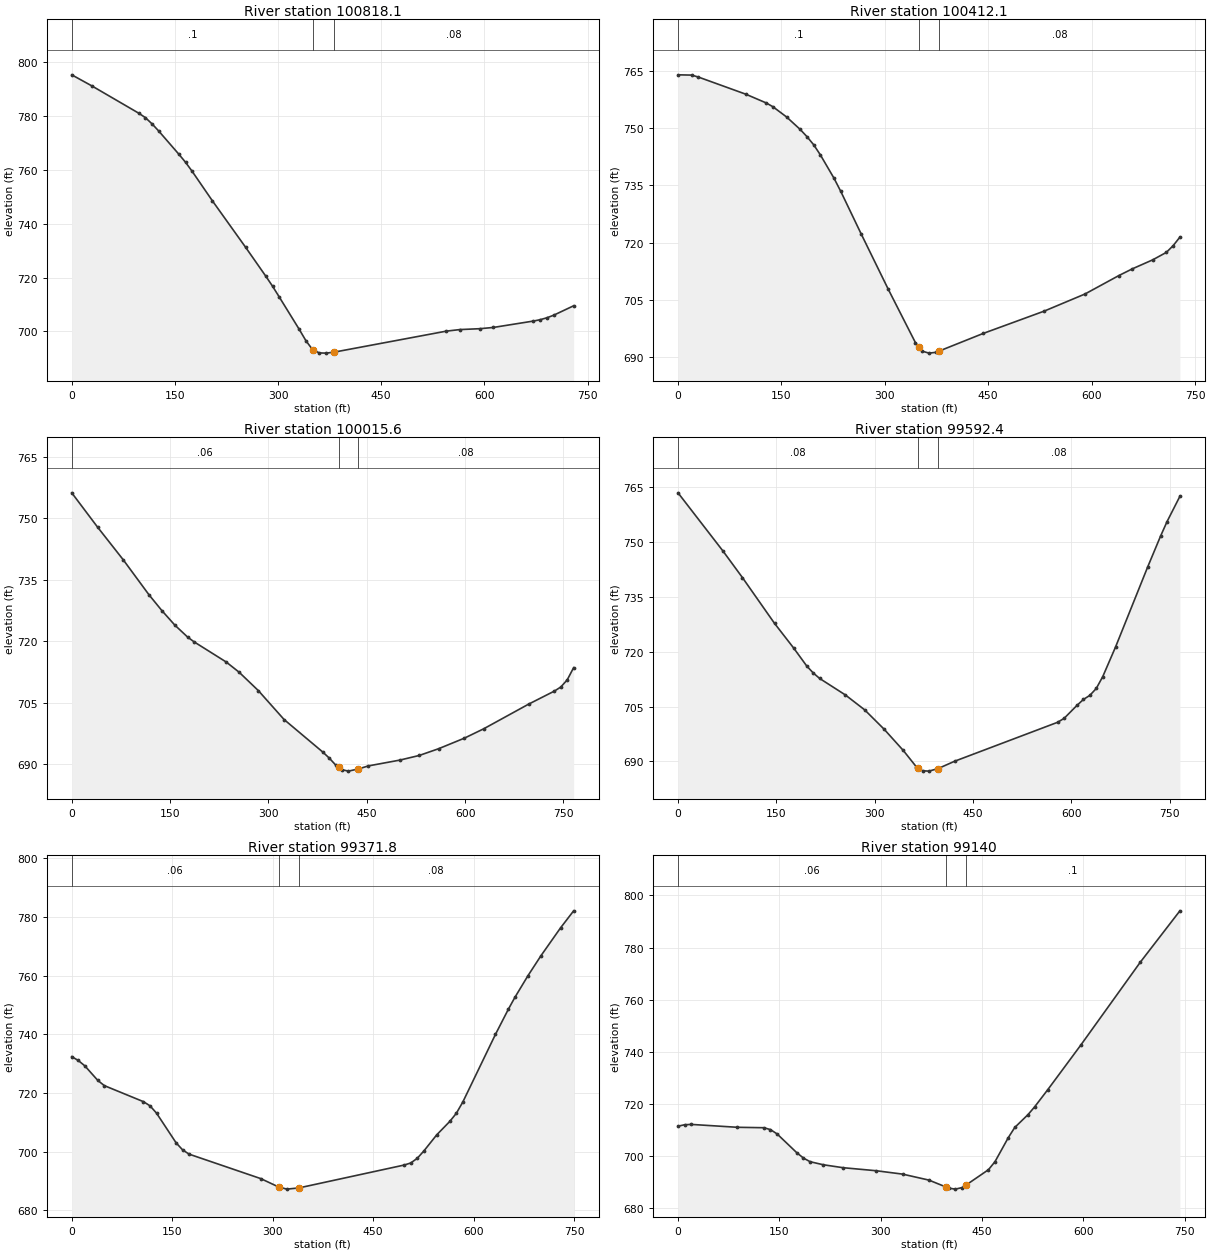
Type RM Length L Ch R = 1 ,100818.1,404.5,406,407
XS GIS Cut Line= 2
     1755667.774      605866.724     1755277.194      606483.192
#Sta/Elev= 30
       0  795.34    29.2  791.23    97.3   781.1     107  779.45   116.8  777.11
   126.5  774.45   155.7  765.85   165.4  762.86   175.2  759.44   204.3   748.6
     253  731.19   282.2  720.51   291.9  716.83   301.6  712.85   330.8  700.76
   340.6  696.51   350.3   693.2   351.1693.1027     360  692.02   369.8  691.94
   381.1692.2859   544.9  700.12   564.4  700.69   593.6  701.02     613  701.48
   671.4  703.86   681.1  704.36   690.9  705.07   700.6  706.01   729.8  709.53
#Mann= 3 , 0 , 0
       0      .1       0   351.1    .045       0   381.1     .08       0
Bank Sta=351.1,381.1
XS Rating Curve= 0 ,0
Exp/Cntr=0.3,0.1

Type RM Length L Ch R = 1 ,100412.1,394.7,396.5,397.2
XS GIS Cut Line= 2
     1755386.086      605596.444     1754980.072      606200.717
#Sta/Elev= 30
       0  763.89    19.7  763.82    29.5  763.31    98.4  758.82   127.9  756.54
   137.7  755.54   157.4  752.88   177.1  749.63   186.9  747.75   196.8   745.6
   206.6  742.92   226.3  736.84   236.1   733.4   265.6  722.31     305   707.8
   344.3  693.88     349692.8118   354.2  691.63     364  691.11   373.8  691.31
     379691.6672   442.7  696.26   531.2   702.1   590.3  706.57   639.5   711.4
   659.1  713.16   688.6  715.51   708.3  717.45   718.2  719.21     728  721.45
#Mann= 3 , 0 , 0
       0      .1       0     349    .045       0     379     .08       0
Bank Sta=349,379
XS Rating Curve= 0 ,0
Exp/Cntr=0.3,0.1

Type RM Length L Ch R = 1 ,100015.6,418.3,423.2,421
XS GIS Cut Line= 2
     1755175.118      605277.773      1754730.12      605900.825
#Sta/Elev= 30
       0  756.27    39.3   747.9    78.5  739.91   117.8  731.35   137.4   727.5
   157.1  723.96   176.7  721.02   186.5  719.86   235.6  714.92   255.2  712.44
   284.7  707.92   323.9  700.86   382.8  692.93   392.6  691.47   402.5  689.76
   407.3 689.187   412.3  688.59   422.1  688.25   437.3688.7855   452.3  689.52
   500.6  690.95   530.1  692.08   559.5  693.72   598.8   696.3   628.2  698.58
   696.9  704.62   736.2  707.81     746  708.81   755.8  710.56   765.6  713.54
#Mann= 3 , 0 , 0
       0     .06       0   407.3    .045       0   437.3     .08       0
Bank Sta=407.3,437.3
XS Rating Curve= 0 ,0
Exp/Cntr=0.3,0.1

Type RM Length L Ch R = 1 ,99592.4 ,232.6,220.6,208.4
XS GIS Cut Line= 2
     1754793.063      605187.435     1754348.066      605810.487
#Sta/Elev= 30
       0  763.53    68.7  747.56    98.2  740.33   147.2  727.78   176.7  720.95
   196.3  716.11   206.1  714.22     216  712.69   255.2  708.18   284.7  704.09
   314.1  698.84   343.6  692.97   363.2  688.55   366.8688.1276     373   687.4
   382.8   687.3   396.8688.0036   422.1  690.02   579.1  700.68     589  701.76
   608.6  705.31   618.4  706.93   628.2  708.05     638  709.94   647.9  713.18
   667.5  721.33   716.6  743.29   736.2  751.71     746  755.65   765.6  762.58
#Mann= 3 , 0 , 0
       0     .08       0   366.8    .045       0   396.8     .08       0
Bank Sta=366.8,396.8
XS Rating Curve= 0 ,0
Exp/Cntr=0.3,0.1

Type RM Length L Ch R = 1 ,99371.8 ,232.2,231.7,229.6
XS GIS Cut Line= 2
     1754490.615      605095.751     1754239.304      605801.542
#Sta/Elev= 30
       0  732.42     9.7  731.11    19.5  729.28    38.9  724.31    48.6  722.54
     107  717.07   116.8  715.65   126.5  713.17   155.7  703.06   165.4  700.65
   175.1  699.18   282.2  690.83   308.9687.9704   321.1  687.25   338.9 687.654
   496.2  695.46     506  696.16   515.7  697.75   525.4   700.2   544.9  705.78
   564.3  710.33   574.1  713.11   583.8  716.97   632.4  739.97   651.9  748.65
   661.6  752.67   681.1  760.05   700.6  766.89   729.7  776.34   749.2  782.13
#Mann= 3 , 0 , 0
       0     .06       0   308.9    .045       0   338.9     .08       0
Bank Sta=308.9,338.9
XS Rating Curve= 0 ,0
Exp/Cntr=0.3,0.1

Type RM Length L Ch R = 1 ,99140   ,191.9,203.6,215.8
XS GIS Cut Line= 2
     1754282.159      605026.564     1754056.042      605734.093
#Sta/Elev= 30
       0  711.47     9.8  712.03    19.6  712.16      88  711.05     127  710.89
   136.8  710.17   146.6  708.52   175.9  701.27   185.7  699.24   195.5  697.85
     215  696.68   244.3  695.55   293.2  694.39   332.3  693.09   371.4  690.79
   396.1688.1929   400.7   687.7   410.5  687.33   420.3  687.92   426.1688.8528
   459.4  694.77   469.1  697.85   488.7  707.03   498.4  710.99     518  715.92
   527.8  718.89   547.3   725.5   596.2  742.62   684.1  774.36   742.8   794.1
#Mann= 3 , 0 , 0
       0     .06       0   396.1    .045       0   426.1      .1       0
Bank Sta=396.1,426.1
XS Rating Curve= 0 ,0
Exp/Cntr=0.3,0.1

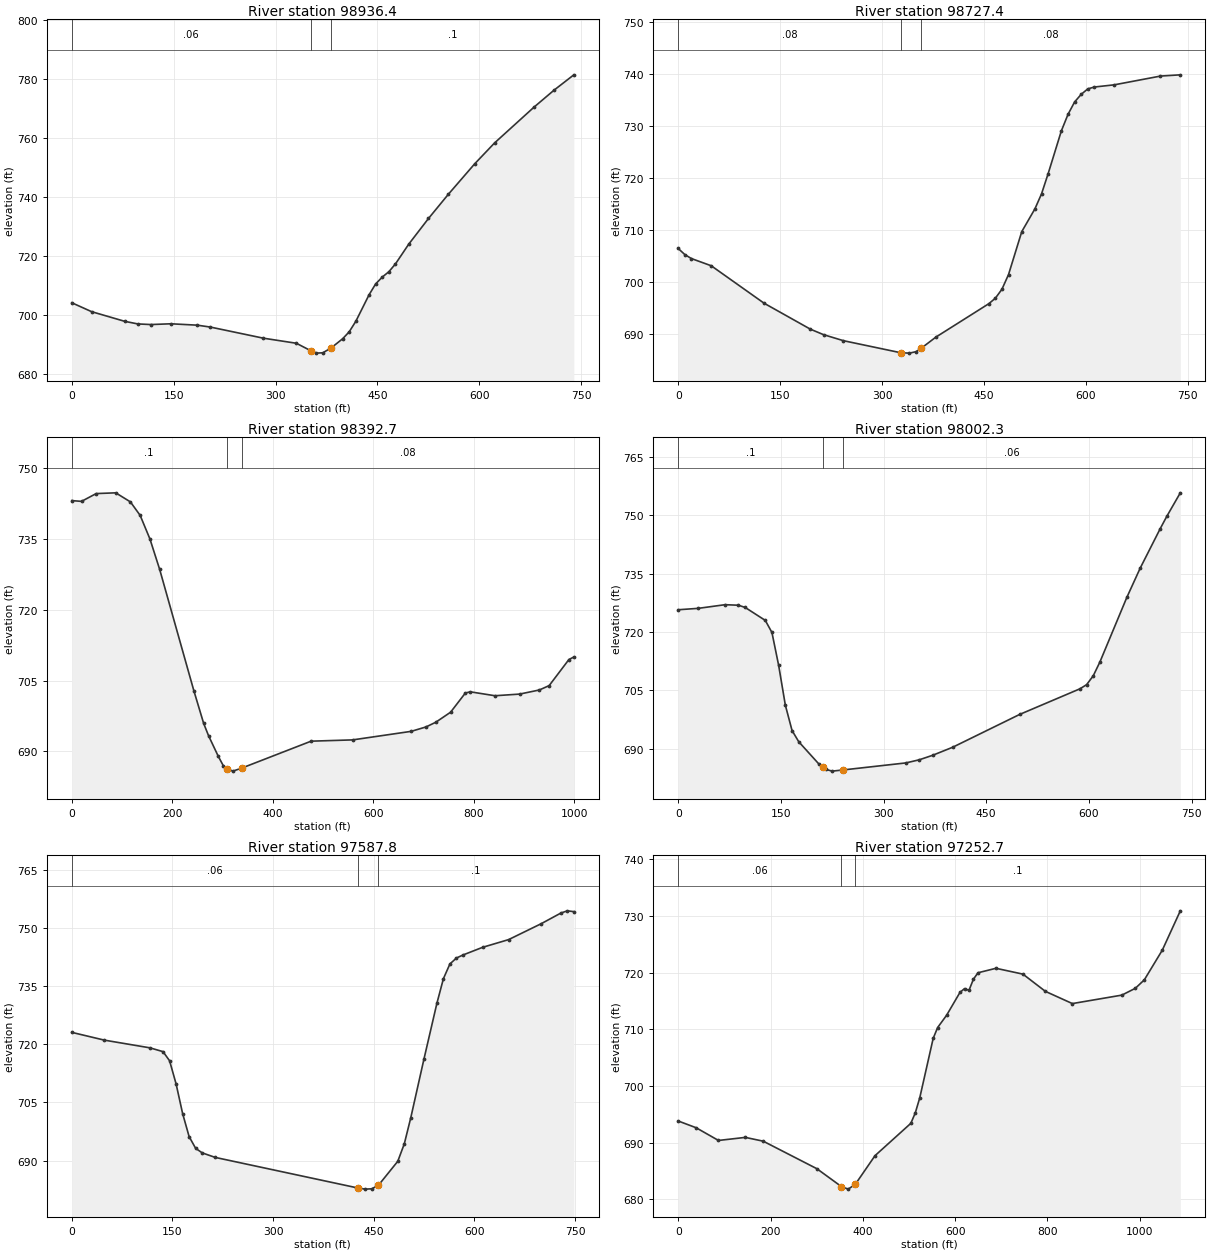
Type RM Length L Ch R = 1 ,98936.4 ,211.4,209,206.4
XS GIS Cut Line= 2
      1754175.39      605014.446      1753779.79      605638.725
#Sta/Elev= 30
       0  704.21    29.2  701.19    77.8  697.93    97.2  697.04   116.7  696.83
   145.9  697.09   184.8  696.62   204.2  695.97     282  692.22   330.6   690.5
   351.6688.0053   359.8  687.16   369.5  687.27   381.6688.8783   398.7  692.01
   408.4  694.37   418.2  697.95   437.6  706.88   447.3  710.57   457.1   712.9
   466.8  714.71   476.5  717.35     496  724.02   525.1  732.72   554.3   740.9
   593.2  751.24   622.4  758.29   680.7  770.45   709.9  776.14   739.1  781.34
#Mann= 3 , 0 , 0
       0     .06       0   351.6    .045       0   381.6      .1       0
Bank Sta=351.6,381.6
XS Rating Curve= 0 ,0
Exp/Cntr=0.3,0.1

Type RM Length L Ch R = 1 ,98727.4 ,351.1,334.7,315.3
XS GIS Cut Line= 2
     1753990.708       604912.52     1753610.213      605546.118
#Sta/Elev= 30
       0  706.43     9.7  705.26    19.4  704.49    48.6   703.1   126.4  695.88
   194.5  690.88   213.9  689.82   243.1  688.66   327.6686.3326   340.4  686.26
   350.1  686.54   357.6687.1895   379.3  689.35   457.1  695.78   466.8  696.84
   476.5  698.57   486.2   701.4   505.7  709.68   525.1  714.08   534.8  716.96
   544.6  720.88     564  729.11   573.8  732.29   583.5  734.68   593.2  736.15
   602.9   737.2   612.6  737.56   641.8  737.98   709.9  739.67   739.1  739.91
#Mann= 3 , 0 , 0
       0     .08       0   327.6    .045       0   357.6     .08       0
Bank Sta=327.6,357.6
XS Rating Curve= 0 ,0
Exp/Cntr=0.3,0.1

Type RM Length L Ch R = 1 ,98392.7 ,388.1,390.5,393.5
XS GIS Cut Line= 4
      1753750.31      604600.388      1753650.48      605066.171
     1753662.294      605166.454     1753516.382      605562.397
#Sta/Elev= 30
       0  743.14    19.4  742.98    48.6  744.63    87.5  744.79   116.7  742.87
   136.1  740.01   155.6     735     175  728.54     243  702.84   262.5  695.92
   272.2  693.32   291.6  688.94   301.4  686.99   308.3686.2786   320.8   685.8
   338.3 686.442   476.4  692.15     559  692.42   675.5  694.23   704.9  695.16
   724.5  696.16     754  698.29   783.4  702.36   793.2  702.61   842.3  701.78
   891.4  702.13   930.6     703   950.2  703.93   989.5  709.46   999.3  709.99
#Mann= 3 , 0 , 0
       0      .1       0   308.3    .045       0   338.3     .08       0
Bank Sta=308.3,338.3
XS Rating Curve= 0 ,0
Exp/Cntr=0.3,0.1

Type RM Length L Ch R = 1 ,98002.3 ,369.8,414.5,454.1
XS GIS Cut Line= 2
     1753352.584      604710.389     1753215.234      605431.021
#Sta/Elev= 30
       0  725.73    29.3  726.09    68.5  727.03      88  726.89    97.8  726.32
   127.2  722.99   136.9  719.89   146.7  711.45   156.5   701.2   166.3  694.68
   176.1  691.79   205.4  686.09   210.9685.3099   215.2   684.7     225  684.24
   240.9684.5424   332.6  686.35   352.1  687.15   371.7  688.31     401  690.38
   498.8  698.81   586.9   705.4   596.7  706.47   606.4  708.75   616.2  712.33
   655.4  728.88   674.9   736.4   704.3   746.6     714  749.79   733.6  755.79
#Mann= 3 , 0 , 0
       0      .1       0   210.9    .045       0   240.9     .06       0
Bank Sta=210.9,240.9
XS Rating Curve= 0 ,0
Exp/Cntr=0.3,0.1

Type RM Length L Ch R = 1 ,97587.8 ,346.1,335.1,323.9
XS GIS Cut Line= 2
     1753339.487      604669.405     1752671.059      605005.784
#Sta/Elev= 30
       0   723.1    48.6  721.09   116.6   719.1     136  718.12   145.8  715.76
   155.5  709.78   165.2  702.14   174.9  696.18   184.6  693.16   194.4  691.98
   213.8  690.81   427.1682.8875   437.3  682.62     447   682.7   457.1683.6222
   485.9  689.81   495.6  694.31   505.3  701.08   524.8  716.13   544.2  730.61
   553.9  736.96   563.6  740.77   573.4   742.3   583.1  743.08   612.2  745.05
   651.1  747.05   699.7  751.16   728.9   753.9   738.6  754.48   748.3  754.27
#Mann= 3 , 0 , 0
       0     .06       0   427.1    .045       0   457.1      .1       0
Bank Sta=427.1,457.1
XS Rating Curve= 0 ,0
Exp/Cntr=0.3,0.1

Type RM Length L Ch R = 1 ,97252.7 ,512.1,517.1,517.7
XS GIS Cut Line= 3
     1753085.749      604337.528     1752596.258      604734.092
     1752445.626      605166.502
#Sta/Elev= 30
       0  693.83    38.8  692.64    87.2   690.4   145.4  690.94   184.2  690.27
   300.4  685.42   353.7682.2626   368.3  681.82   383.7682.6689   426.4  687.72
     504  693.42   513.7  695.27   523.4  697.94   552.4  708.39   562.1  710.31
   581.5  712.47   610.6  716.52   620.3  717.16     630  716.87   639.7  718.84
   649.5  719.96   688.4  720.75   746.9  719.72   795.6  716.68     854  714.53
   961.2  716.02   990.4  717.22  1009.9  718.71  1048.9  723.95  1087.9  730.88
#Mann= 3 , 0 , 0
       0     .06       0   353.7    .045       0   383.7      .1       0
Bank Sta=353.7,383.7
XS Rating Curve= 0 ,0
Exp/Cntr=0.3,0.1