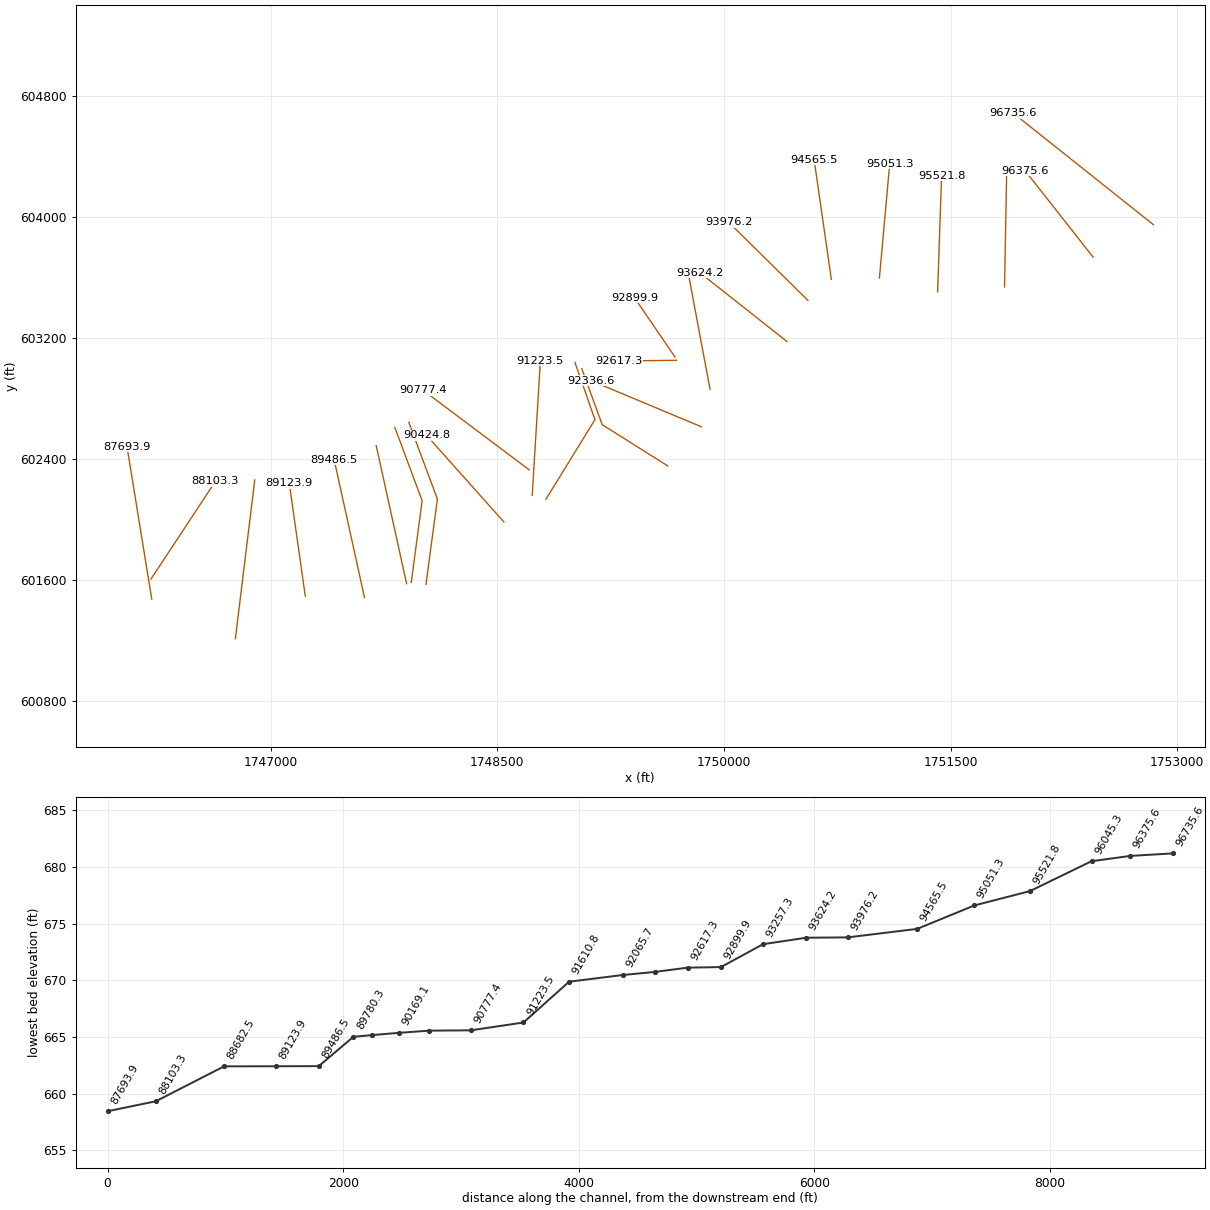
HEC-RAS study EightenmC1.prj: EightenmC1

--- EightenmC1.g01 (geometry) --- (continued)

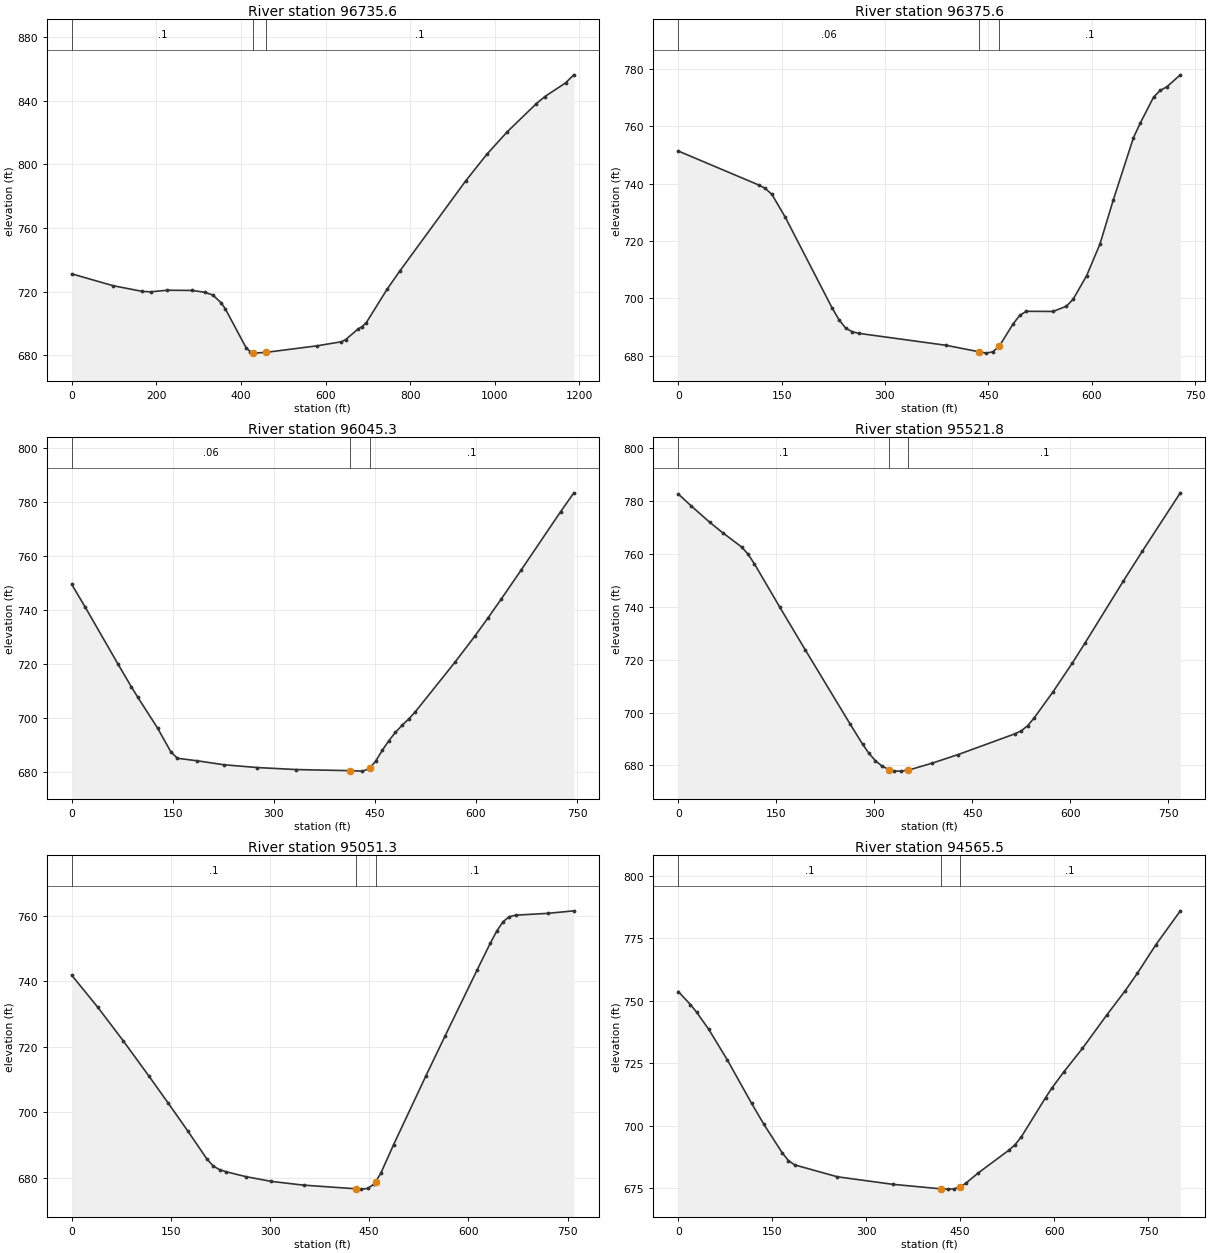
Type RM Length L Ch R = 1 ,96735.6 ,373.8,360,346.2
XS GIS Cut Line= 2
     1752843.188      603948.401     1751914.254      604687.142
#Sta/Elev= 30
       0  731.11    98.1  723.63   166.8  720.07   186.4  719.79   225.6   720.8
   284.5  720.67   313.9  719.53   333.5  717.79   353.1  712.88   362.9  709.13
     412  684.64   421.8  682.17   428.8  681.47   431.6  681.19   458.8681.6704
   578.7  685.74   637.6  688.37   647.4  689.71   676.8   696.4   686.6  697.94
   696.4  700.46   745.5  721.45   774.9   732.7   931.8  789.87   980.9  806.32
  1029.9   820.7  1098.6   838.4  1118.2  842.74  1167.2  851.36  1186.9  856.46
#Mann= 3 , 0 , 0
       0      .1       0   428.8    .045       0   458.8      .1       0
Bank Sta=428.8,458.8
XS Rating Curve= 0 ,0
Exp/Cntr=0.3,0.1

Type RM Length L Ch R = 1 ,96375.6 ,360.4,330.3,298.5
XS GIS Cut Line= 2
     1752443.431      603733.932     1751993.044      604306.596
#Sta/Elev= 30
       0  751.37   116.6  739.55   126.3  738.34     136  736.24   155.4  728.28
   223.4  696.67   233.1  692.68   242.8  689.73   252.6  688.39   262.3  687.85
   388.6   683.7   436.2 681.452   446.8  680.97   456.6  681.44   466.2683.4986
   485.7  691.06   495.4  694.08   505.1  695.54     544  695.49   563.4  697.32
   573.1  699.75   592.6  707.91     612  718.98   631.4  734.36   660.6     756
   670.3  761.01   689.7  770.08   699.4  772.46   709.1  773.74   728.6   777.9
#Mann= 3 , 0 , 0
       0     .06       0   436.2    .045       0   466.2      .1       0
Bank Sta=436.2,466.2
XS Rating Curve= 0 ,0
Exp/Cntr=0.3,0.1

Type RM Length L Ch R = 1 ,96045.3 ,522.8,523.5,522.3
XS GIS Cut Line= 2
     1751857.235      603536.411     1751871.231      604281.468
#Sta/Elev= 30
       0   749.6    19.6  741.36    68.6  720.14    88.2  711.81      98  707.84
   127.5  696.38   147.1  687.61   156.9  685.25   186.3  684.33   225.5  682.87
   274.5  681.84   333.4  681.08   412.5680.6714   431.4   680.5   441.2  681.34
   442.5681.7167     451  684.18   460.8  688.17   470.6  691.77   480.4  694.85
   490.3  697.48   500.1   699.8   509.9  702.47   568.7   720.8   598.1  730.42
   617.7  737.18   637.3  744.15   666.8  754.86   725.6  776.55   745.2  783.51
#Mann= 3 , 0 , 0
       0     .06       0   412.5    .045       0   442.5      .1       0
Bank Sta=412.5,442.5
XS Rating Curve= 0 ,0
Exp/Cntr=0.3,0.1

Type RM Length L Ch R = 1 ,95521.8 ,457.9,470.5,456.1
XS GIS Cut Line= 2
     1751414.335      603504.666     1751440.771      604272.601
#Sta/Elev= 30
       0  782.79    19.4  778.35    48.6  771.98    68.1   768.1    97.3  762.66
     107  759.93   116.7  756.29   155.6  739.86   194.5  723.73   262.6  695.88
   282.1   688.1   291.8   684.6   301.5  681.88   311.2  679.91     322678.4561
   330.7   677.9   340.4  677.86     352678.2095   389.1  680.92     428   684.1
   515.5     692   525.2  693.17     535  695.12   544.7  697.99   573.9     708
     603  718.72   622.5  726.34   680.8  749.66     710  761.01   768.4  783.21
#Mann= 3 , 0 , 0
       0      .1       0     322    .045       0     352      .1       0
Bank Sta=322,352
XS Rating Curve= 0 ,0
Exp/Cntr=0.3,0.1

Type RM Length L Ch R = 1 ,95051.3 ,465.6,485.7,494.4
XS GIS Cut Line= 2
      1751029.07      603596.106     1751097.284      604352.645
#Sta/Elev= 30
       0  741.86      39   732.2    77.9  721.85   116.9  711.06   146.1   702.8
   175.3  694.41   204.5  685.78   214.2  683.63     224  682.49   233.7   681.9
   262.9  680.43   301.9  678.96   350.6  677.82   429.7676.7051   438.2   676.6
     448  676.82   457.7   678.2   459.7678.8598   467.4   681.4   486.9  690.17
   535.6  711.09   564.8  723.36   613.5  743.58     633  751.58   642.8   755.3
   652.5  758.21   662.2  759.77     672  760.21   720.6  760.77   759.6  761.53
#Mann= 3 , 0 , 0
       0      .1       0   429.7    .045       0   459.7      .1       0
Bank Sta=429.7,459.7
XS Rating Curve= 0 ,0
Exp/Cntr=0.3,0.1

Type RM Length L Ch R = 1 ,94565.5 ,562.4,589.4,615.3
XS GIS Cut Line= 2
     1750710.855       603586.46      1750596.82       604379.49
#Sta/Elev= 30
       0  753.74    19.5   748.5    29.3  745.46    48.8  738.53    78.2  726.38
   117.2  708.87   136.8  700.46   166.1  689.01   175.9  685.97   185.6  684.26
     254  679.47     342  676.47   419.7674.6262   429.9  674.53   439.7  674.62
   449.7675.3599   459.2  676.94   478.8  681.04   527.6  690.12   537.4  692.33
   547.2  695.35   586.2  711.21     596  714.96   615.6  721.62   644.9  730.91
   683.9  744.34   713.2  754.03   732.8  761.12   762.1  772.46   801.2  786.08
#Mann= 3 , 0 , 0
       0      .1       0   419.7    .045       0   449.7      .1       0
Bank Sta=419.7,449.7
XS Rating Curve= 0 ,0
Exp/Cntr=0.3,0.1

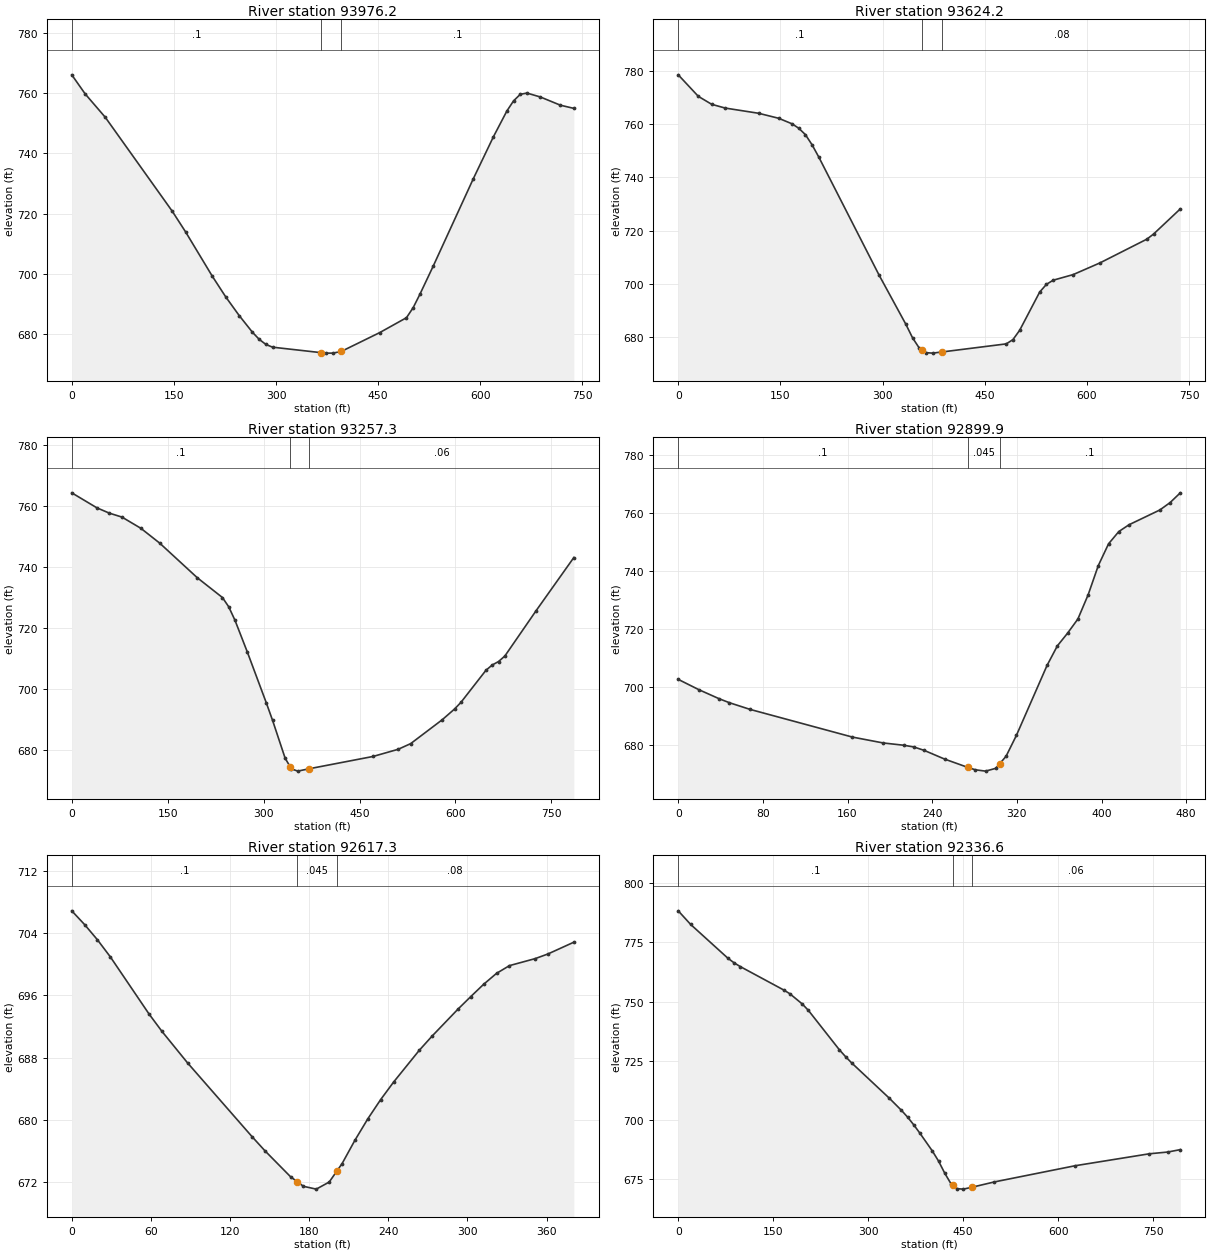
Type RM Length L Ch R = 1 ,93976.2 ,343.9,352,358.9
XS GIS Cut Line= 2
     1750555.936      603447.639     1750030.799      603965.191
#Sta/Elev= 30
       0  766.02    19.7  759.69    49.2  751.95   147.5  720.83   167.1  713.98
   206.4  699.26   226.1  692.42   245.8  686.25   265.4  680.68   275.3  678.34
   285.1  676.66   294.9  675.75   365.9673.9433   373.6  673.78   383.4  673.78
   395.9674.3546   452.2  680.58   491.5  685.52   501.4  688.87   511.2  693.27
   530.9  702.68   589.8  731.65   619.3  745.54     639  754.05   648.8   757.4
   658.7  759.57   668.5  759.97   688.2  758.67   717.6  755.95   737.3   754.9
#Mann= 3 , 0 , 0
       0      .1       0   365.9    .045       0   395.9      .1       0
Bank Sta=365.9,395.9
XS Rating Curve= 0 ,0
Exp/Cntr=0.3,0.1

Type RM Length L Ch R = 1 ,93624.2 ,399.2,366.8,335
XS GIS Cut Line= 2
     1750417.904      603175.184     1749839.399      603631.791
#Sta/Elev= 30
       0  778.73    29.5  770.61    49.1  767.61    68.8   766.2   117.9  764.23
   147.4  762.34     167  760.26   176.9  758.59   186.7  756.16   196.5  752.32
   206.4  747.67   294.8  703.19   334.1  684.65   343.9  679.55   353.8  675.66
   357.8674.9539   363.6  673.93   373.4  673.75   387.8674.2079   481.5  677.24
   491.3  678.84   501.2  682.37   530.6   696.8   540.5   699.7   550.3  701.25
   579.8  703.38   619.1  707.79   687.9  716.74   697.7  718.66     737  728.16
#Mann= 3 , 0 , 0
       0      .1       0   357.8    .045       0   387.8     .08       0
Bank Sta=357.8,387.8
XS Rating Curve= 0 ,0
Exp/Cntr=0.3,0.1

Type RM Length L Ch R = 1 ,93257.3 ,335,357.5,375.5
XS GIS Cut Line= 2
     1749908.068      602859.285     1749763.216      603631.033
#Sta/Elev= 30
       0  764.26    39.3  759.35    58.9   757.6    78.5  756.32     108  752.66
   137.4  747.82   196.3  736.47   235.6     730   245.4  726.98   255.2  722.57
   274.8  712.03   304.3  695.49   314.1  689.76   333.7   677.4   341.7674.5673
   343.5  673.93   353.4  673.18   371.7673.9736   471.1  677.98   510.4  680.32
     530  682.18   579.1  689.95   598.7  693.52   608.6  695.68   647.8   706.2
   657.6  707.92   667.4  709.04   677.3  710.85   726.3  725.72   785.2  743.09
#Mann= 3 , 0 , 0
       0      .1       0   341.7    .045       0   371.7     .06       0
Bank Sta=341.7,371.7
XS Rating Curve= 0 ,0
Exp/Cntr=0.3,0.1

Type RM Length L Ch R = 1 ,92899.9 ,237.7,282.6,326
XS GIS Cut Line= 2
     1749675.936      603073.388     1749408.106      603464.947
#Sta/Elev= 30
       0  702.78    19.4  699.24    38.7   696.1    48.4  694.73    67.8  692.44
   164.6  682.89   193.6  680.87     213  680.08   222.7  679.48   232.4  678.31
   251.7  675.31   273.8672.4255   280.8  671.61   290.4  671.16   300.1  672.13
   303.8673.7244   309.8  676.31   319.5  683.45   348.5   707.6   358.2  714.31
   367.9  718.71   377.6  723.57   387.3  731.91   396.9  741.98   406.6  749.49
   416.3  753.72     426  756.07     455  761.14   464.7  763.68   474.4  767.06
#Mann= 3 , 0 , 0
       0      .1       0   273.8    .045       0   303.8      .1       0
Bank Sta=273.8,303.8
XS Rating Curve= 0 ,0
Exp/Cntr=0.3,0.1

Type RM Length L Ch R = 1 ,92617.3 ,299.5,280.7,261.9
XS GIS Cut Line= 2
     1749685.912       603051.58     1749305.276      603047.106
#Sta/Elev= 30
       0  706.87     9.8  705.09    19.5  703.14    29.3  700.94    58.6  693.61
    68.3   691.4    87.8  687.33   136.6  677.87   146.4  676.05   165.9   672.7
   170.9672.0724   175.7  671.47   185.4  671.11   195.2  672.02   200.9673.4043
     205   674.4   214.7  677.39   224.5  680.15   234.2  682.61     244  684.86
   263.5  688.95   273.3  690.79   292.8  694.23   302.6  695.86   312.3  697.43
   322.1  698.84   331.9  699.83   351.4  700.73   361.1  701.33   380.7  702.84
#Mann= 3 , 0 , 0
       0      .1       0   170.9    .045       0   200.9     .08       0
Bank Sta=170.9,200.9
XS Rating Curve= 0 ,0
Exp/Cntr=0.3,0.1

Type RM Length L Ch R = 1 ,92336.6 ,277.8,270.9,262.9
XS GIS Cut Line= 2
     1749850.594      602611.693     1749119.085      602917.569
#Sta/Elev= 30
       0  788.32    19.6  782.57    78.3  768.33    88.1  766.37    97.9  764.77
   166.4   754.9   176.2   753.3   195.8  748.98   205.6  746.24   254.5   729.6
   264.3  726.69   274.1     724   332.8  709.29   352.4  704.05   362.2  701.16
     372  697.87   381.8  694.31   401.3  686.85   411.1  682.59   420.9  677.46
   430.7  673.02   433.6672.3956   440.5  670.91   450.3  670.73   463.6671.5136
   499.2  673.77   626.5   680.6   743.9  685.66   773.3  686.41   792.9  687.42
#Mann= 3 , 0 , 0
       0      .1       0   433.6    .045       0   463.6     .06       0
Bank Sta=433.6,463.6
XS Rating Curve= 0 ,0
Exp/Cntr=0.3,0.1

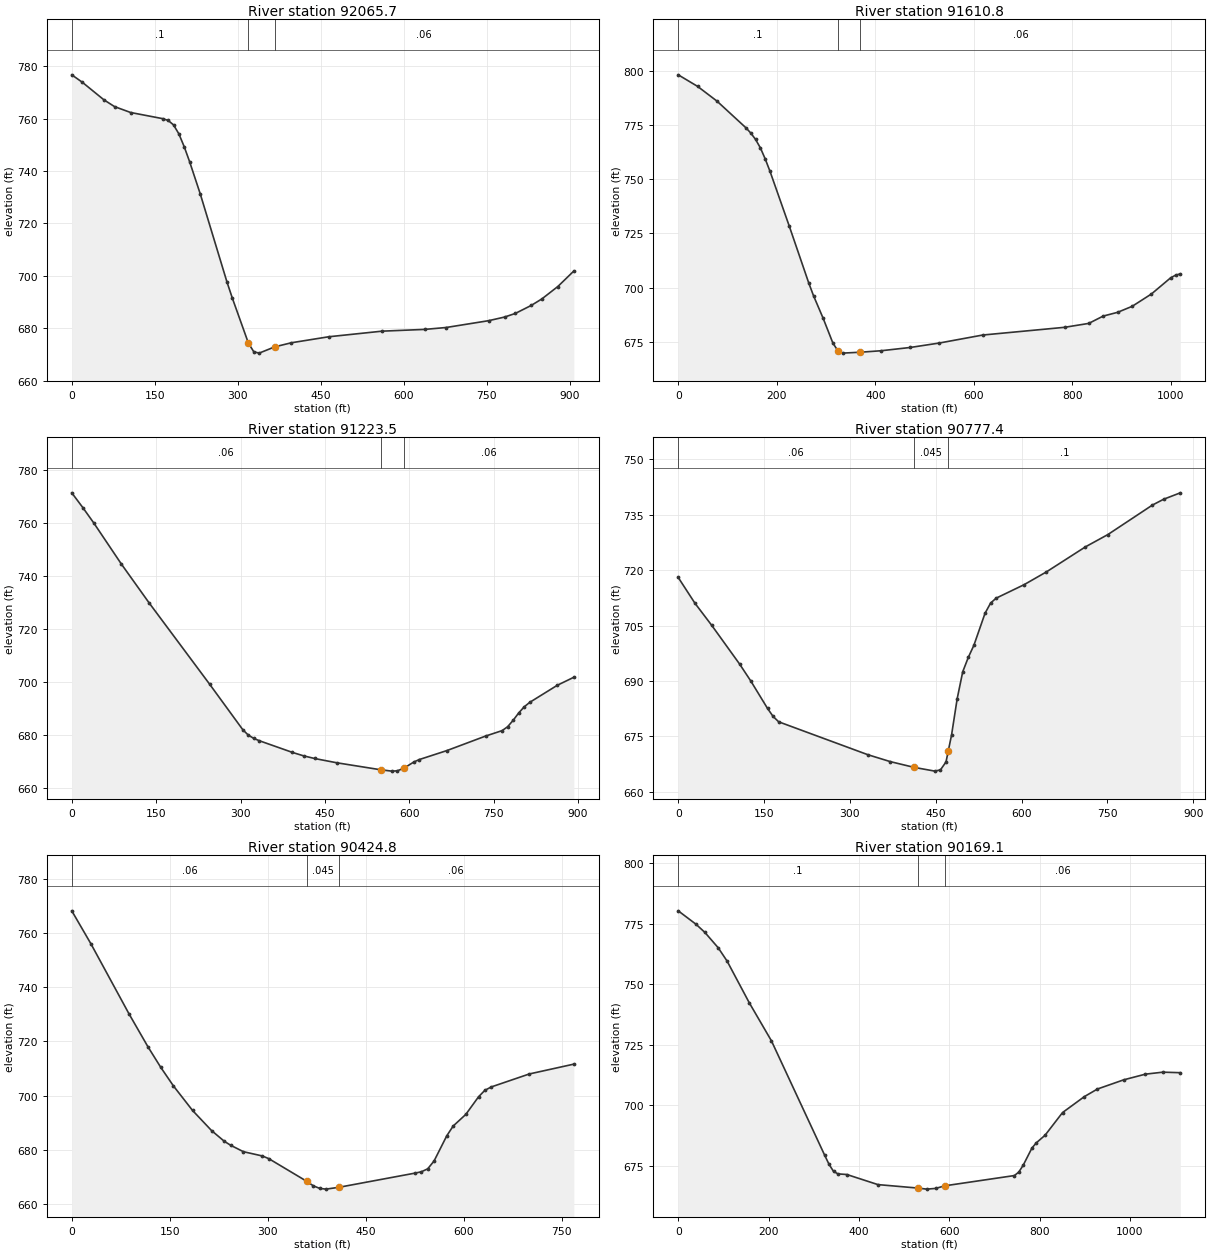
Type RM Length L Ch R = 1 ,92065.7 ,523.4,454.9,381.9
XS GIS Cut Line= 3
     1749628.032      602352.956     1749194.054      602625.684
     1749058.745      602996.179
#Sta/Elev= 30
       0  776.73    19.3  773.85      58  767.19    77.4  764.58   106.4  762.34
   164.4  759.99   174.1  759.31   183.8  757.62   193.4  754.22   203.1  749.29
   212.8  743.61   232.1  731.27   280.5  697.53   290.1  691.44   319.1  674.27
   328.8  670.98   338.5  670.46   366.6  672.85   396.5  674.41   464.2  676.71
   560.7  678.85   637.6  679.52   676.1  680.24   753.1  682.85   781.9  684.24
   801.2  685.61     830  688.67   849.3  691.17   878.1   695.9     907  701.82
#Mann= 3 , 0 , 0
       0      .1       0   319.1    .045       0   366.6     .06       0
Bank Sta=319.1,366.6
XS Rating Curve= 0 ,0
Exp/Cntr=0.3,0.1

Type RM Length L Ch R = 1 ,91610.8 ,364.9,387.3,410
XS GIS Cut Line= 3
     1748821.856      602132.927     1749146.005      602659.033
     1749013.589      603037.855
#Sta/Elev= 30
       0  798.05    39.2  792.74    78.5  785.97   137.3  773.68   147.1  771.28
   156.9  768.32   166.8  764.39   176.6  759.29   186.4  753.53   225.6  728.23
   264.8  702.27   274.6  696.32   294.3  685.84   313.9  674.53   323.7  671.07
   333.5  669.87   369.7  670.29     412  670.97   470.8  672.47   529.7  674.51
     618   678.2   784.3  681.76   833.3  683.56   862.6  686.93     892  688.67
   921.4  691.42   960.5   697.1   999.7  704.58  1009.5  705.76  1019.2  706.38
#Mann= 3 , 0 , 0
       0      .1       0   323.7    .045       0   369.7     .06       0
Bank Sta=323.7,369.7
XS Rating Curve= 0 ,0
Exp/Cntr=0.3,0.1

Type RM Length L Ch R = 1 ,91223.5 ,401.6,446.1,490.5
XS GIS Cut Line= 2
     1748730.531      602157.573     1748784.926      603048.537
#Sta/Elev= 30
       0  771.51    19.6  765.94    39.2  760.09    88.3  744.54   137.3  729.95
   245.2  699.11   304.1  681.92   313.9  679.88   323.7  678.64   333.5  677.76
   392.4  673.34     412  672.06   431.6  671.05   470.8  669.44   549.3  666.78
   568.9  666.27   578.7  666.38   590.4  667.37   608.2  669.73     618  670.66
     667  674.05   735.7  679.53   765.1  681.59   774.9  683.06   784.7  685.49
   794.5  688.25   804.3  690.57   814.2  692.28   863.2  698.74   892.6  701.77
#Mann= 3 , 0 , 0
       0     .06       0   549.3    .045       0   590.4     .06       0
Bank Sta=549.3,590.4
XS Rating Curve= 0 ,0
Exp/Cntr=0.3,0.1

Type RM Length L Ch R = 1 ,90777.4 ,361.9,352.6,342.4
XS GIS Cut Line= 2
     1748710.587      602327.206     1748008.664      602853.474
#Sta/Elev= 30
       0     718    29.2  711.03    58.5  705.05   107.2  694.57   126.7     690
     156  682.56   165.7   680.4   175.5  678.93   331.4  670.02   370.4  668.16
   411.7  666.61   448.4  665.58   458.2  665.92   467.9  668.07   471.7  670.93
   477.6  675.37   487.4  685.17   497.1  692.48   506.9  696.39   516.6  699.64
   536.1  708.32   545.9   711.1   555.6  712.41   604.4  716.06   643.4  719.52
   711.6   726.3   750.6  729.61   828.6  737.61   848.1  739.18   877.3  740.92
#Mann= 3 , 0 , 0
       0     .06       0   411.7    .045       0   471.7      .1       0
Bank Sta=411.7,471.7
XS Rating Curve= 0 ,0
Exp/Cntr=0.3,0.1

Type RM Length L Ch R = 1 ,90424.8 ,372.2,255.8,234.4
XS GIS Cut Line= 2
     1748543.068      601982.528     1748030.991      602555.755
#Sta/Elev= 30
       0  768.17    29.2  756.06    87.6  730.19   116.8  717.96   136.2  710.47
   155.7  703.58   184.9  694.56     214  687.14   233.5  683.19   243.2  681.73
   262.7  679.36   291.9  677.77   301.6  676.79     360  668.39   369.7  666.78
   379.5  665.82   389.2  665.55   408.6  666.21   525.4  671.45   535.1  671.94
   544.9  673.04   554.6  675.92     574  685.18   583.8   688.8   603.2   693.1
   622.7  699.59   632.4  701.99   642.2  703.23   700.5  708.02   768.6  711.64
#Mann= 3 , 0 , 0
       0     .06       0     360    .045       0   408.6     .06       0
Bank Sta=360,408.6
XS Rating Curve= 0 ,0
Exp/Cntr=0.3,0.1

Type RM Length L Ch R = 1 ,90169.1 ,157.2,229.3,202.6
XS GIS Cut Line= 4
     1748027.473      601568.999     1748102.901      602133.775
     1747998.029      602415.402     1747913.816      602641.552
#Sta/Elev= 30
       0  780.38    39.3  774.84    58.9  771.48    88.4  765.13   108.1  759.63
   157.2   742.4   206.3  726.66   324.2  679.37     334  675.57   343.8   672.7
   353.7  671.66   373.3   671.4   442.1  667.23   530.5   665.8   550.1  665.36
   569.8  665.65   590.5  666.74   744.3  670.97     754  672.41   763.7  675.22
   783.1  682.34   792.8   684.5   812.1  687.62   850.9  697.01   899.3  703.61
   928.2  706.74   986.1  710.52  1034.4  712.88    1073   713.7  1111.6  713.48
#Mann= 3 , 0 , 0
       0      .1       0   530.5    .045       0   590.5     .06       0
Bank Sta=530.5,590.5
XS Rating Curve= 0 ,0
Exp/Cntr=0.3,0.1

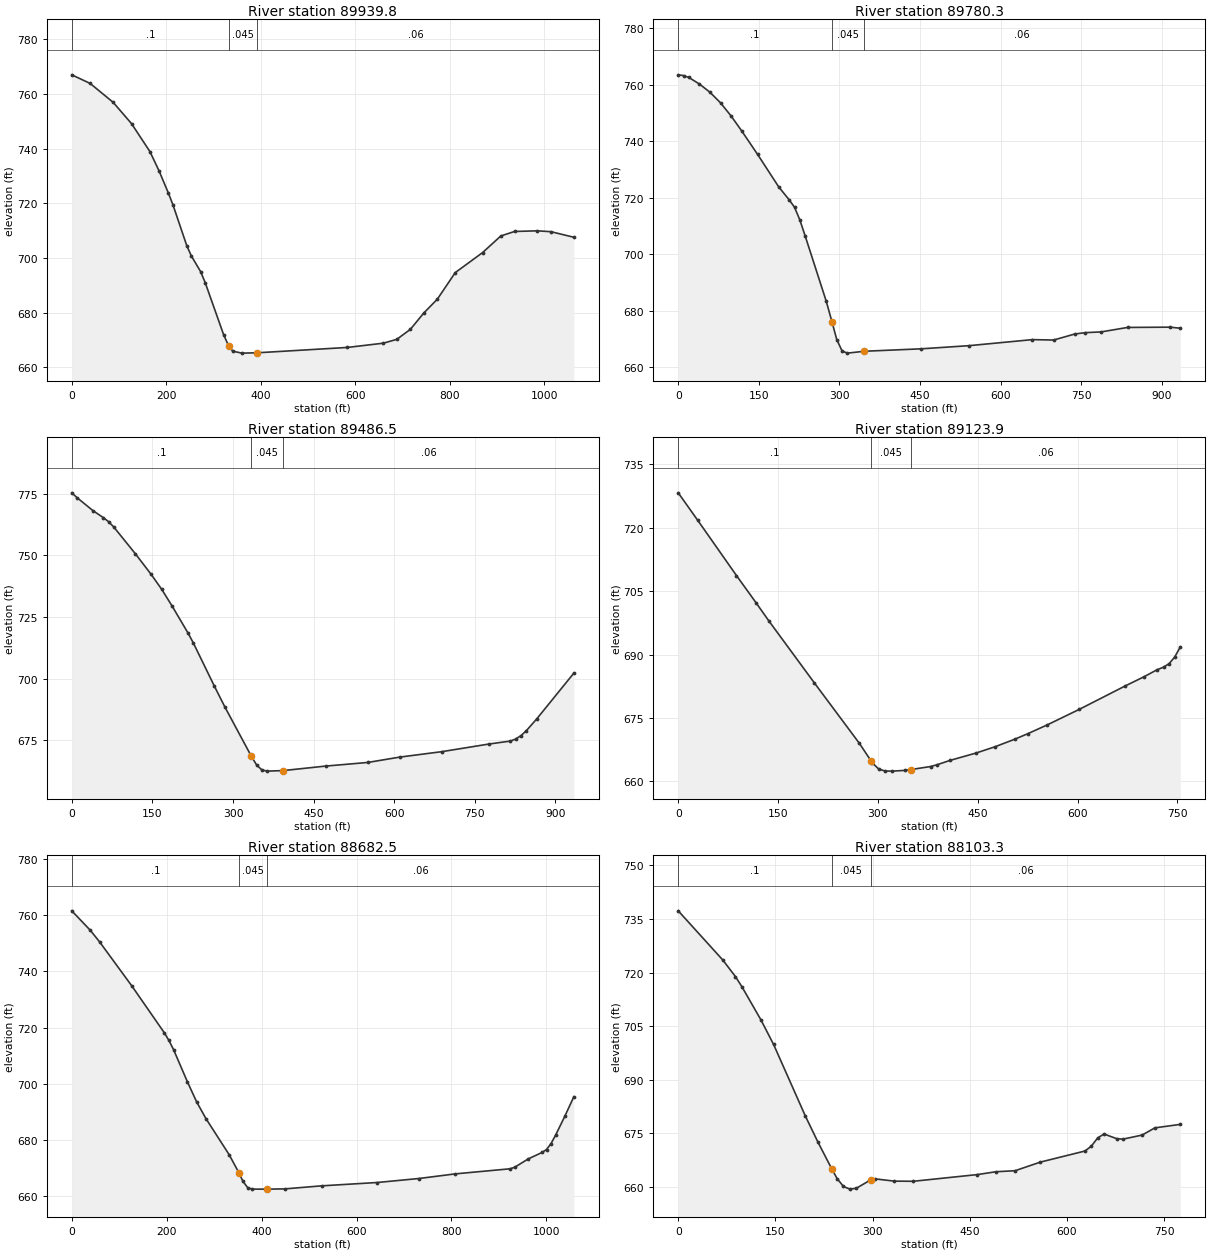
Type RM Length L Ch R = 1 ,89939.8 ,137.9,159.5,183.7
XS GIS Cut Line= 4
     1747929.884      601582.033     1748002.059      602122.449
     1747905.764      602381.045      1747821.55      602607.195
#Sta/Elev= 30
       0  767.01    38.9  763.86    87.6  756.94   126.6  749.12   165.5  738.89
     185  731.75   204.5  723.72   214.2   719.4   243.4  704.48   253.1  700.71
   272.6  695.02   282.3  690.99   321.3  671.94   332.2   667.7   340.8  665.86
   360.2  665.16   392.2  665.28   583.3  667.24   659.4   668.8   687.9  670.21
   716.5  673.86     745  679.85   773.6   684.9   811.6  694.64   869.4  701.96
     908  708.04     937  709.68   985.3  709.92  1014.2   709.6  1062.5  707.56
#Mann= 3 , 0 , 0
       0      .1       0   332.2    .045       0   392.2     .06       0
Bank Sta=332.2,392.2
XS Rating Curve= 0 ,0
Exp/Cntr=0.3,0.1

Type RM Length L Ch R = 1 ,89780.3 ,293.7,293.8,294
XS GIS Cut Line= 3
     1747899.098      601574.239     1747742.545      602285.228
     1747698.191      602486.663
#Sta/Elev= 30
       0   763.5     9.8  763.24    19.7  762.57    39.4  760.25      59  757.34
    78.7  753.59    98.4  748.93   118.1  743.65   147.6  735.36   186.9  723.87
   206.6  719.22   216.4  716.64   226.3  712.15   236.1  706.55   275.5  683.33
   286.2     676   295.1  669.74     305  665.75   314.8  665.01   346.2  665.67
   452.6  666.54   541.1  667.65   659.2  669.79   698.5  669.64   737.8  671.77
   757.5  672.26     787  672.52   836.1   674.1   914.6   674.2   934.3  673.83
#Mann= 3 , 0 , 0
       0      .1       0   286.2    .045       0   346.2     .06       0
Bank Sta=286.2,346.2
XS Rating Curve= 0 ,0
Exp/Cntr=0.3,0.1

Type RM Length L Ch R = 1 ,89486.5 ,364.9,362.6,357.3
XS GIS Cut Line= 3
     1747620.375      601482.173     1747463.822      602193.163
     1747419.468      602394.597
#Sta/Elev= 30
       0  775.33     9.8  773.37    39.4  768.11      59  765.23    68.9  763.56
    78.7  761.32   118.1  750.68   147.6  742.28   167.2  736.23   186.9  729.33
   216.4  718.42   226.3  714.39   265.6  696.79   285.3  688.29   333.8   668.6
   344.3  664.79   354.2  662.86     364  662.42   393.8  662.65   472.2  664.46
   550.9  665.94     610   668.1   688.7  670.32   777.1  673.44   816.4  674.62
   826.2  675.46   836.1  676.86   845.9  678.82   865.5  683.68   934.3  702.18
#Mann= 3 , 0 , 0
       0      .1       0   333.8    .045       0   393.8     .06       0
Bank Sta=333.8,393.8
XS Rating Curve= 0 ,0
Exp/Cntr=0.3,0.1

Type RM Length L Ch R = 1 ,89123.9 ,452.9,441.4,429.3
XS GIS Cut Line= 3
     1747228.499      601491.847     1747125.932      602213.833
     1747122.398      602238.709
#Sta/Elev= 30
       0  728.26    29.2  721.78    87.5  708.69   116.7   702.3   136.1  697.97
   204.2  683.36   272.2  668.98   289.4  664.91   291.7  664.36   301.4  662.87
   311.1  662.44   320.9  662.41   340.3  662.58   349.4  662.78   379.2   663.5
   388.9  663.92   408.4  664.95   447.3  666.68   476.4   668.2   505.6  669.96
     525  671.25   554.2  673.33   602.8  677.04   670.9  682.51   700.1  684.76
   719.5   686.4   729.2  687.01   737.6  687.84     746  689.42   754.4   691.8
#Mann= 3 , 0 , 0
       0      .1       0   289.4    .045       0   349.4     .06       0
Bank Sta=289.4,349.4
XS Rating Curve= 0 ,0
Exp/Cntr=0.3,0.1

Type RM Length L Ch R = 1 ,88682.5 ,601.5,579.2,555.4
XS GIS Cut Line= 3
     1746765.652      601210.154     1746858.011      601964.978
     1746894.152      602260.356
#Sta/Elev= 30
       0  761.61      39  754.68    58.5  750.58   126.7   734.8     195  718.14
   204.7   715.4   214.5  712.14   243.7  700.64   263.2  693.49   282.7  687.55
   331.5  674.72     352   668.3   360.7  665.19   370.5  662.96   380.2   662.4
     412   662.4   448.5  662.48   526.5  663.57   643.5  664.76   731.2  666.18
   808.4  667.84   923.6  669.65   933.2  670.18     962  673.18   990.8  675.46
  1000.4  676.52    1010  678.66  1019.6  681.66  1038.8  688.31    1058  695.34
#Mann= 3 , 0 , 0
       0      .1       0     352    .045       0     412     .06       0
Bank Sta=352,412
XS Rating Curve= 0 ,0
Exp/Cntr=0.3,0.1

Type RM Length L Ch R = 1 ,88103.3 ,331,409.4,456.7
XS GIS Cut Line= 2
     1746207.075      601604.393     1746633.724      602251.256
#Sta/Elev= 30
       0  737.29    68.7  723.53    88.3  718.87    98.1  716.08   127.5  706.78
   147.1  699.88   196.2   679.8   215.8  672.43   236.9  665.01   245.2  662.28
     255  660.06   264.8  659.32   274.6  659.54   296.9  661.89   304.1  662.19
   333.5  661.56   362.9  661.52     461  663.38   490.4  664.19   519.9  664.48
   559.1   666.9   627.8     670   637.6  671.36   647.4  673.67   657.2  674.76
   676.8  673.45   686.6  673.33     716  674.47   735.7  676.49   774.9  677.46
#Mann= 3 , 0 , 0
       0      .1       0   236.9    .045       0   296.9     .06       0
Bank Sta=236.9,296.9
XS Rating Curve= 0 ,0
Exp/Cntr=0.3,0.1

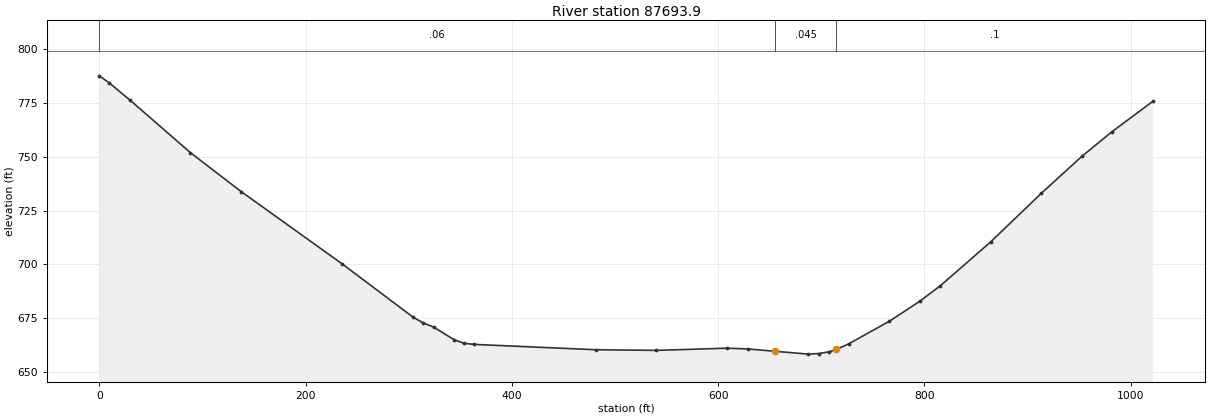
Type RM Length L Ch R = 1 ,87693.9 ,597.9,578.5,585
XS GIS Cut Line= 2
     1746212.135      601472.064     1746048.257      602480.375
#Sta/Elev= 30
       0  787.45     9.8   784.1    29.5  776.29    88.4   751.8   137.5  733.81
   235.7   700.2   304.5  675.46   314.3  672.87   324.1     671   343.8  665.17
   353.6  663.48   363.4  662.95   481.3  660.48   540.2  660.18     609   661.2
   628.6  660.85   654.8  659.77   687.6  658.44   697.4  658.71   707.2  659.46
   714.8  660.62   726.9  663.27   766.2  673.71   795.6  682.96   815.3  690.04
   864.4   710.5   913.5  733.01   952.8  750.13   982.2  761.62  1021.5  775.59
#Mann= 3 , 0 , 0
       0     .06       0   654.8    .045       0   714.8      .1       0
Bank Sta=654.8,714.8
XS Rating Curve= 0 ,0
Exp/Cntr=0.3,0.1