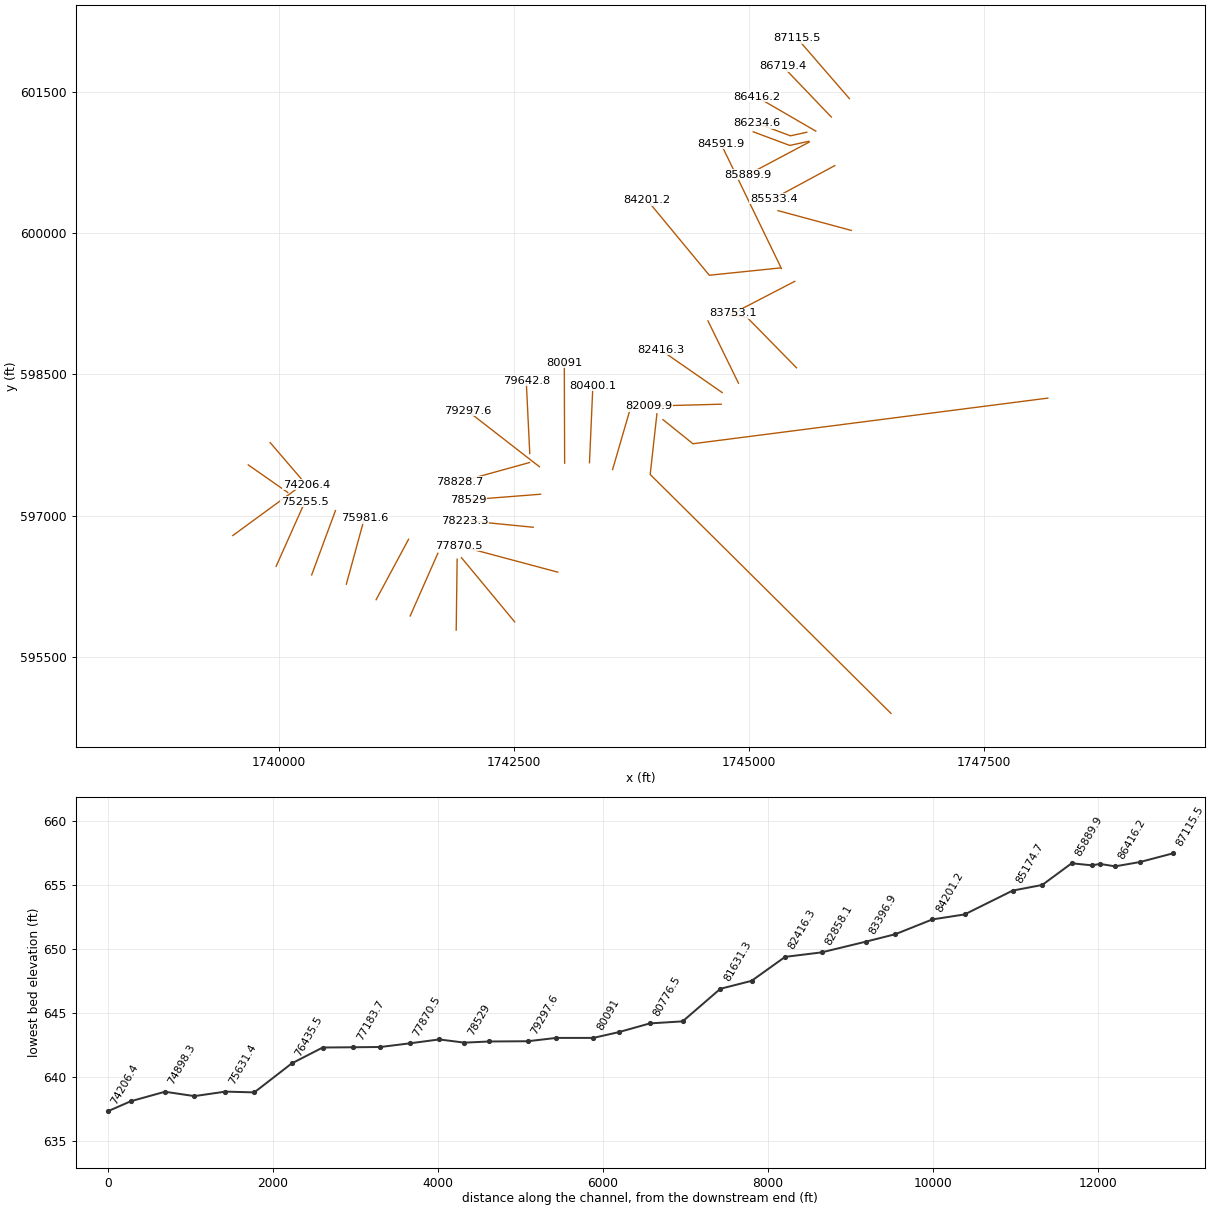
HEC-RAS study EightenmC1.prj: EightenmC1

--- EightenmC1.g01 (geometry) --- (continued)

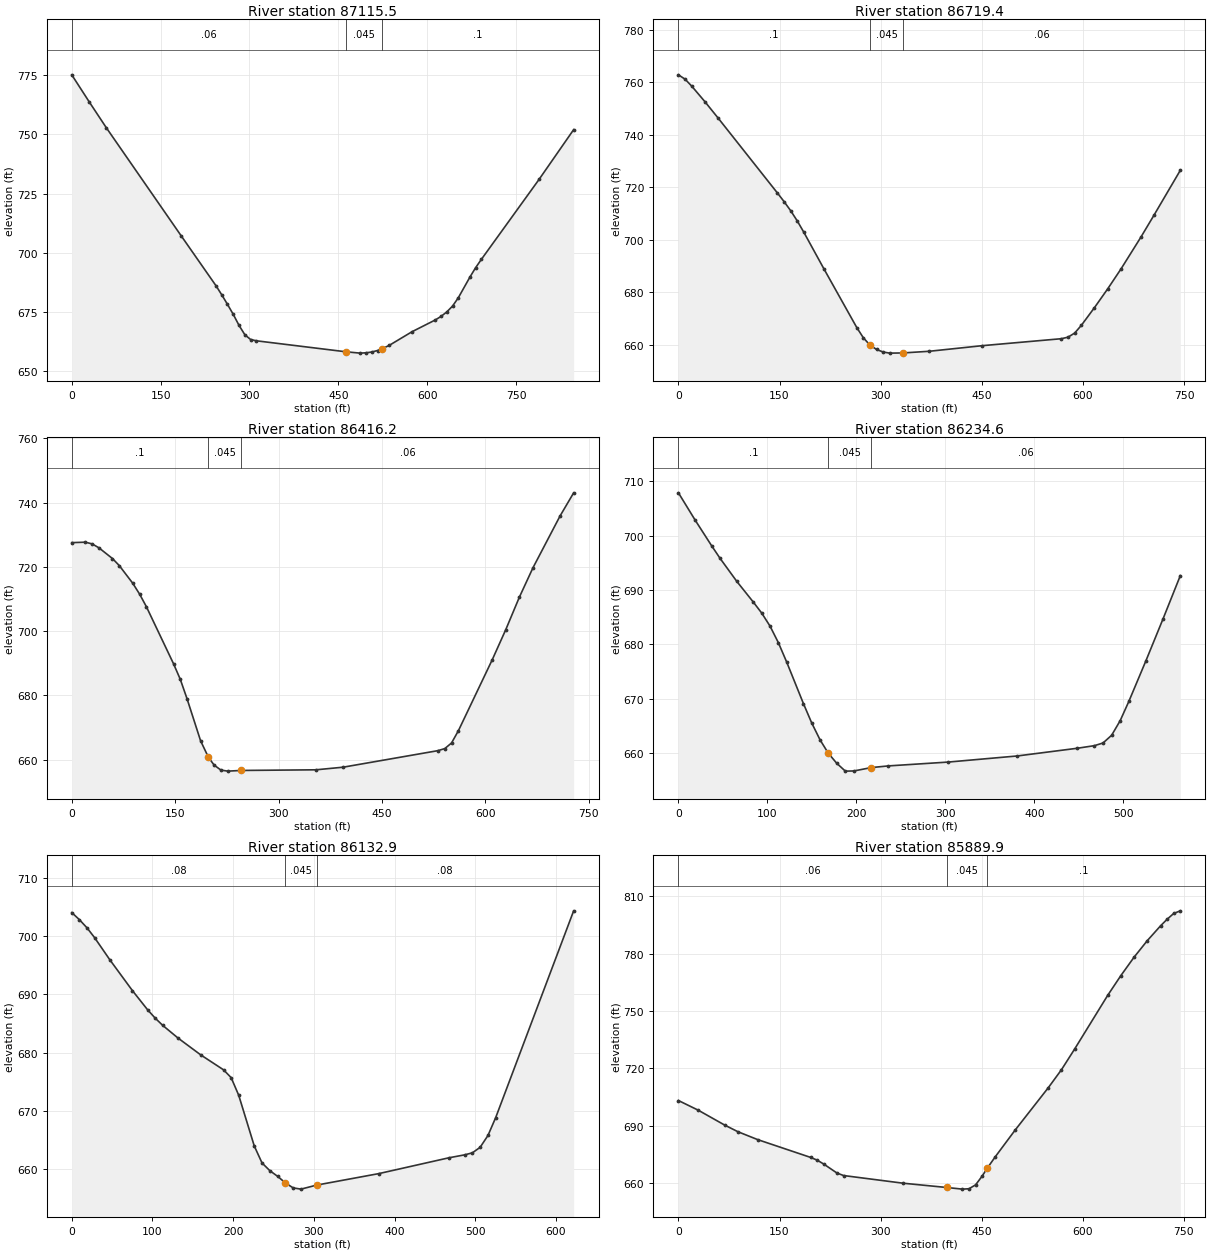
Type RM Length L Ch R = 1 ,87115.5 ,394.4,396.1,361.2
XS GIS Cut Line= 2
     1746067.619      601428.738     1745512.726      602069.004
#Sta/Elev= 30
       0  775.23    29.2  763.89    58.4  752.82     185  707.01   243.5  685.99
   253.2  682.15   262.9   678.1   272.7  673.85   282.4   669.2   292.2  665.26
   301.9  663.23   311.6  662.69   463.4  658.02   486.9  657.47   496.7  657.61
   506.4  657.93   516.2  658.58   523.4  659.25   535.6   660.7   574.6  666.55
   613.5  671.48   623.3  672.99     633  674.88   642.8  677.36   652.5  680.86
     672  689.57   681.7  693.58   691.4  697.11   788.8  730.94   847.3  752.04
#Mann= 3 , 0 , 0
       0     .06       0   463.4    .045       0   523.4      .1       0
Bank Sta=463.4,523.4
XS Rating Curve= 0 ,0
Exp/Cntr=0.3,0.1

Type RM Length L Ch R = 1 ,86719.4 ,287.7,303.1,355.6
XS GIS Cut Line= 2
     1745875.557      601232.912     1745360.639      601770.531
#Sta/Elev= 30
       0  762.89     9.8  761.24    19.6  758.62    39.2  752.68    58.8  746.43
   146.9  717.82   156.7  714.56   166.5  711.09   176.3  707.18   186.1  702.83
   215.5  689.06   264.5  666.56   274.3  662.64   284.1  659.86   293.8  658.21
   303.6  657.22   313.4   656.8     333  656.87   372.2  657.51   450.6  659.64
   568.1   662.3   577.9  662.89   587.7  664.45   597.5  667.36   617.1  674.16
   636.7  681.31   656.3  688.85   685.7  700.92   705.2  709.32   744.4   726.5
#Mann= 3 , 0 , 0
       0      .1       0   284.1    .045       0     333     .06       0
Bank Sta=284.1,333
XS Rating Curve= 0 ,0
Exp/Cntr=0.3,0.1

Type RM Length L Ch R = 1 ,86416.2 ,155.6,181.7,189.3
XS GIS Cut Line= 2
      1745710.41      601083.467     1745080.481      601448.398
#Sta/Elev= 30
       0  727.52    19.7  727.66    29.5  727.13    39.4  725.91      59  722.58
    68.9  720.39    88.5  714.88    98.4  711.51   108.2  707.62   147.6  689.86
   157.4  685.02   167.2  678.98   186.9  665.88   198.3  660.73   206.6  658.32
   216.4  656.78   226.3  656.46     246  656.67   354.2  656.87   393.5  657.68
   531.2  662.83   541.1  663.47   550.9  665.22   560.8  669.02     610  691.14
   629.6  700.49   649.3  710.58     669  719.71   708.3  735.82     728  743.01
#Mann= 3 , 0 , 0
       0      .1       0   198.3    .045       0     246     .06       0
Bank Sta=198.3,246
XS Rating Curve= 0 ,0
Exp/Cntr=0.3,0.1

Type RM Length L Ch R = 1 ,86234.6 ,119.5,101.7,102.4
XS GIS Cut Line= 3
     1745614.927      601071.315     1745441.041      601033.529
     1745079.301      601168.681
#Sta/Elev= 30
       0  707.88    18.7  702.88    37.5  698.09    46.8  695.82    65.6  691.58
    84.3  687.74    93.6  685.75     103  683.33   112.4  680.27   121.8  676.68
   140.5  669.08   149.8  665.52   159.2   662.4   168.4  659.96   177.9   658.1
   187.6  656.65   197.2  656.68   216.6   657.3   235.9  657.61   303.4  658.32
   380.7  659.44   448.3  660.86   467.6  661.34   477.2  661.83   486.9  663.25
   496.5  665.94   506.2  669.47   525.5  676.99   544.8  684.73   564.1  692.64
#Mann= 3 , 0 , 0
       0      .1       0   168.4    .045       0   216.6     .06       0
Bank Sta=168.4,216.6
XS Rating Curve= 0 ,0
Exp/Cntr=0.3,0.1

Type RM Length L Ch R = 1 ,86132.9 ,202.3,243,281.5
XS GIS Cut Line= 3
     1745635.833      600975.106      1745433.68      600931.177
     1745044.844      601076.453
#Sta/Elev= 30
       0  704.08     9.4  702.87    18.8  701.47    28.2  699.79      47     696
    75.2  690.66      94  687.37   103.4  685.93   112.8  684.68   131.6  682.52
   159.8  679.62   188.1  677.05   197.5  675.71   206.9  672.68   226.2  663.95
   235.8  661.04   245.5  659.71   255.1  658.74   264.8  657.61   274.4  656.75
   284.1  656.54   303.4  657.23   380.6  659.21   467.5  661.93   486.8  662.43
   496.5  662.78   506.1  663.73   515.8  665.76   525.4  668.84     622  704.38
#Mann= 3 , 0 , 0
       0     .08       0   264.8    .045       0   303.4     .08       0
Bank Sta=264.8,303.4
XS Rating Curve= 0 ,0
Exp/Cntr=0.3,0.1

Type RM Length L Ch R = 1 ,85889.9 ,355.2,356.5,355.8
XS GIS Cut Line= 2
      1745641.19      600967.123     1744983.162       600618.27
#Sta/Elev= 30
       0  703.08    29.4  698.02    68.6  690.24    88.2  686.76   117.6  682.62
     196  673.32   205.8  671.89   215.6  669.84   235.2  665.14     245  663.82
   333.2  659.81     398  657.56   421.4   656.7   431.2  656.89     441  658.94
   450.8  663.56     458  667.51   470.4  673.74   499.8  687.67   548.8  709.75
   568.4   719.2     588  730.05     637  758.12   656.6  768.49   676.2  778.13
   695.8  786.78   715.4   794.5   725.2  797.97     735     801   744.8  802.38
#Mann= 3 , 0 , 0
       0     .06       0     398    .045       0     458      .1       0
Bank Sta=398,458
XS Rating Curve= 0 ,0
Exp/Cntr=0.3,0.1

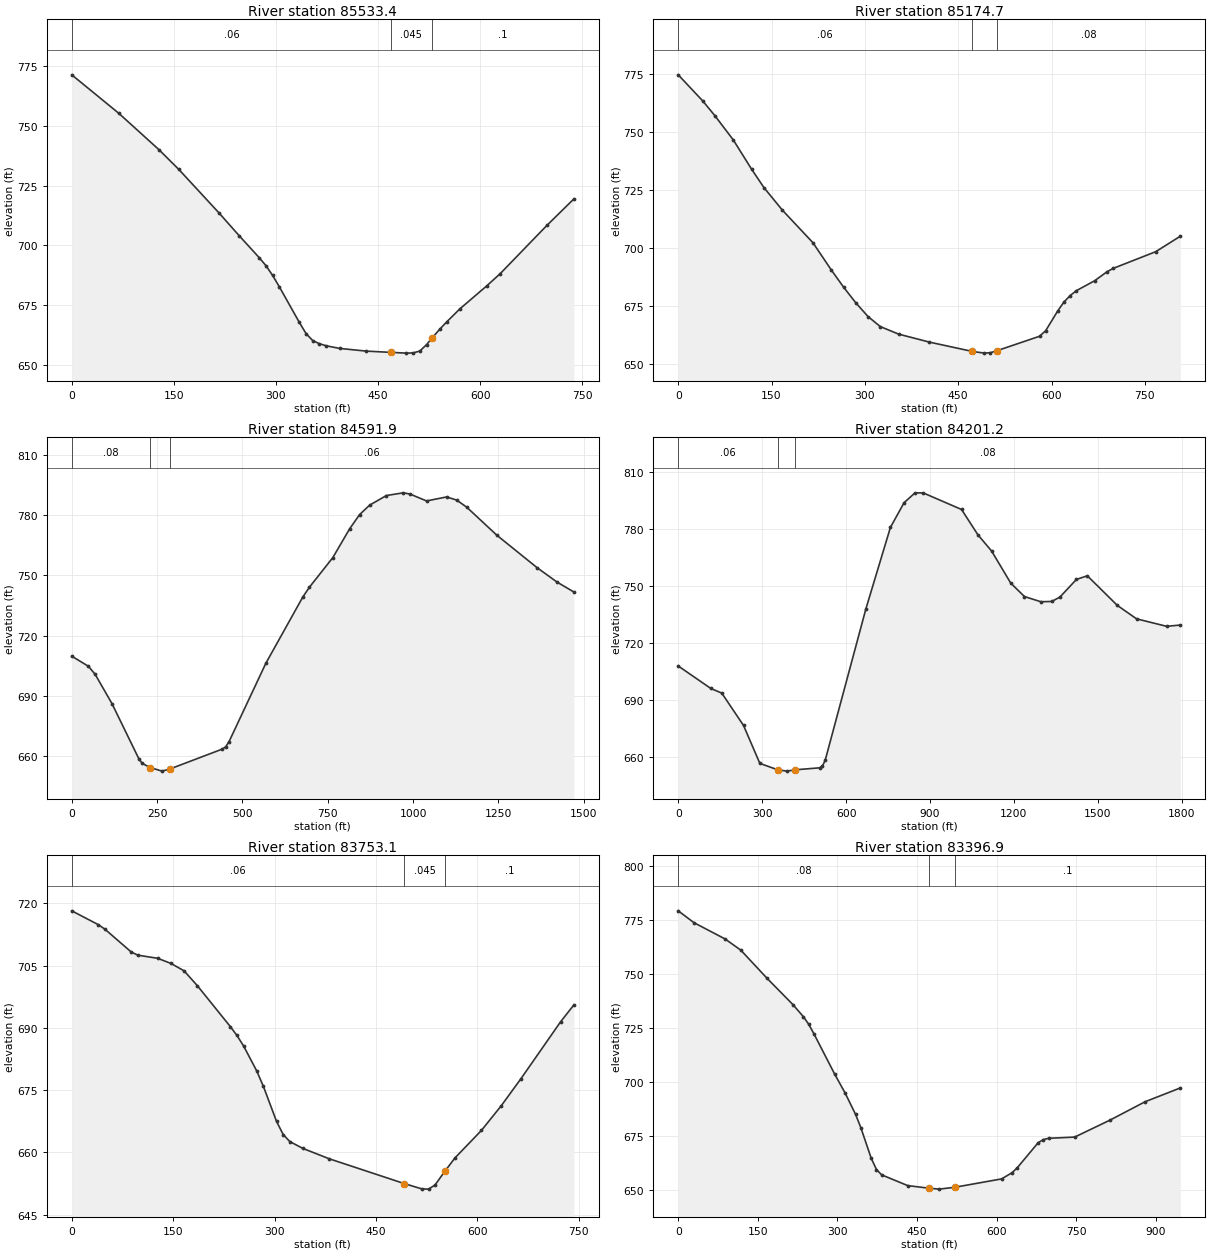
Type RM Length L Ch R = 1 ,85533.4 ,394.6,358.7,321.9
XS GIS Cut Line= 2
     1745912.788      600717.316     1745263.342      600367.312
#Sta/Elev= 30
       0  771.22    68.9  755.21   127.9  740.02   157.4  731.69   216.4  713.54
   245.9  704.08   275.4  694.89   285.3  691.56   295.1  687.47   304.9  682.77
   334.4  667.85   344.3  663.17   354.1  660.24     364  658.93   373.8  658.09
   393.5  656.98   432.8  655.85     469  655.32   491.8  655.01   501.7   655.1
   511.5  655.89   521.4  658.57     529  661.19     541  665.07   550.9  668.03
   570.5  673.54   609.9  683.12   629.6   688.2   698.4   708.4   737.8   719.4
#Mann= 3 , 0 , 0
       0     .06       0     469    .045       0     529      .1       0
Bank Sta=469,529
XS Rating Curve= 0 ,0
Exp/Cntr=0.3,0.1

Type RM Length L Ch R = 1 ,85174.7 ,620.3,582.9,544.7
XS GIS Cut Line= 2
     1746087.438      600028.668     1745308.392      600238.742
#Sta/Elev= 30
       0  774.66    39.4   763.4      59  756.99    88.6  746.52   118.1  733.86
   137.8  725.98   167.3  716.29   216.5  702.21     246  690.45   265.7  683.06
   285.4  676.27     305  670.36   324.7  666.03   354.2  662.77   403.4  659.34
   472.3  655.32     492  654.57   501.8  654.76   511.7  655.57   580.6  661.84
   590.4   664.2   610.1  672.86   619.9  676.62   629.8  679.39   639.6  681.48
   669.1  685.79   688.8  689.62   698.6  691.09   767.5  698.36   806.9  705.02
#Mann= 3 , 0 , 0
       0     .06       0   472.3    .045       0   511.7     .08       0
Bank Sta=472.3,511.7
XS Rating Curve= 0 ,0
Exp/Cntr=0.3,0.1

Type RM Length L Ch R = 1 ,84591.9 ,313.1,390.7,473.5
XS GIS Cut Line= 2
     1745344.627      599624.269     1744702.408      600948.025
#Sta/Elev= 30
       0  709.87      49  704.79    68.7  700.78   117.7  686.31   196.2  658.98
     206  656.64   229.1   654.5   264.8  652.71   289.1  653.88   441.4  663.68
   451.2  664.84     461  667.41   568.9  706.37   676.8  739.18   696.4  744.12
   765.1  758.87   814.1  773.11   843.6  780.25     873  784.93     922  789.69
   971.1  791.04   990.7  790.46  1039.7  787.01  1098.6     789    1128  787.42
  1157.4  783.91  1245.7  769.96  1363.4  753.86  1422.3  746.65  1471.3  741.76
#Mann= 3 , 0 , 0
       0     .08       0   229.1    .045       0   289.1     .06       0
Bank Sta=229.1,289.1
XS Rating Curve= 0 ,0
Exp/Cntr=0.3,0.1

Type RM Length L Ch R = 1 ,84201.2 ,444.4,448,436.4
XS GIS Cut Line= 3
     1745332.807      599630.067     1744578.139        599552.4
     1743917.501      600350.555
#Sta/Elev= 30
       0   707.8   116.7  695.92   155.6   693.5   233.4  676.42   291.8  656.39
   356.8  652.97     389  652.32   416.8     653   505.8  654.07   515.5  655.02
   525.2  657.98   671.1  738.09   758.6  780.96   807.5     794   846.6  799.17
     876  799.11  1012.8  790.38  1071.4     777  1120.3  768.44  1188.7  751.52
  1237.6  744.44  1296.2   741.7  1335.4  741.85  1364.7   744.2  1423.3  753.46
  1462.4  755.39  1569.9  739.74  1638.4  732.68  1745.9  728.73  1794.8   729.4
#Mann= 3 , 0 , 0
       0     .06       0   356.8    .045       0   416.8     .08       0
Bank Sta=356.8,416.8
XS Rating Curve= 0 ,0
Exp/Cntr=0.3,0.1

Type RM Length L Ch R = 1 ,83753.1 ,421.1,356.2,286.3
XS GIS Cut Line= 2
     1745486.783      599487.646     1744827.369       599146.05
#Sta/Elev= 30
       0  718.19    39.1  714.87    48.9  713.79    87.9  708.28    97.7  707.51
     127  706.76   146.6  705.53   166.1  703.74   185.7  700.17   234.5  690.32
   244.3  688.17   254.1  685.66   273.6  679.62   283.4  675.92   302.9  667.47
   312.7  664.32   322.5  662.62     342  660.96   381.1  658.46   491.7  652.51
   517.9  651.22   527.7  651.17   537.4  652.18   551.7  655.45   566.8  658.69
   605.8  665.29   635.2  671.24   664.5   677.8   723.1  691.49   742.6  695.52
#Mann= 3 , 0 , 0
       0     .06       0   491.7    .045       0   551.7      .1       0
Bank Sta=491.7,551.7
XS Rating Curve= 0 ,0
Exp/Cntr=0.3,0.1

Type RM Length L Ch R = 1 ,83396.9 ,542.3,538.8,532.7
XS GIS Cut Line= 3
     1745505.626       598569.05     1744982.239      599101.924
     1744785.923      599134.987
#Sta/Elev= 30
       0  779.33    29.5  773.87    88.4   766.3   117.9  761.14   167.1  748.18
   216.2  735.92   235.9  730.33   245.7  726.89   255.5  722.53   294.8  703.78
   314.5  695.02   334.2  685.13     344  679.08   363.6  664.87   373.5  659.66
   383.3  657.19   432.4  652.22   471.7  651.04   491.4  650.59   520.9  651.44
   609.3  655.32     629  658.19   638.8  660.48   678.1  672.05     688  673.52
   697.8   674.1   746.9  674.66   813.3  682.49   879.6  691.01     946   697.4
#Mann= 3 , 0 , 0
       0     .08       0   471.7    .045       0   520.9      .1       0
Bank Sta=471.7,520.9
XS Rating Curve= 0 ,0
Exp/Cntr=0.3,0.1

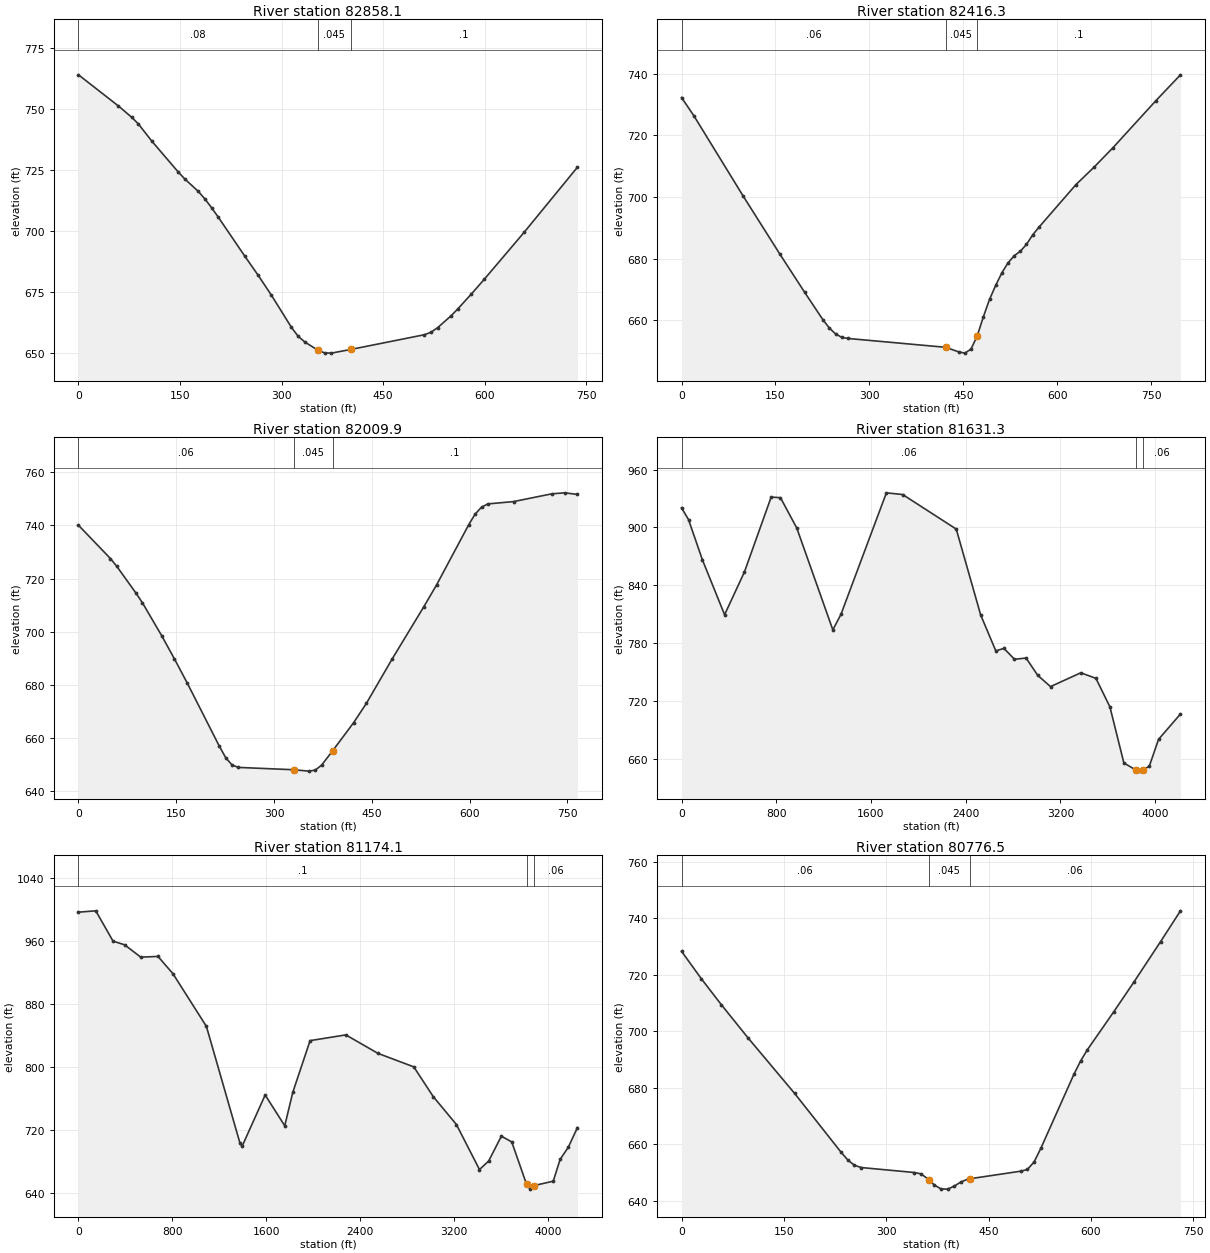
Type RM Length L Ch R = 1 ,82858.1 ,417.6,441.8,465.5
XS GIS Cut Line= 2
     1744888.277       598405.64      1744564.17      599067.434
#Sta/Elev= 30
       0  763.97      59  751.18    78.6  746.54    88.4  743.83   108.1  736.83
   147.4  724.06   157.2  721.18   176.9  716.14   186.7  713.04   196.5  709.46
   206.3  705.62   245.6  689.56   265.3  681.72   284.9  673.54   314.4  660.38
   324.2  656.73   334.1  654.35   353.7  650.92   363.5  649.85   373.4  649.75
     402  651.25   510.9   657.3   520.7  658.33   530.6  660.24   550.2  665.05
     560  667.84   579.7  673.84   599.3  680.06   658.3  699.38   736.9  726.05
#Mann= 3 , 0 , 0
       0     .08       0   353.7    .045       0     402      .1       0
Bank Sta=353.7,402
XS Rating Curve= 0 ,0
Exp/Cntr=0.3,0.1

Type RM Length L Ch R = 1 ,82416.3 ,376.7,406.4,433.9
XS GIS Cut Line= 2
     1744715.401       598305.87     1744060.815      598759.585
#Sta/Elev= 30
       0  732.26    19.7  726.35    98.3  700.35   157.3   681.4   196.7  669.07
   226.2  660.07     236  657.54   245.8  655.65   255.6  654.54   265.5  654.16
   421.5  651.29   442.5   649.8   452.3   649.4   462.1  650.73     472  654.99
   481.8  661.17   491.6   666.8   501.5  671.37   511.3  675.41   521.1  678.65
     531  680.96   540.8  682.42   550.6  684.65   560.5  687.72   570.3  690.17
   629.3  703.96   658.8  709.75   688.3  715.91   757.1  731.22   796.4  739.61
#Mann= 3 , 0 , 0
       0     .06       0   421.5    .045       0     472      .1       0
Bank Sta=421.5,472
XS Rating Curve= 0 ,0
Exp/Cntr=0.3,0.1

Type RM Length L Ch R = 1 ,82009.9 ,412.6,378.6,340.6
XS GIS Cut Line= 2
     1744704.539      598182.451     1743939.192      598162.259
#Sta/Elev= 30
       0  740.08    49.1  727.53    58.9  724.58    88.3  714.51    98.2  710.86
   127.6  698.54   147.2  689.79   166.9  680.68   215.9  657.02   225.8  652.63
   235.6  649.84   245.4  648.93   330.2  648.05   353.4  647.53   363.2   647.9
     373  649.77   390.2  655.26   422.1  665.75   441.7  673.02     481  689.63
     530  709.46   549.7  717.74   598.8   740.3   608.6  744.27   618.4  746.89
   628.2  748.12   667.5  748.99   726.4  751.92     746  752.29   765.6   751.7
#Mann= 3 , 0 , 0
       0     .06       0   330.2    .045       0   390.2      .1       0
Bank Sta=330.2,390.2
XS Rating Curve= 0 ,0
Exp/Cntr=0.3,0.1

Type RM Length L Ch R = 1 ,81631.3 ,500.6,457.3,416.3
XS GIS Cut Line= 3
     1748177.237      598247.108     1744404.187      597762.433
     1744085.314      598018.827
#Sta/Elev= 30
       0  920.31      59  908.13   176.9  866.12   363.7  809.32   530.8  853.59
   756.9  931.43   835.5  930.85   973.1  899.37  1277.8  793.58  1346.6  809.78
    1730  935.88  1867.6  934.09  2319.8  898.24  2526.2  809.04    2654  771.75
  2722.8  774.38  2811.3  763.06  2909.6  764.33  3007.9  746.37    3116  734.68
  3371.6  749.01  3499.3  743.27  3617.3  713.68  3735.2  655.45  3838.1  647.97
  3872.2  646.91  3898.1  648.14  3950.2  652.11  4028.1   679.9  4213.2  706.23
#Mann= 3 , 0 , 0
       0     .06       0  3838.1    .045       0  3898.1     .06       0
Bank Sta=3838.1,3898.1
XS Rating Curve= 0 ,0
Exp/Cntr=0.3,0.1

Type RM Length L Ch R = 1 ,81174.1 ,394.5,397.5,390.6
XS GIS Cut Line= 3
     1746509.626      594898.161      1743949.76      597436.109
     1744021.246      598080.652
#Sta/Elev= 30
       0  996.45   147.3  998.14   294.7  959.56   392.9  954.98   530.4  939.28
   677.7  940.18   805.4  918.17  1090.3  851.28  1375.1  703.57  1394.8  698.87
  1591.2  764.05  1758.2  724.88  1826.9  767.48  1974.2  833.13  2278.7  840.44
  2553.8  816.88  2858.2   799.8  3025.2  761.74  3221.7   726.5  3418.1  669.24
  3496.7  680.14  3604.7  711.67  3693.2  704.41  3819.5  650.46  3850.4  644.37
  3879.5  648.75  4046.9  654.47  4105.8  682.28  4174.6  697.42  4253.2  722.61
#Mann= 3 , 0 , 0
       0      .1       0  3819.5    .045       0  3879.5     .06       0
Bank Sta=3819.5,3879.5
XS Rating Curve= 0 ,0
Exp/Cntr=0.3,0.1

Type RM Length L Ch R = 1 ,80776.5 ,375.9,376.5,387
XS GIS Cut Line= 2
     1743550.098      597488.384     1743754.099      598190.681
#Sta/Elev= 30
       0  728.34    29.2  718.57    58.5   709.4    97.5   697.7   165.8  678.06
     234  657.22   243.8   654.5   253.5  652.64   263.3  651.85   341.3  650.09
     351  649.61   362.4  647.59   370.5  645.68   380.3  644.29     390  644.21
   399.8  645.28   409.5  646.74   419.3  647.72   422.4  647.87   497.3  650.56
     507  651.17   516.8  653.84   526.6  658.62   575.3  684.91   585.1   689.6
   594.8  693.49   633.8  707.03   663.1  717.47   702.1  731.73   731.3  742.64
#Mann= 3 , 0 , 0
       0     .06       0   362.4    .045       0   422.4     .06       0
Bank Sta=362.4,422.4
XS Rating Curve= 0 ,0
Exp/Cntr=0.3,0.1

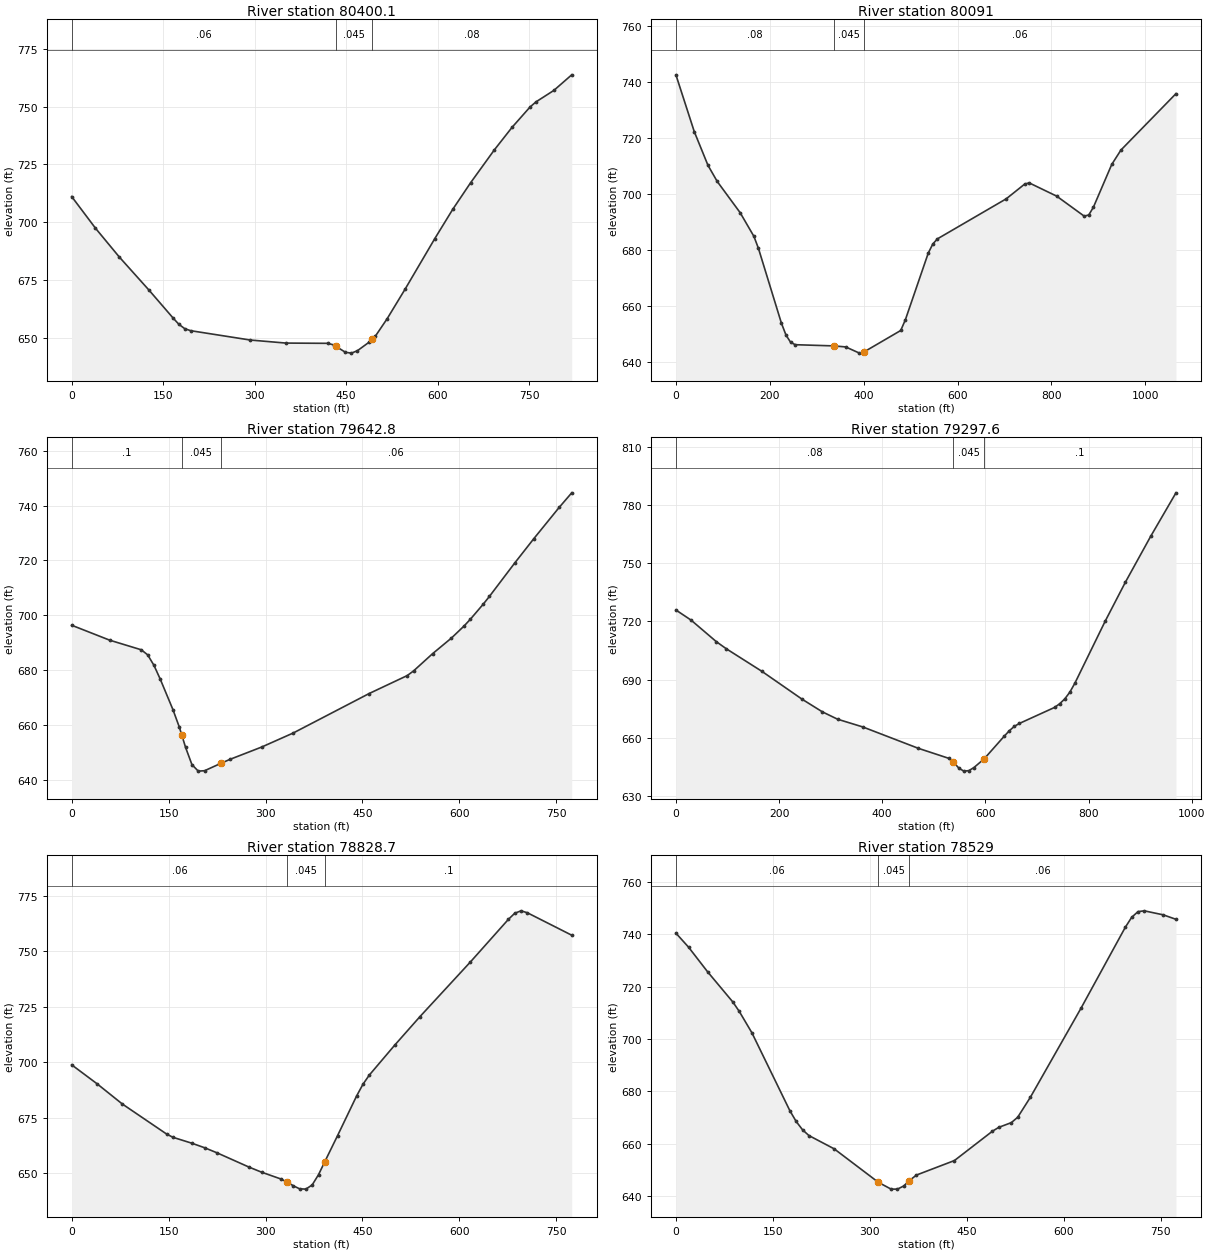
Type RM Length L Ch R = 1 ,80400.1 ,306.6,309,311.3
XS GIS Cut Line= 3
     1743304.132      597560.479     1743306.716       597618.92
     1743340.357      598379.744
#Sta/Elev= 30
       0  711.16      39   697.5      78  685.08   126.8  670.75   165.9  658.82
   175.7  656.01   185.4   654.1   195.2  653.22   292.8  649.19   351.4  647.87
   419.8  647.76   429.5   647.1   433.2  646.48     449  643.89   458.8  643.53
   468.6  644.57   488.1  648.31   493.2   649.6   497.9  650.79   517.4  658.39
   546.7   671.1   595.5  692.98   624.8  705.57   654.1  717.06   693.1  731.28
   722.4   741.1   751.7  749.82   761.5  752.05   790.8     757   820.1  763.73
#Mann= 3 , 0 , 0
       0     .06       0   433.2    .045       0   493.2     .08       0
Bank Sta=433.2,493.2
XS Rating Curve= 0 ,0
Exp/Cntr=0.3,0.1

Type RM Length L Ch R = 1 ,80091   ,442.3,448.3,450.8
XS GIS Cut Line= 2
     1743040.095      597556.023     1743036.337      598621.348
#Sta/Elev= 30
       0  742.45    39.1  722.17    68.4   710.1      88  704.38   136.8  693.24
   166.2  684.76   175.9  680.44   224.8  653.76   234.6  649.49   244.3  646.97
   254.1  646.09   336.4  645.66   361.6   645.3     391  643.08   400.7  643.51
   478.9  651.16   488.7  654.93   537.6  678.81   547.3  682.05   557.1  683.88
   703.7  698.18   742.8  703.41   752.6  703.87   811.2  699.13   869.9  691.98
   879.6  692.43   889.4  695.18   928.5  710.46     948  715.58  1065.3  735.73
#Mann= 3 , 0 , 0
       0     .08       0   336.4    .045       0   400.7     .06       0
Bank Sta=336.4,400.7
XS Rating Curve= 0 ,0
Exp/Cntr=0.3,0.1

Type RM Length L Ch R = 1 ,79642.8 ,304.9,345.2,385.5
XS GIS Cut Line= 2
      1742669.37      597658.809     1742631.673      598431.744
#Sta/Elev= 30
       0  696.33    58.8  690.88   107.8  687.36   117.6  685.52   127.3  681.71
   137.1  676.64   156.7  665.53   166.5   659.2   170.5  656.15   176.3  651.72
   186.1  645.46   195.9  643.08   205.7  643.23   230.5  645.88   244.9  647.37
   293.9  651.86   342.8  656.99   460.4  671.41   519.2  677.95     529  679.64
   558.4  685.93   587.7  691.66   607.3  696.07   617.1  698.56   636.7  703.97
   646.5  706.87   685.7  719.07   715.1  727.92   754.3  739.31   773.8  744.66
#Mann= 3 , 0 , 0
       0      .1       0   170.5    .045       0   230.5     .06       0
Bank Sta=170.5,230.5
XS Rating Curve= 0 ,0
Exp/Cntr=0.3,0.1

Type RM Length L Ch R = 1 ,79297.6 ,427.9,468.9,509.9
XS GIS Cut Line= 2
     1742772.117      597518.129     1742005.996      598112.348
#Sta/Elev= 30
       0  725.85    29.4  720.63    78.4  709.52    97.9  705.84   166.5  694.28
   244.8  679.85     284  673.36   313.4  669.58   362.4  665.58   470.1  654.57
   528.8  649.44   537.6  647.63   548.4  644.43   558.2  642.82     568  643.07
   577.8  644.65   597.6  649.12   636.6  660.82   646.4  663.61   656.2  665.89
     666  667.39   734.5  675.68   744.3  677.58   754.1  680.06   763.9  683.54
   773.7  688.19   832.4  720.11   871.6  740.21   920.6  763.82   969.6  786.22
#Mann= 3 , 0 , 0
       0     .08       0   537.6    .045       0   597.6      .1       0
Bank Sta=537.6,597.6
XS Rating Curve= 0 ,0
Exp/Cntr=0.3,0.1

Type RM Length L Ch R = 1 ,78828.7 ,308.3,299.7,289.7
XS GIS Cut Line= 2
     1742667.088      597562.814     1741921.099      597357.166
#Sta/Elev= 30
       0  698.85    39.2  690.32    78.4  681.18   146.9  667.64   156.7  666.17
   186.1  663.49   205.7  661.46   225.3  659.12   274.3  652.75   293.8  650.45
   323.2  647.43   333.8  645.95   342.8  644.34   352.6  642.95   362.4   642.8
   372.2   644.7     382  649.33   391.8  655.23   411.4  666.89   440.8  684.73
   450.6  690.01   460.4  694.16   499.6  707.62   538.7   720.5   617.1  745.25
   675.9  764.47   685.7   767.2   695.4  768.28   705.2   767.4   773.8  757.29
#Mann= 3 , 0 , 0
       0     .06       0   333.8    .045       0   391.8      .1       0
Bank Sta=333.8,391.8
XS Rating Curve= 0 ,0
Exp/Cntr=0.3,0.1

Type RM Length L Ch R = 1 ,78529   ,313.5,305.7,299.2
XS GIS Cut Line= 2
      1742784.05      597226.118     1742012.578      597165.944
#Sta/Elev= 30
       0  740.43    19.6  735.06      49  725.68    88.2  714.11      98  710.56
   117.5  702.43   176.3  672.66   186.1  668.53   195.9  665.38   205.7  663.18
   244.9  658.09   313.4  645.29     333  642.71   342.8  642.71   352.6  643.92
   360.6  645.84   372.2  648.08     431  653.62   489.8  664.82   499.6  666.29
   519.1   668.1   528.9  670.15   548.5  677.77   626.9  711.79   695.4  742.66
   705.2  746.44     715  748.63   724.8  748.94   754.2   747.4   773.8   745.7
#Mann= 3 , 0 , 0
       0     .06       0   313.4    .045       0   360.6     .06       0
Bank Sta=313.4,360.6
XS Rating Curve= 0 ,0
Exp/Cntr=0.3,0.1

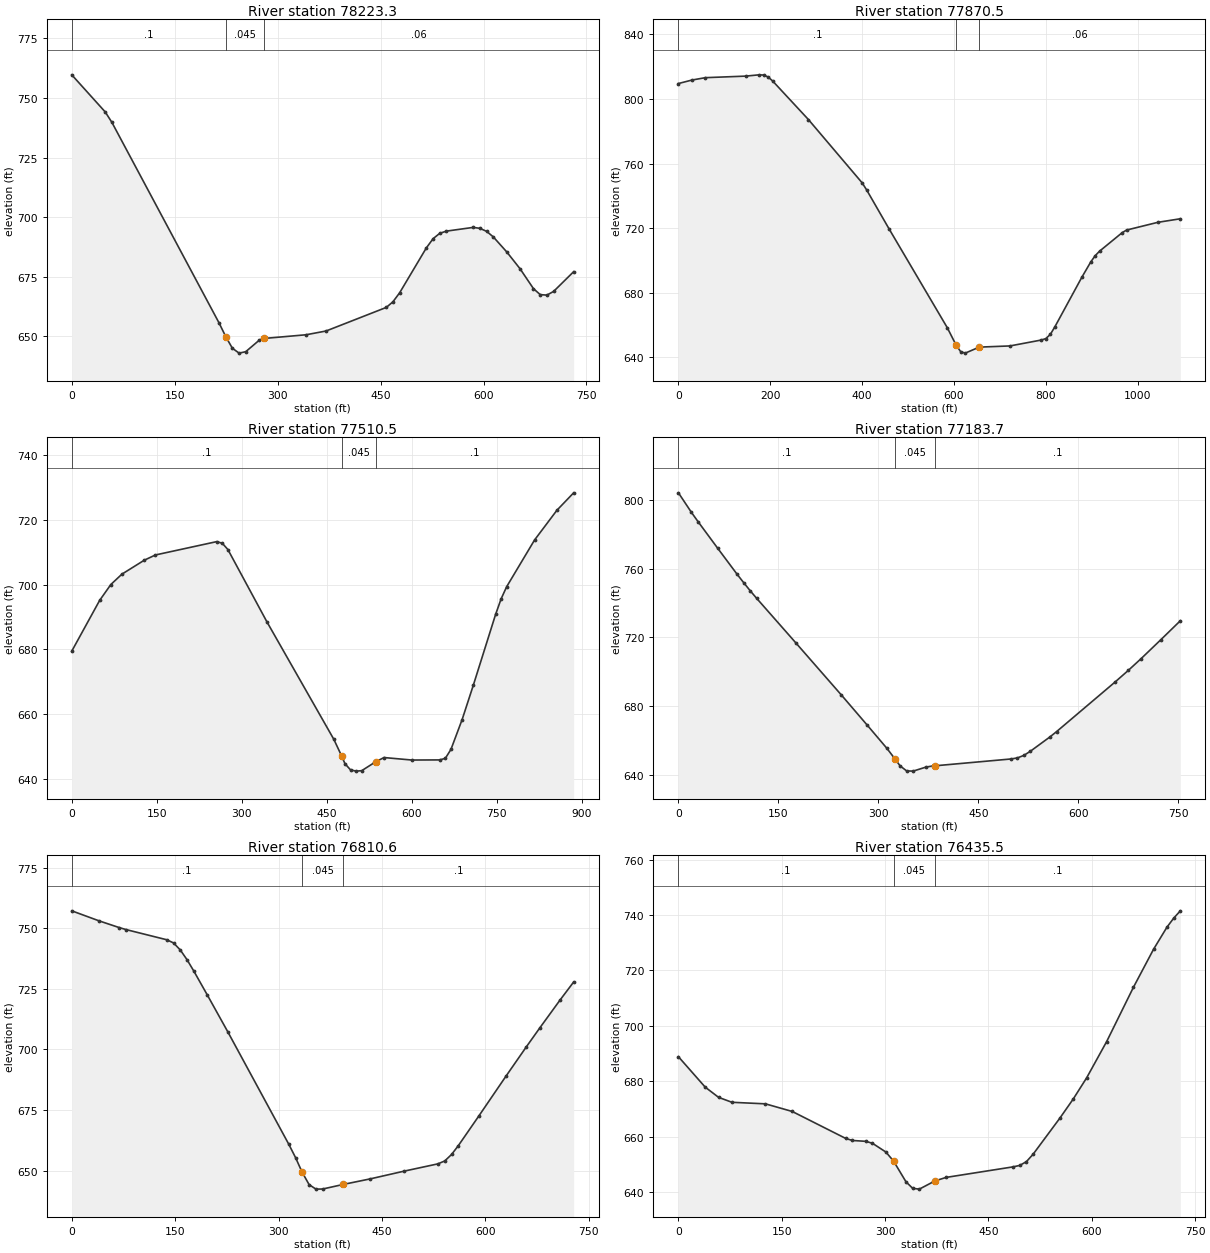
Type RM Length L Ch R = 1 ,78223.3 ,360.2,352.8,345.4
XS GIS Cut Line= 2
     1742705.767       596875.26     1741977.985      596947.045
#Sta/Elev= 30
       0  759.74    48.8  744.15    58.5  739.78   214.5   655.7   224.3  649.93
     234  645.02   243.8  642.96   253.5  643.56     273  648.34   280.3  649.12
   341.3  650.66   370.5  652.24   458.3  662.14     468   664.5   477.8  668.29
   516.8  687.17   526.6  691.01   536.3  693.25     546  694.16     585  695.72
   594.8  695.32   604.6  694.04   614.3  691.71   633.8  685.44   653.3  678.33
   672.8     670   682.6  667.51   692.3   667.3   702.1  668.85   731.3  677.13
#Mann= 3 , 0 , 0
       0      .1       0   224.3    .045       0   280.3     .06       0
Bank Sta=224.3,280.3
XS Rating Curve= 0 ,0
Exp/Cntr=0.3,0.1

Type RM Length L Ch R = 1 ,77870.5 ,388.1,360,331.9
XS GIS Cut Line= 2
     1742967.063      596398.456     1741911.073      596680.307
#Sta/Elev= 30
       0  809.61    29.3  811.76    58.6  813.24   146.4   814.2   175.6     815
   185.4  814.86   195.2  813.69   204.9  811.26     283  787.33   400.1   748.1
   409.9  743.72   458.6  719.65   585.5   658.4     605  647.47   614.8  643.52
   624.6  642.66   655.1  646.38   722.1  647.12   790.4  650.78   800.2  651.67
     810   654.3   819.7   658.9   878.3  689.53   897.8  699.05   907.5  702.97
   917.3  705.84   966.1   717.2   975.8  718.86  1044.2  723.67    1093  725.86
#Mann= 3 , 0 , 0
       0      .1       0     605    .045       0   655.1     .06       0
Bank Sta=605,655.1
XS Rating Curve= 0 ,0
Exp/Cntr=0.3,0.1

Type RM Length L Ch R = 1 ,77510.5 ,358.6,326.8,294.9
XS GIS Cut Line= 2
     1742508.638      595870.481     1741943.398      596551.826
#Sta/Elev= 30
       0  679.48    49.2  695.18    68.9  700.08    88.5   703.3   127.9  707.61
   147.6  709.23   255.8  713.36   265.6  712.84   275.4  710.91   344.3  688.53
   462.3   652.2     476  647.07     482  644.65   491.8  642.75   501.7  642.37
   511.5  642.51     536  645.25   550.8  646.57     600   645.8   649.2  645.84
     659  646.33   668.9   649.1   688.6  658.32   708.2  668.86   747.6  690.82
   757.4  695.67   767.2  699.43   816.4  713.87   855.8  723.06   885.3  728.45
#Mann= 3 , 0 , 0
       0      .1       0     476    .045       0     536      .1       0
Bank Sta=476,536
XS Rating Curve= 0 ,0
Exp/Cntr=0.3,0.1

Type RM Length L Ch R = 1 ,77183.7 ,391.4,373.1,354.9
XS GIS Cut Line= 2
     1741887.175       595783.25     1741897.159      596536.389
#Sta/Elev= 30
       0  803.94    19.6  792.53    29.4  787.23    58.7  771.87      88  756.68
    97.8  751.83   107.6  747.13   117.4  742.68   176.1  716.86   244.6  686.52
   283.7  668.88     313  655.51     325   649.4   332.6  645.43   342.4  642.49
   352.2  642.35   371.7  644.72   381.5  645.33     385  645.44   498.9   649.4
   508.7  650.02   518.4  651.49   528.2   653.9   557.6  662.23   567.4  665.26
   655.4  694.13     675  700.79   694.5  707.72   723.9  718.63   753.2  729.65
#Mann= 3 , 0 , 0
       0      .1       0     325    .045       0     385      .1       0
Bank Sta=325,385
XS Rating Curve= 0 ,0
Exp/Cntr=0.3,0.1

Type RM Length L Ch R = 1 ,76810.6 ,378.6,375.1,371.6
XS GIS Cut Line= 2
     1741397.742      595932.797     1741691.973      596598.689
#Sta/Elev= 30
       0  757.25    39.4  753.13    68.9  750.33    78.7  749.51   137.7  745.31
   147.6     744   157.4   741.1   167.2  737.07   177.1  732.35   196.8  722.41
   226.3  707.31   314.8  660.86   324.6  655.36     334  649.41   344.3  644.18
   354.2  642.33     364  642.38     394  644.28   432.9  646.56     482  649.75
   531.2  652.77   541.1  653.98   550.9  656.63   560.8  660.31   590.3  672.46
   629.6  688.87   659.1  700.97   678.8  708.86   708.3  720.42     728  727.86
#Mann= 3 , 0 , 0
       0      .1       0     334    .045       0     394      .1       0
Bank Sta=334,394
XS Rating Curve= 0 ,0
Exp/Cntr=0.3,0.1

Type RM Length L Ch R = 1 ,76435.5 ,443.5,453.8,463.9
XS GIS Cut Line= 2
     1741035.853      596105.764     1741380.835      596747.512
#Sta/Elev= 30
       0  688.87    38.9  677.89    58.3  674.21    77.7  672.43   126.3  671.87
   165.2  669.12   242.9  659.38   252.6  658.65     272  658.34   281.7  657.63
   301.2  654.47   312.3  651.21   330.3  643.75     340  641.38   349.7  641.09
   372.3  644.04   388.6  645.32   485.7  649.12   495.4  649.64   505.2  651.02
   514.9  653.69   553.7   666.7   573.2  673.64   592.6  681.25   621.7  694.36
   660.6  713.97   689.7  727.64   709.2  735.63   718.9  738.85   728.6  741.53
#Mann= 3 , 0 , 0
       0      .1       0   312.3    .045       0   372.3      .1       0
Bank Sta=312.3,372.3
XS Rating Curve= 0 ,0
Exp/Cntr=0.3,0.1

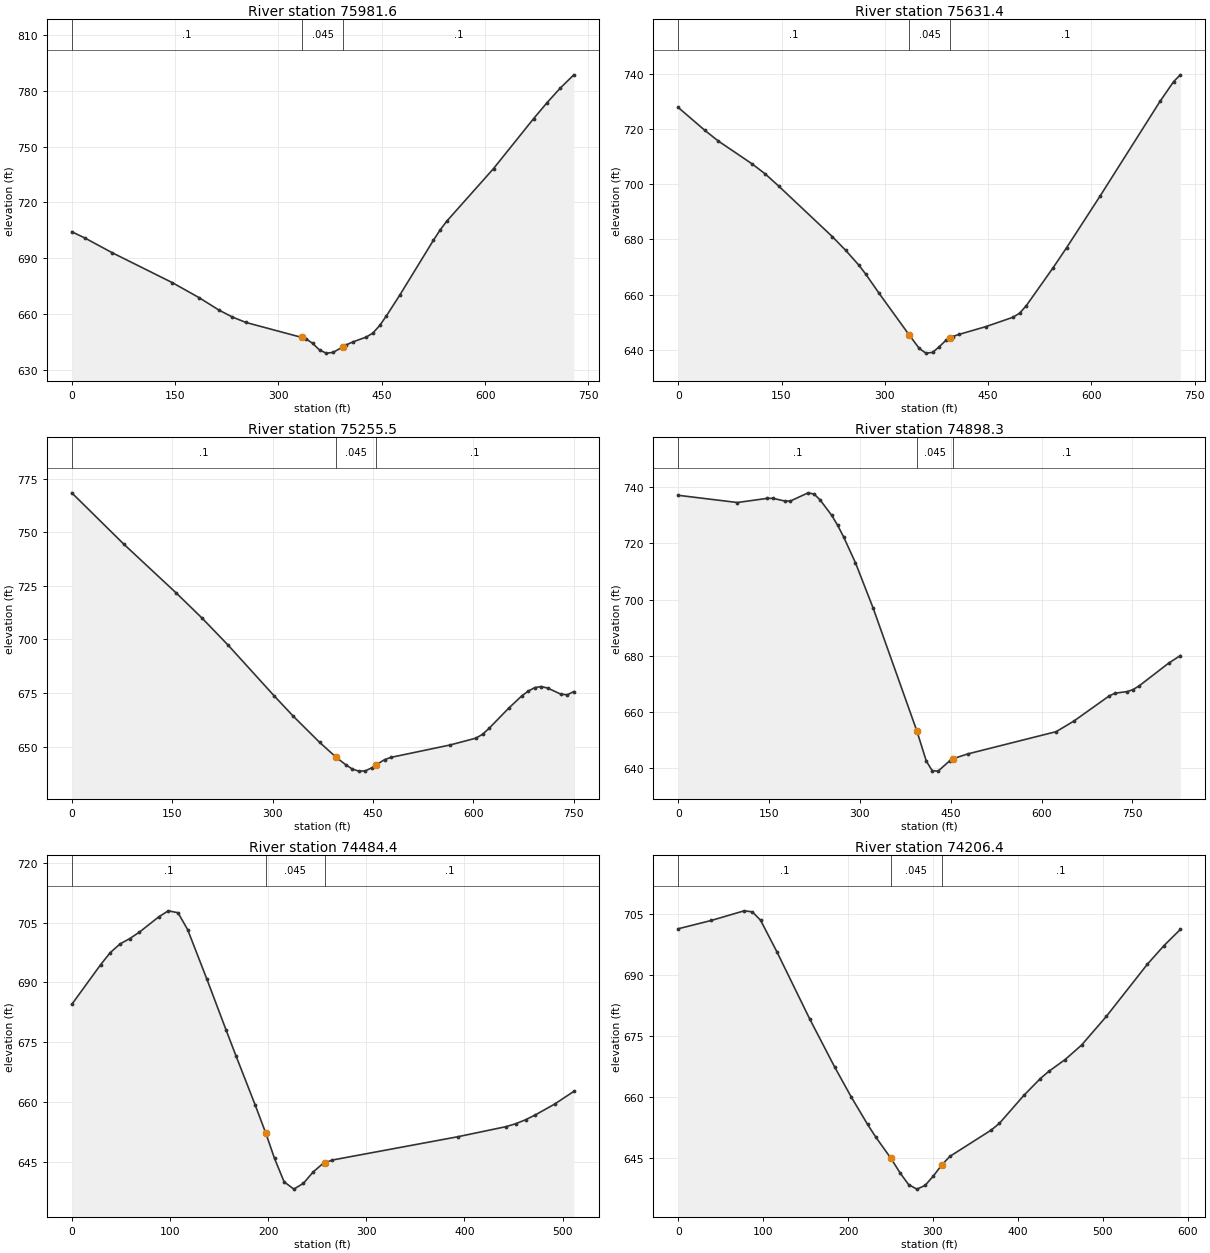
Type RM Length L Ch R = 1 ,75981.6 ,354.1,350.2,346.3
XS GIS Cut Line= 2
     1740719.198      596270.254     1740911.638      596973.241
#Sta/Elev= 30
       0  704.21    19.4  700.76    58.3  692.97   145.8  676.82   184.6  668.76
   213.8  661.98   233.2  658.27   252.7  655.36   334.2  647.25   340.1  646.54
   349.8  644.03   359.6  640.54   369.3  638.83     379  639.17   394.2  642.31
   398.4  643.26   408.2   644.9   427.6   647.5   437.3  649.71     447  653.73
   456.8  658.93   476.2  670.13   524.8  699.52   534.5  705.04   544.2  709.84
   612.2  738.21   670.5  765.17     690  773.75   709.4  781.68   728.8   788.7
#Mann= 3 , 0 , 0
       0      .1       0   334.2    .045       0   394.2      .1       0
Bank Sta=334.2,394.2
XS Rating Curve= 0 ,0
Exp/Cntr=0.3,0.1

Type RM Length L Ch R = 1 ,75631.4 ,378.3,375.9,372.3
XS GIS Cut Line= 2
     1740350.633      596369.143     1740603.465      597052.883
#Sta/Elev= 30
       0  727.73    38.9   719.4    58.3  715.57   106.9  707.39   126.4  703.68
   145.8  699.31   223.6  681.06     243   676.1   262.4  670.67   272.2  667.48
   291.6  660.53     335  645.59   349.9  640.59   359.6  638.89   369.4  639.15
   379.1  641.23   388.8  643.56     395  644.41   398.5  644.89   408.2  645.69
   447.1  648.51     486  651.86   495.7  653.34   505.4  656.06   544.3  669.77
   563.8  676.98   612.4  695.65   699.8  730.04   719.3  737.08     729  739.53
#Mann= 3 , 0 , 0
       0      .1       0     335    .045       0     395      .1       0
Bank Sta=335,395
XS Rating Curve= 0 ,0
Exp/Cntr=0.3,0.1

Type RM Length L Ch R = 1 ,75255.5 ,380.4,357.3,335.2
XS GIS Cut Line= 2
     1739972.497      596460.478     1740278.702      597145.328
#Sta/Elev= 30
       0  768.33    77.9  744.36   155.9  721.68   194.8  709.87   233.8  697.24
     302  673.79   331.2  664.08   370.2     652   395.3  644.92   409.2  641.56
   418.9  639.57   428.7  638.54   438.4  638.64   448.2  640.09   455.3  641.61
   467.6  643.92   477.4  644.99   565.1  650.72     604  653.93   613.8  655.72
   623.5  658.48   652.8  667.88   672.2  673.58     682  675.85   691.7  677.48
   701.5  677.99   711.2  677.27   730.7  674.44   740.4  674.13   750.2  675.66
#Mann= 3 , 0 , 0
       0      .1       0   395.3    .045       0   455.3      .1       0
Bank Sta=395.3,455.3
XS Rating Curve= 0 ,0
Exp/Cntr=0.3,0.1

Type RM Length L Ch R = 1 ,74898.3 ,470.3,413.9,357.3
XS GIS Cut Line= 2
     1739512.121      596787.544     1740181.899      597276.402
#Sta/Elev= 30
       0  737.15    97.6  734.58   146.3  736.04   156.1  736.09   175.6  735.12
   185.4  735.13   214.6  738.03   224.4  737.58   234.1  735.56   253.6  729.98
   263.4   726.4   273.2   722.3   292.7  713.11   321.9  696.97   394.2  653.13
   409.7  642.44   419.5  639.04   429.2  638.88   448.8  642.66   454.2  643.33
     478     645   624.3  652.95   653.6  656.74   712.1  665.73   721.9  666.65
   741.4  667.22   751.2  667.94   760.9   669.2   809.7  677.31   829.2  680.05
#Mann= 3 , 0 , 0
       0      .1       0   394.2    .045       0   454.2      .1       0
Bank Sta=394.2,454.2
XS Rating Curve= 0 ,0
Exp/Cntr=0.3,0.1

Type RM Length L Ch R = 1 ,74484.4 ,289.3,278,266.5
XS GIS Cut Line= 2
      1739676.64       597537.22     1740096.113      597244.769
#Sta/Elev= 30
       0  684.47    29.5  694.47    39.3  697.48    49.2  699.64      59  700.97
    68.8  702.58    88.5  706.41    98.3  707.94   108.2  707.46     118  703.24
   137.7  690.76   157.3  677.97   167.2  671.61   186.8  659.26   197.7  652.12
   206.5  645.85   216.3  639.97   226.2  638.14     236  639.61   245.8  642.43
   255.7  644.54   257.7  644.72   265.5  645.44   393.4  651.29   442.5  653.82
   452.4  654.56   462.2  655.54     472  656.73   491.7  659.45   511.4  662.66
#Mann= 3 , 0 , 0
       0      .1       0   197.7    .045       0   257.7      .1       0
Bank Sta=197.7,257.7
XS Rating Curve= 0 ,0
Exp/Cntr=0.3,0.1

Type RM Length L Ch R = 1 ,74206.4 ,202.2,222.4,242.5
XS GIS Cut Line= 2
      1739908.79      597774.889     1740294.181       597326.39
#Sta/Elev= 30
       0  701.28    38.8  703.31    77.6  705.68    87.2  705.44    96.9  703.39
   116.3  695.58   155.1  679.03   184.2  667.35   203.6  660.04     223  653.25
   232.7  650.12   250.3  644.98   261.7  641.21   271.4  638.45   281.1  637.36
   290.8  638.28   300.5   640.6   310.3  643.28   319.9   645.4   368.4  651.83
   378.1  653.48   407.2  660.41   426.5  664.51   436.2  666.24   455.6  669.16
     475  672.72   504.1  679.74   552.6   692.6     572  697.13   591.3  701.11
#Mann= 3 , 0 , 0
       0      .1       0   250.3    .045       0   310.3      .1       0
Bank Sta=250.3,310.3
XS Rating Curve= 0 ,0
Exp/Cntr=0.3,0.1