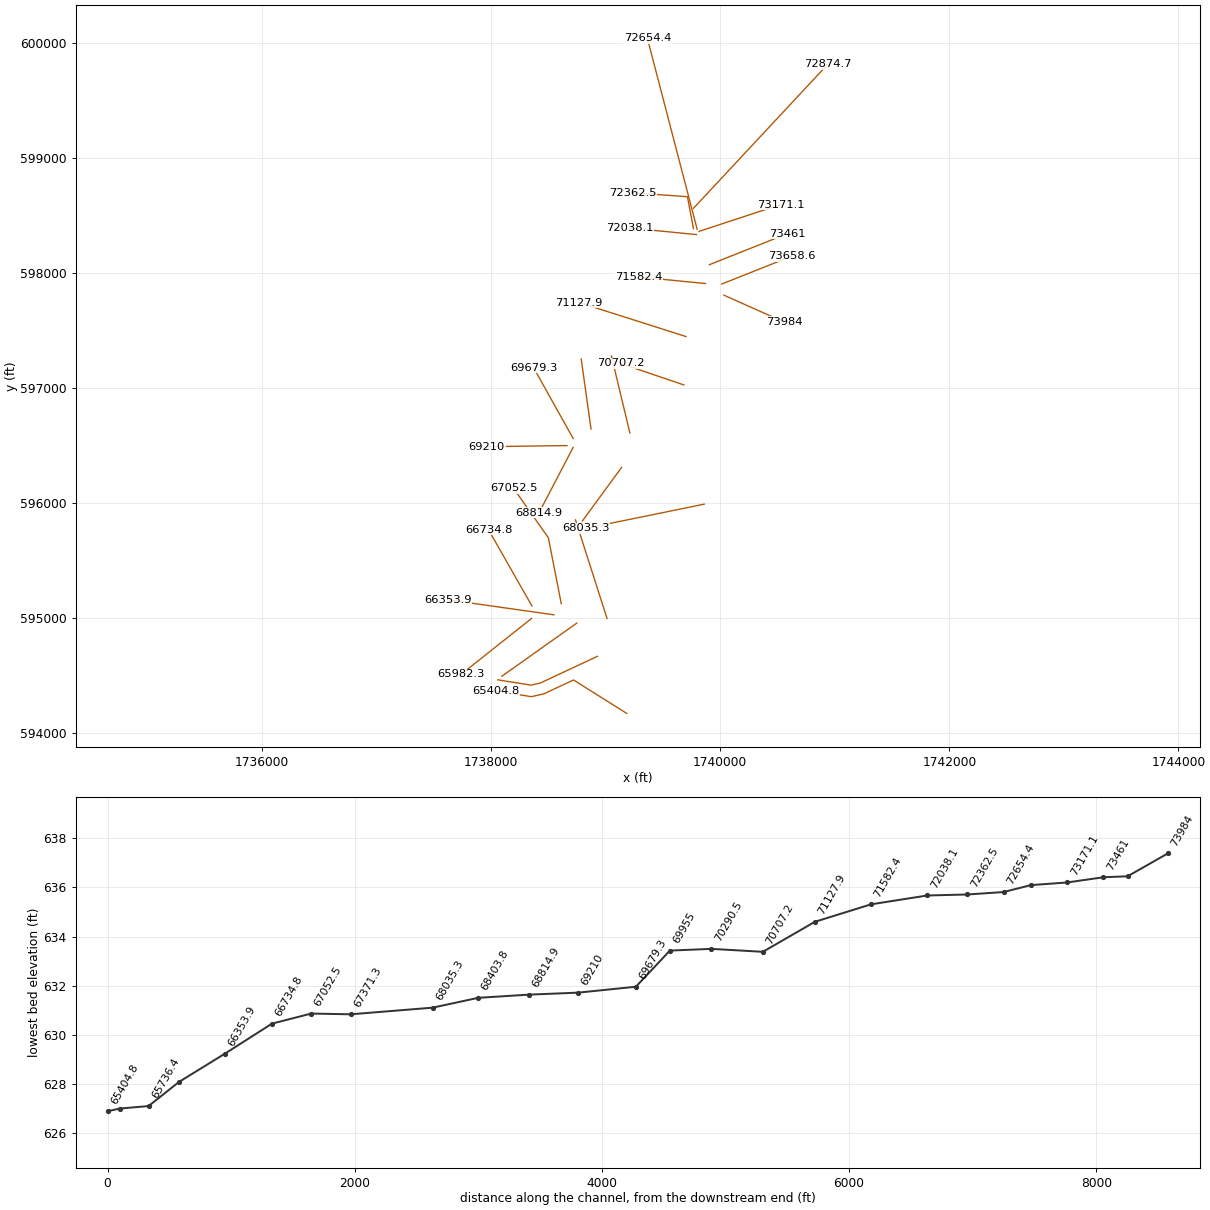
HEC-RAS study EightenmC1.prj: EightenmC1

--- EightenmC1.g01 (geometry) --- (continued)

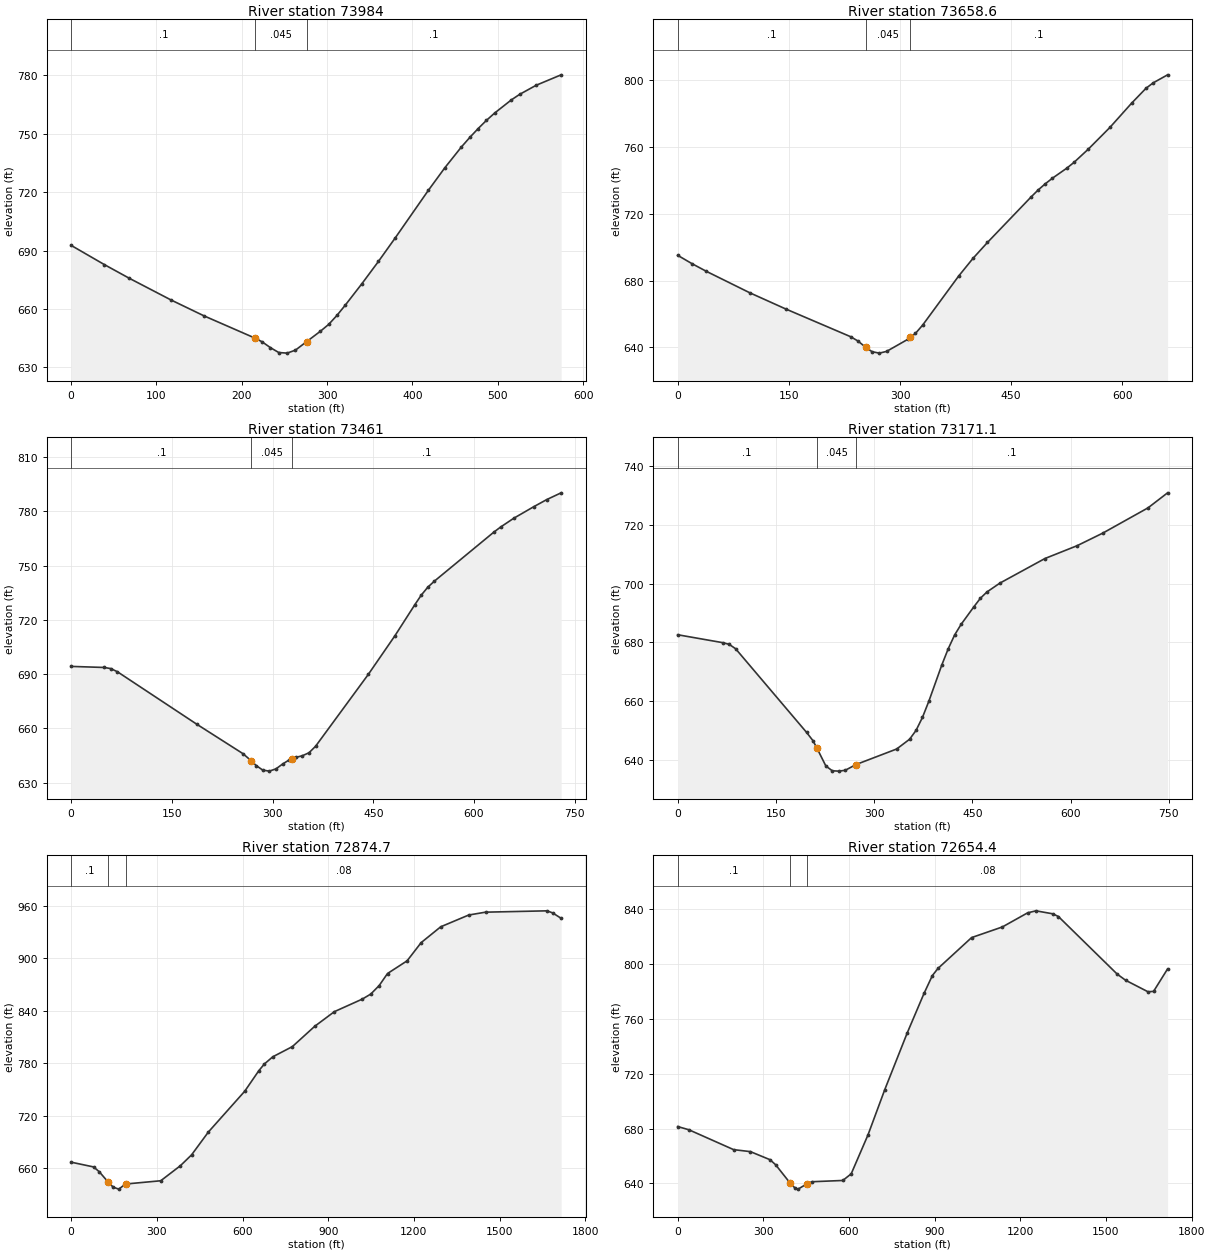
Type RM Length L Ch R = 1 ,73984   ,289.5,325.4,361.3
XS GIS Cut Line= 2
      1740032.62       597808.36     1740557.419      597575.247
#Sta/Elev= 30
       0  692.71    38.9  682.85    68.1  675.83   116.8  664.73   155.7  656.52
   215.9     645   223.9  643.16   233.6  640.17   243.3  637.69   253.1  637.38
   262.8  638.91   275.9  643.26     292  648.59   301.7   652.1   311.4  656.71
   321.2     662   340.6  672.96   360.1  684.47   379.6  696.44   418.5  720.92
     438  732.62   457.4  743.29   467.2  748.17   476.9  752.68   486.6  756.89
   496.4  760.72   515.8  767.41   525.6  770.28     545  774.96   574.2  780.31
#Mann= 3 , 0 , 0
       0      .1       0   215.9    .045       0   275.9      .1       0
Bank Sta=215.9,275.9
XS Rating Curve= 0 ,0
Exp/Cntr=0.3,0.1

Type RM Length L Ch R = 1 ,73658.6 ,197.7,197.6,197.8
XS GIS Cut Line= 2
      1740013.48      597905.283     1740627.849       598149.09
#Sta/Elev= 30
       0  695.15    19.4  690.11    38.9  685.49    97.2  672.68   145.8  662.95
   233.3  646.32     243   643.8     254  639.86   262.4  637.28   272.2  636.45
   281.9  637.49     311  644.85     314  645.89   320.8  648.26   330.5  653.23
   379.1  682.67   398.5  693.31     418  702.85   476.3  729.88     486  734.17
   495.7  737.92   505.4  741.31   524.9  747.37   534.6  750.82     554   758.8
   583.2  771.85   612.4  786.36   631.8   795.3   641.5  798.57     661   803.4
#Mann= 3 , 0 , 0
       0      .1       0     254    .045       0     314      .1       0
Bank Sta=254,314
XS Rating Curve= 0 ,0
Exp/Cntr=0.3,0.1

Type RM Length L Ch R = 1 ,73461   ,292.4,289.8,286.9
XS GIS Cut Line= 3
     1739905.378      598073.374     1740582.046      598341.904
     1740583.617      598342.527
#Sta/Elev= 30
       0  694.29    49.2   693.7      59  693.09    68.9  691.33   186.9  662.38
   255.8  646.08   268.4  642.07   275.5  639.52   285.3  636.98   295.1  636.41
     305  637.65   314.8  640.31   324.6  642.59   328.4  643.13   334.5     644
   344.3  644.91   354.2  646.56     364  650.15   442.7  689.96   482.1  711.19
   511.6  728.26   521.4  733.69   531.2  738.09   541.1  741.46   629.6  768.54
   639.5   771.3   659.1  776.16   688.6  782.49   708.3   786.5   729.7  790.23
#Mann= 3 , 0 , 0
       0      .1       0   268.4    .045       0   328.4      .1       0
Bank Sta=268.4,328.4
XS Rating Curve= 0 ,0
Exp/Cntr=0.3,0.1

Type RM Length L Ch R = 1 ,73171.1 ,273.8,296.4,319.1
XS GIS Cut Line= 3
     1739814.754      598362.974     1740506.634      598589.446
     1740525.727      598595.696
#Sta/Elev= 30
       0  682.64    68.9  679.94    78.7  679.37    88.5  677.88   196.8  649.41
   206.6  646.58   212.5  644.12   226.3  637.96   236.1  636.32     246   636.2
   255.8  636.48   272.5  638.45   334.5  643.74   354.2  647.06     364  650.06
   373.8  654.48   383.7  660.08   403.4  672.37   413.2  677.89     423  682.58
   432.9   686.2   452.5  692.21   462.4  695.09   472.2  697.19   491.9   700.2
   560.8  708.59     610  712.96   649.3  717.26   718.2  725.84   748.1  730.96
#Mann= 3 , 0 , 0
       0      .1       0   212.5    .045       0   272.5      .1       0
Bank Sta=212.5,272.5
XS Rating Curve= 0 ,0
Exp/Cntr=0.3,0.1

Type RM Length L Ch R = 1 ,72874.7 ,173.6,220.3,266.9
XS GIS Cut Line= 2
     1739765.923      598563.302     1740938.822      599815.423
#Sta/Elev= 30
       0   666.9    78.4  661.47      98   656.1   130.4  643.88   147.1  638.34
   166.7  636.09   190.4  641.93   313.7  645.66   382.4  662.84   421.6  675.24
   480.4  701.34   607.8  748.03   656.8  771.33   676.5  779.16   705.9  787.36
   774.5     799   852.9  822.25   921.6  838.97  1019.6  853.37    1049  859.08
  1078.4  868.76  1107.8  882.59  1176.4  897.11  1225.5  917.89  1294.1  936.01
  1392.1  949.46    1451  952.73  1666.6  954.26  1686.2  951.86  1715.7  945.71
#Mann= 3 , 0 , 0
       0      .1       0   130.4    .045       0   190.4     .08       0
Bank Sta=130.4,190.4
XS Rating Curve= 0 ,0
Exp/Cntr=0.3,0.1

Type RM Length L Ch R = 1 ,72654.4 ,234.6,291.9,349.2
XS GIS Cut Line= 2
     1739798.508      598381.285     1739364.057      600041.028
#Sta/Elev= 30
       0  681.49    39.2  679.16   196.1  664.63   254.9  663.18   323.5  657.29
   343.1  653.62   393.4  640.38   411.8  636.45   421.6  635.81   453.4  639.73
   470.6  641.21   578.4  642.13   607.8  646.99   666.7  675.44   725.5  708.52
   803.9  749.79   862.7  778.63   892.1  791.74   911.8  796.92  1029.4  819.42
  1137.2  827.19  1225.5  837.48  1254.9  838.95  1313.7  836.77  1333.3   834.8
  1539.2  792.76  1568.6  788.28    1647  779.87  1666.6  780.16  1715.7  796.56
#Mann= 3 , 0 , 0
       0      .1       0   393.4    .045       0   453.4     .08       0
Bank Sta=393.4,453.4
XS Rating Curve= 0 ,0
Exp/Cntr=0.3,0.1

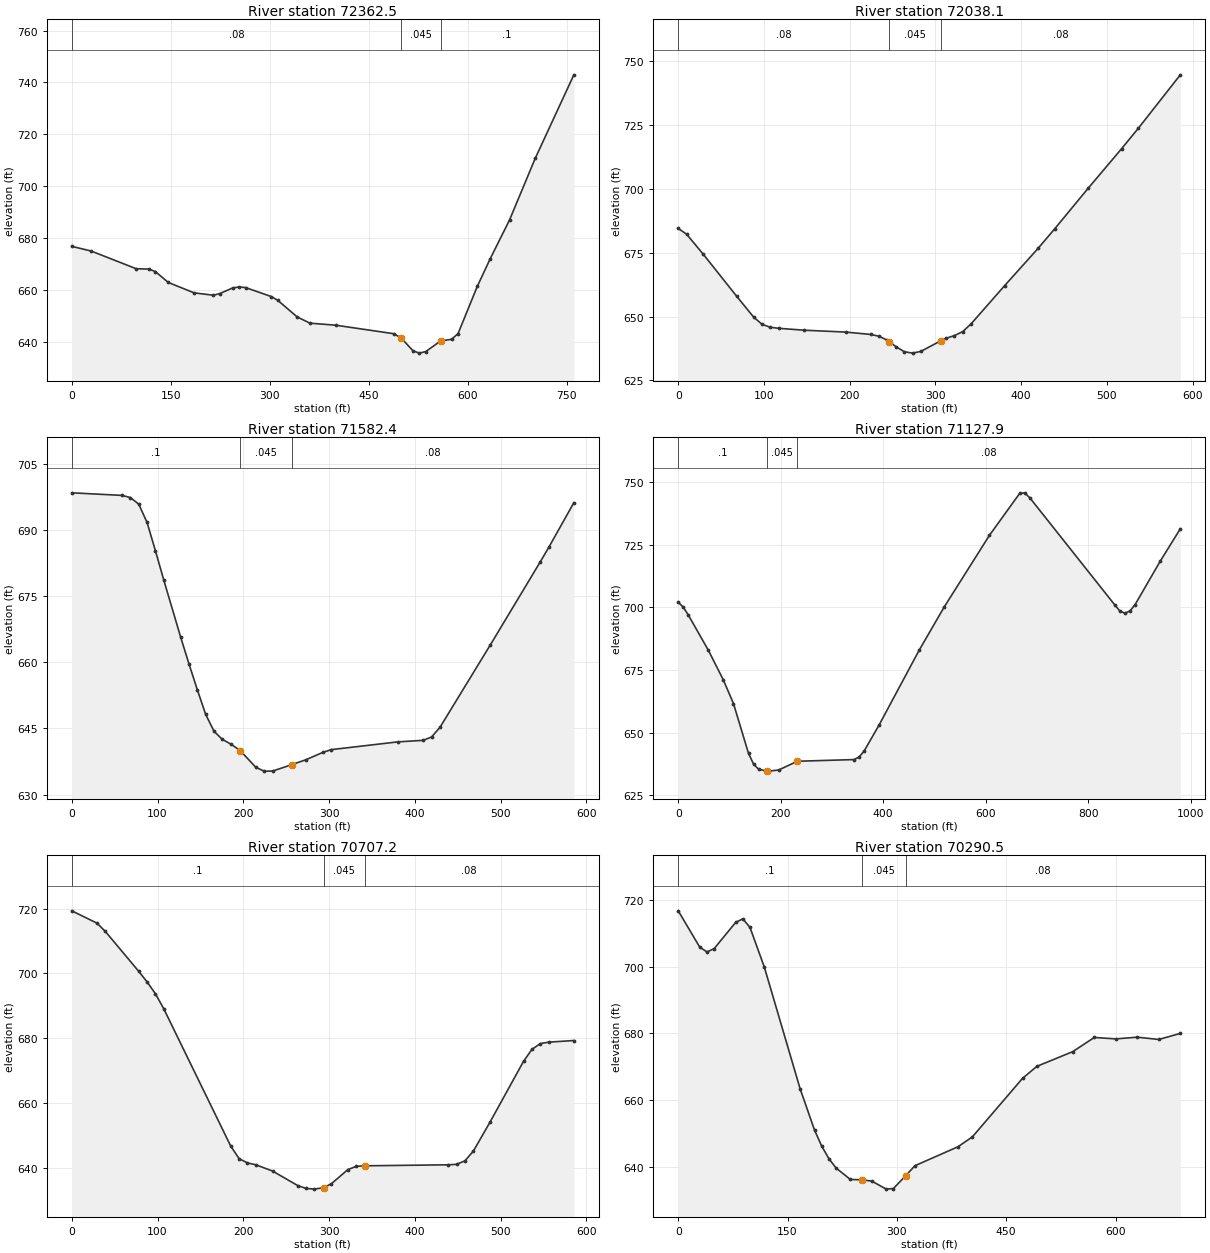
Type RM Length L Ch R = 1 ,72362.5 ,325.7,324.5,323.3
XS GIS Cut Line= 3
      1739766.58      598386.275     1739713.615      598664.222
     1739236.881      598698.821
#Sta/Elev= 30
       0  676.85    29.3  675.06    97.6  668.24   117.1  668.09   126.8  667.11
   146.4  662.93   185.4  658.93   214.6  658.02   224.4  658.66   243.9  660.83
   253.7  661.21   263.4  660.97   302.5   657.5   312.2  656.06   341.5  649.68
     361  647.25     400  646.47   487.8   643.2     499   641.6   517.1  636.62
   526.8  635.71   536.6  636.33     559  640.41   575.6  641.04   585.4  643.22
   614.6  661.44   634.1  672.06   663.4     687   702.4  710.78   760.9  742.95
#Mann= 3 , 0 , 0
       0     .08       0     499    .045       0     559      .1       0
Bank Sta=499,559
XS Rating Curve= 0 ,0
Exp/Cntr=0.3,0.1

Type RM Length L Ch R = 1 ,72038.1 ,455.5,455.7,455.4
XS GIS Cut Line= 2
     1739792.113      598335.264      1739209.44      598392.307
#Sta/Elev= 30
       0  684.48     9.8   682.2    29.3  674.33    68.3  657.86    87.8  649.82
    97.6  646.98   107.3  645.79   117.1  645.39   146.4  644.65   195.2  643.91
   224.4  642.98   234.2  642.27   243.9  640.72   245.9  640.22   253.7  638.25
   263.5  636.24   273.2  635.67     283  636.36   305.9  640.45   312.2  641.46
     322  642.52   331.8   644.1   341.5  647.12   380.6  662.07   419.6  676.66
   439.1  684.35   478.1  700.22   517.2  715.74   536.7  723.74   585.5  744.59
#Mann= 3 , 0 , 0
       0     .08       0   245.9    .045       0   305.9     .08       0
Bank Sta=245.9,305.9
XS Rating Curve= 0 ,0
Exp/Cntr=0.3,0.1

Type RM Length L Ch R = 1 ,71582.4 ,463.9,454.5,445.1
XS GIS Cut Line= 2
     1739870.298      597909.797     1739287.626       597966.84
#Sta/Elev= 30
       0   698.4    58.6  697.82    68.3  697.33    78.1  695.84    87.8  691.68
    97.6  685.24   107.3  678.62   126.8   665.8   136.6  659.66   146.4  653.77
   156.1   648.2   165.9  644.34   175.6   642.5   185.4  641.46   196.4  639.98
   214.7  636.16   224.4  635.31   234.2  635.32   256.4  636.77   273.2   637.9
   292.7  639.55   302.5  640.18   380.6  641.95   409.8  642.29   419.6  643.06
   429.3  645.21   487.9  663.86   546.4  682.77   556.2  686.02   585.5  696.16
#Mann= 3 , 0 , 0
       0      .1       0   196.4    .045       0   256.4     .08       0
Bank Sta=196.4,256.4
XS Rating Curve= 0 ,0
Exp/Cntr=0.3,0.1

Type RM Length L Ch R = 1 ,71127.9 ,433.6,420.6,413.5
XS GIS Cut Line= 2
      1739701.43      597448.807      1738767.59      597744.602
#Sta/Elev= 30
       0  701.95     9.8  700.02    19.6  696.91    58.8   682.8    88.2   670.9
   107.8  661.55   137.1  641.68   146.9  637.44   156.7  635.38   172.4  634.64
   176.3   634.6   195.9  635.04   232.4  638.54   342.8  639.21   352.6   640.2
   362.4  642.52   391.8  652.96   470.2  682.89   519.2  700.17   607.3   728.7
   666.1  745.37   675.9  745.62   685.7   743.7   852.2  700.79     862   698.4
   871.8  697.61   881.6  698.54   891.4  701.03   940.4  718.35   979.6  731.27
#Mann= 3 , 0 , 0
       0      .1       0   172.4    .045       0   232.4     .08       0
Bank Sta=172.4,232.4
XS Rating Curve= 0 ,0
Exp/Cntr=0.3,0.1

Type RM Length L Ch R = 1 ,70707.2 ,454.3,416.8,371.3
XS GIS Cut Line= 2
      1739682.68      597028.337      1739128.06       597215.84
#Sta/Elev= 30
       0  719.32    29.3  715.53      39     713    78.1  700.63    87.8  697.38
    97.6  693.69   107.3  689.07   185.4  646.65   195.2  642.77   204.9  641.48
   214.7  640.89   234.2  638.96   263.5  634.48   273.2   633.6     283  633.38
   293.6  633.84   302.5  634.99     322  639.42   331.8  640.41   341.5  640.58
   439.1  640.89   448.8  641.04   458.6  642.14   468.4  645.16   487.9  654.15
   526.9  672.88   536.7  676.55   546.4  678.32   556.2  678.77   585.5  679.27
#Mann= 3 , 0 , 0
       0      .1       0   293.6    .045       0   341.5     .08       0
Bank Sta=293.6,341.5
XS Rating Curve= 0 ,0
Exp/Cntr=0.3,0.1

Type RM Length L Ch R = 1 ,70290.5 ,340,335.5,330.3
XS GIS Cut Line= 2
     1739211.186      596610.551      1739050.19      597280.314
#Sta/Elev= 30
       0  716.64    29.5   705.8    39.4  704.36    49.2  705.33    78.7  713.16
    88.6  714.26    98.4  711.69   118.1  699.84   167.3  663.42     187  651.13
   196.8  646.37   206.6  642.63   216.5  639.81   236.2  636.38   252.2  636.29
   265.7  635.88   285.4   633.5   295.2  633.68   312.2  637.54   324.7  640.49
   383.8  646.16   403.5   649.1   472.4  666.61     492  670.18   541.2  674.57
   570.8  678.81   600.3  678.38   629.8  678.89   659.3  678.21   688.8  680.02
#Mann= 3 , 0 , 0
       0      .1       0   252.2    .045       0   312.2     .08       0
Bank Sta=252.2,312.2
XS Rating Curve= 0 ,0
Exp/Cntr=0.3,0.1

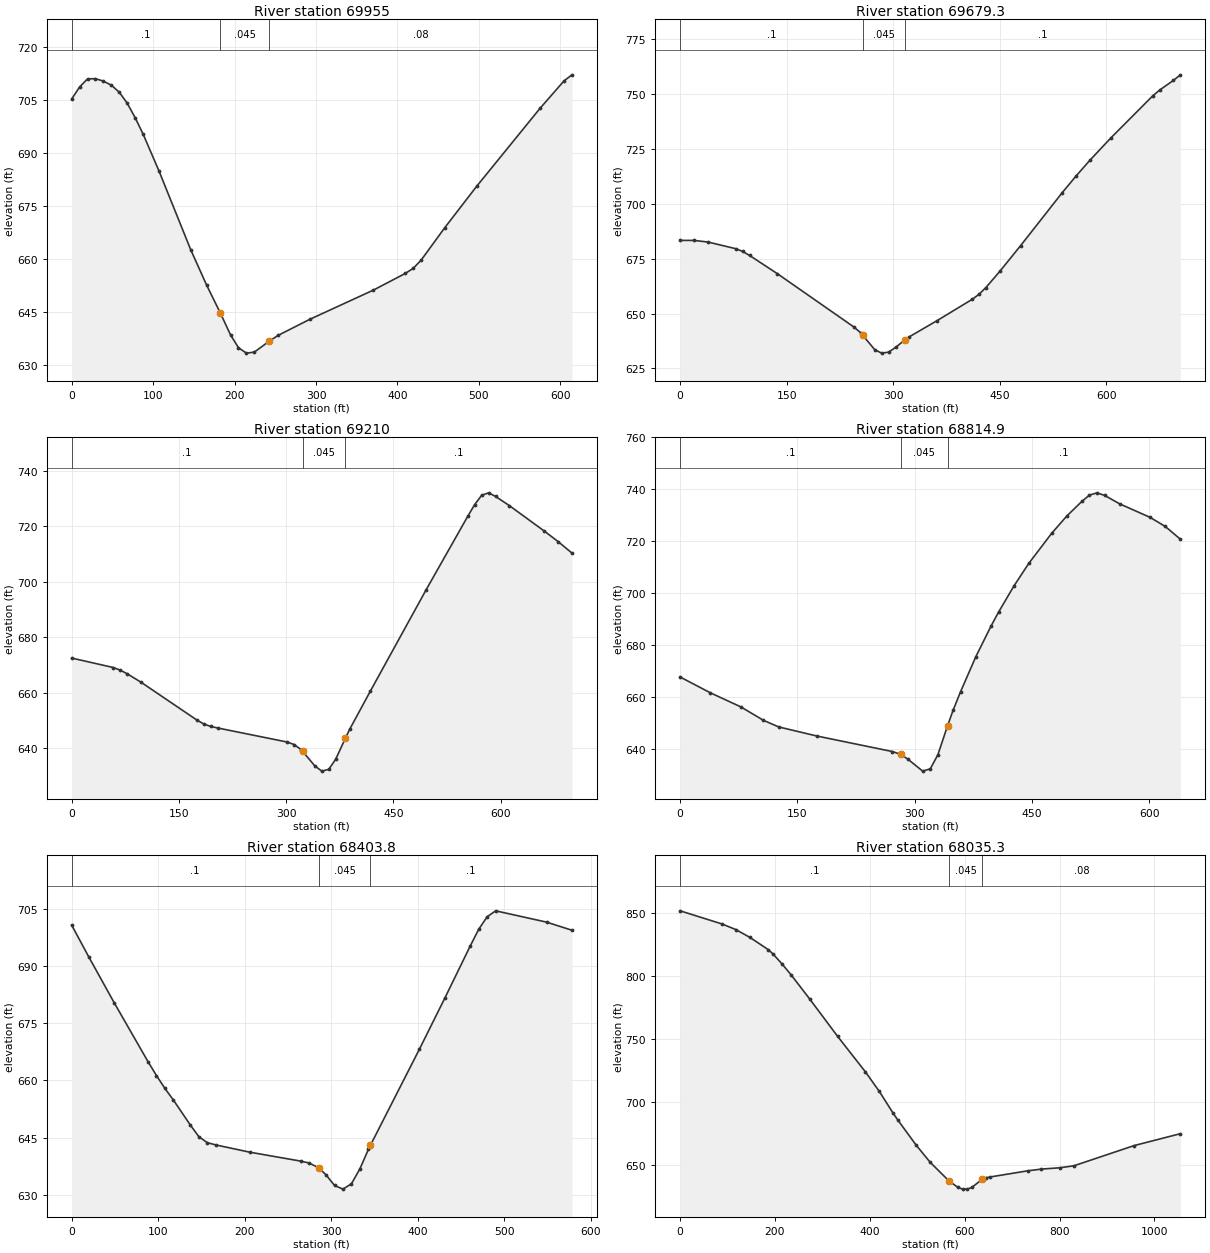
Type RM Length L Ch R = 1 ,69955   ,258.9,275.6,292.1
XS GIS Cut Line= 2
     1738871.732      596645.822     1738786.344      597254.109
#Sta/Elev= 30
       0  705.32     9.8  708.74    19.5  711.01    29.2  711.07      39  710.37
    48.8  709.22    58.5  707.22    68.2  704.13      78     700    87.8  695.34
   107.2  684.96   146.2  662.66   165.8  652.61   182.3  644.88     195  638.61
   204.8  634.96   214.5  633.43   224.2  633.71   242.3  636.76   253.5  638.46
   292.5  643.01   370.5  651.27   409.5  655.96   419.2   657.4     429  659.72
   458.2  668.96   497.2  680.62   575.2  702.73   604.5  710.45   614.2  712.16
#Mann= 3 , 0 , 0
       0      .1       0   182.3    .045       0   242.3     .08       0
Bank Sta=182.3,242.3
XS Rating Curve= 0 ,0
Exp/Cntr=0.3,0.1

Type RM Length L Ch R = 1 ,69679.3 ,420.9,469.3,517.8
XS GIS Cut Line= 2
      1738716.08      596562.725     1738370.984      597177.113
#Sta/Elev= 30
       0  683.32    19.6   683.3    39.2  682.57    78.3  679.54    88.1  678.28
    97.9  676.44     137  668.14   244.7  643.88   254.5  641.19   257.2  640.11
     274  633.57   283.8  631.96   293.6  632.39   303.4  634.56   317.2  638.13
     323  639.43   362.1   646.8   411.1  656.41   420.8   658.7   430.6  661.79
   450.2  669.17   479.6  680.93   538.3  705.09   557.9  712.72   577.4  719.89
   606.8  730.02   665.5  749.08   675.3  751.76   694.9  756.22   704.7  758.74
#Mann= 3 , 0 , 0
       0      .1       0   257.2    .045       0   317.2      .1       0
Bank Sta=257.2,317.2
XS Rating Curve= 0 ,0
Exp/Cntr=0.3,0.1

Type RM Length L Ch R = 1 ,69210   ,345.9,395.1,443.8
XS GIS Cut Line= 2
     1738662.434       596501.26     1737962.684      596491.942
#Sta/Elev= 30
       0   672.5    58.3  669.08      68  668.13    77.8  666.81    97.2  663.75
     175  650.17   184.7  648.73   194.4  647.84   204.1  647.29   301.3  642.22
     311  641.32   320.8  639.51   322.9   638.9   340.2  633.59   349.9  631.72
   359.6  632.36   369.3  636.01   382.9  643.59   388.8  646.78   417.9  660.62
   495.7  697.06     554   723.6   563.7  727.83   573.5   731.2   583.2  732.09
   592.9   730.8   612.3  727.47   660.9  718.34   680.4  714.52   699.8  710.36
#Mann= 3 , 0 , 0
       0      .1       0   322.9    .045       0   382.9      .1       0
Bank Sta=322.9,382.9
XS Rating Curve= 0 ,0
Exp/Cntr=0.3,0.1

Type RM Length L Ch R = 1 ,68814.9 ,418.2,411.1,404.3
XS GIS Cut Line= 2
     1738715.643      596485.071     1738418.605      595918.375
#Sta/Elev= 30
       0  667.82    38.8  661.72    77.6  656.34   106.6  651.16     126  648.63
   174.5  645.16   271.4  639.17     282  638.09   290.8  636.35   310.2  631.64
   319.9  632.52   329.6  637.91     342  649.07     349  654.96   358.7  662.21
   378.1  675.57   397.5  687.34   407.2  692.74   426.6  702.66   445.9  711.49
     475  722.98   494.4  729.66   513.8  735.32   523.5  737.72   533.2  738.61
   542.9  737.61   562.3  734.35     601  729.18   620.4  725.69   639.8  720.77
#Mann= 3 , 0 , 0
       0      .1       0     282    .045       0     342      .1       0
Bank Sta=282,342
XS Rating Curve= 0 ,0
Exp/Cntr=0.3,0.1

Type RM Length L Ch R = 1 ,68403.8 ,403,368.5,332.8
XS GIS Cut Line= 2
     1739138.674       596311.27     1738796.096      595845.196
#Sta/Elev= 30
       0  700.74    19.6  692.48      49  680.45    88.2  664.96      98   661.3
   107.8  657.92   117.6  654.87   137.3  648.29   147.1  645.25   156.9  643.69
   166.7   643.1   205.9   641.2   264.7  638.86   274.5  638.36   285.4  637.13
   294.1  635.26   303.9  632.47   313.7  631.51   323.5  632.92   333.3  636.86
   343.1  641.95   345.4     643     402  668.19   431.4  681.59   460.8  695.27
   470.6  699.64   480.4  702.94   490.2  704.49     549  701.53   578.4   699.4
#Mann= 3 , 0 , 0
       0      .1       0   285.4    .045       0   345.4      .1       0
Bank Sta=285.4,345.4
XS Rating Curve= 0 ,0
Exp/Cntr=0.3,0.1

Type RM Length L Ch R = 1 ,68035.3 ,729,664,599.8
XS GIS Cut Line= 2
     1739860.596      595992.243     1738826.896      595781.887
#Sta/Elev= 30
       0  852.09    87.9   841.7   117.2  837.25   146.5  831.13   185.6  821.34
   195.4  818.02   214.9  809.93   234.4  801.07   273.5  781.94   332.1  752.39
   390.7  724.22     420  708.71   449.3  691.31   459.1  685.94   498.1  665.84
   527.4  652.37   566.5  637.77     586  632.43   595.8  631.11   605.6  631.12
   615.4  632.57     637   638.9   644.6  640.08   654.4   640.8   732.6  645.63
   761.9  647.02   800.9  648.08   830.2  649.62   957.2  665.68  1054.9  675.13
#Mann= 3 , 0 , 0
       0      .1       0   566.5    .045       0     637     .08       0
Bank Sta=566.5,637
XS Rating Curve= 0 ,0
Exp/Cntr=0.3,0.1

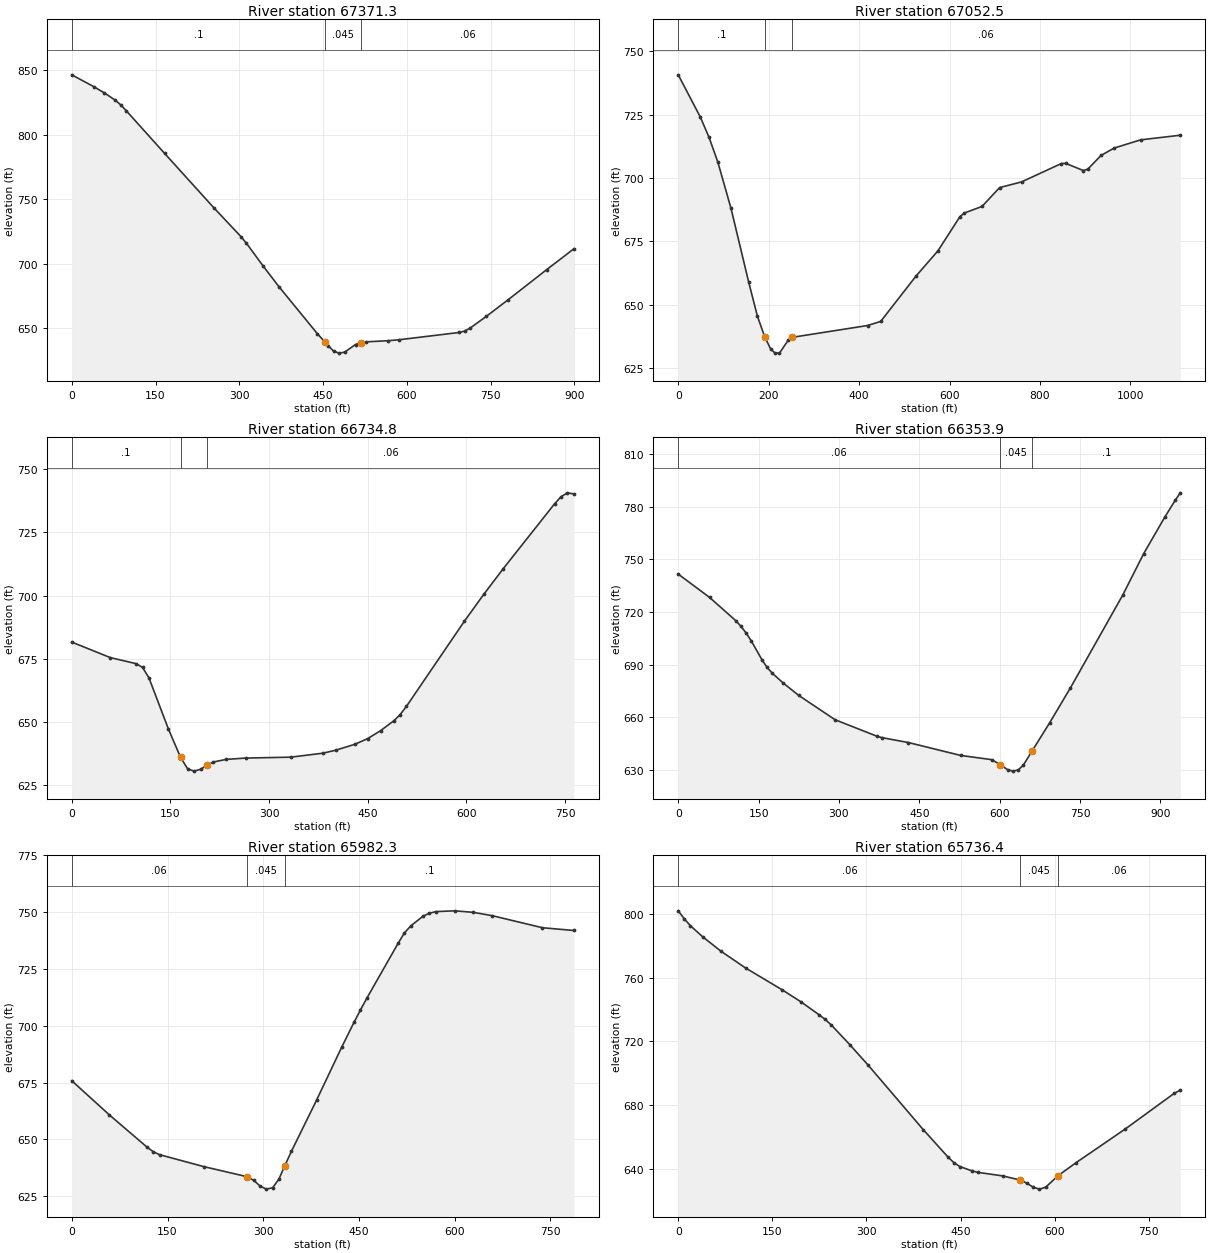
Type RM Length L Ch R = 1 ,67371.3 ,324.3,318.8,313.4
XS GIS Cut Line= 2
     1739011.555      594999.267     1738736.379      595855.112
#Sta/Elev= 30
       0  846.35    39.1  837.26    58.6  832.29    78.2  826.62      88  822.94
    97.7  818.49   166.1  785.58   254.1  743.53   302.9  721.08   312.7  715.97
     342  698.65   371.3  682.11   439.7  645.93   453.1  639.48   459.3  636.54
     469  632.31   478.8  630.84   488.6   631.6   508.1  637.51   517.9  639.05
   527.7  639.59   566.8  640.46   586.3  641.21   693.8  646.84   703.6  647.96
   713.3  650.23   742.6  659.41   781.7  672.29   850.1  695.42     899  711.62
#Mann= 3 , 0 , 0
       0      .1       0   453.1    .045       0   517.9     .06       0
Bank Sta=453.1,517.9
XS Rating Curve= 0 ,0
Exp/Cntr=0.3,0.1

Type RM Length L Ch R = 1 ,67052.5 ,302.8,317.7,332.6
XS GIS Cut Line= 3
     1738612.075      595127.041     1738499.576      595700.212
      1738195.65       596129.85
#Sta/Elev= 30
       0  740.74    48.7  724.13    68.2  716.02    87.6  706.28   116.8  687.97
   155.8   658.9   175.2   645.4   191.1   637.4   204.4  632.49   214.2  630.87
   223.9  630.88   243.4  636.02   251.1  637.08   418.6  641.77   447.8  643.39
   525.7  661.26   574.4  671.26   623.1  684.78   632.8  686.18   671.8  688.78
   710.8  696.22   759.5  698.48   847.2  705.71     857  705.78     896  702.95
   905.7  703.48     935  708.91   964.2  711.84  1022.7  715.07  1110.4   716.9
#Mann= 3 , 0 , 0
       0      .1       0   191.1    .045       0   251.1     .06       0
Bank Sta=191.1,251.1
XS Rating Curve= 0 ,0
Exp/Cntr=0.3,0.1

Type RM Length L Ch R = 1 ,66734.8 ,339.3,380.8,422.2
XS GIS Cut Line= 2
     1738356.037      595106.905     1737977.245      595769.525
#Sta/Elev= 30
       0  681.57    58.7  675.41    97.8  673.03   107.6  671.55   117.4  667.34
   146.8  647.21   165.3  635.96   176.1  631.36   185.9  630.46   195.7  631.19
   205.5  632.76   215.3  634.08   234.8  635.11   264.2  635.63   332.7  635.99
   381.6  637.56   401.2  638.74   430.6  641.12   450.1  643.38   469.7  646.53
   489.3  650.36     499   652.8   508.8  656.14   596.9  689.87   626.3  700.49
   655.6  710.56   733.9  736.34   743.7  739.14   753.5  740.69   763.2  740.25
#Mann= 3 , 0 , 0
       0      .1       0   165.3    .045       0   205.5     .06       0
Bank Sta=165.3,205.5
XS Rating Curve= 0 ,0
Exp/Cntr=0.3,0.1

Type RM Length L Ch R = 1 ,66353.9 ,335,371.6,408.4
XS GIS Cut Line= 2
      1738548.38      595030.268     1737620.446      595160.943
#Sta/Elev= 30
       0  741.64    58.6  728.29   107.4  715.06   117.1  711.84   126.9  707.93
   136.7  703.32   156.2  692.78   165.9  688.35   175.7  685.06   195.2  679.68
   224.5  672.51   292.8  658.54   370.9  649.14   380.7  648.31   429.5  645.55
   527.1   638.2   585.7  635.75     601  632.87     615  630.04   624.7  629.24
   634.5  629.91   644.2  632.72     661     641   693.1  656.73   732.1  676.78
   829.7   729.7   868.8  753.35   907.8  773.94   927.3  783.61   937.1  787.98
#Mann= 3 , 0 , 0
       0     .06       0     601    .045       0     661      .1       0
Bank Sta=601,661
XS Rating Curve= 0 ,0
Exp/Cntr=0.3,0.1

Type RM Length L Ch R = 1 ,65982.3 ,248.3,245.9,243.4
XS GIS Cut Line= 2
     1738353.631      594999.387     1737736.426      594511.579
#Sta/Elev= 30
       0   675.8      59  660.75     118  646.55   127.8  644.54   137.7  643.24
   206.5  638.03   273.8  633.62   285.2  631.97     295  629.44   304.8  628.09
   314.7  628.69   324.5  632.47   333.8   638.4   344.2  644.75   383.5  667.22
   422.8  690.49   442.5  701.66   452.4  706.98   462.2  712.08   511.4  736.33
   521.2  740.86     531  743.92   550.7  748.31   560.5  749.54   570.4  750.25
   599.9   750.6   629.4  749.93   658.9  748.46   737.5  743.16   786.7  741.94
#Mann= 3 , 0 , 0
       0     .06       0   273.8    .045       0   333.8      .1       0
Bank Sta=273.8,333.8
XS Rating Curve= 0 ,0
Exp/Cntr=0.3,0.1

Type RM Length L Ch R = 1 ,65736.4 ,246.3,232.4,214.7
XS GIS Cut Line= 2
     1738747.162      594957.988     1738093.435      594496.333
#Sta/Elev= 30
       0  802.14     9.8  797.07    19.5  792.72      39  785.81    68.3  776.68
   107.4  766.18   165.9  752.41   195.2  745.02   224.5  736.78   234.2  733.85
     244  730.34   273.3  718.05   302.6  705.15   390.4   664.6   429.4  647.54
   439.2  643.82     449  641.29   468.5  638.56   478.2  637.63   517.3  635.42
   545.4  632.78   556.3   630.7   566.1  628.26   575.8  627.11   585.6  628.27
   605.4  635.56   634.4  643.82   712.5  664.92   790.5  687.32   800.3  689.38
#Mann= 3 , 0 , 0
       0     .06       0   545.4    .045       0   605.4     .06       0
Bank Sta=545.4,605.4
XS Rating Curve= 0 ,0
Exp/Cntr=0.3,0.1

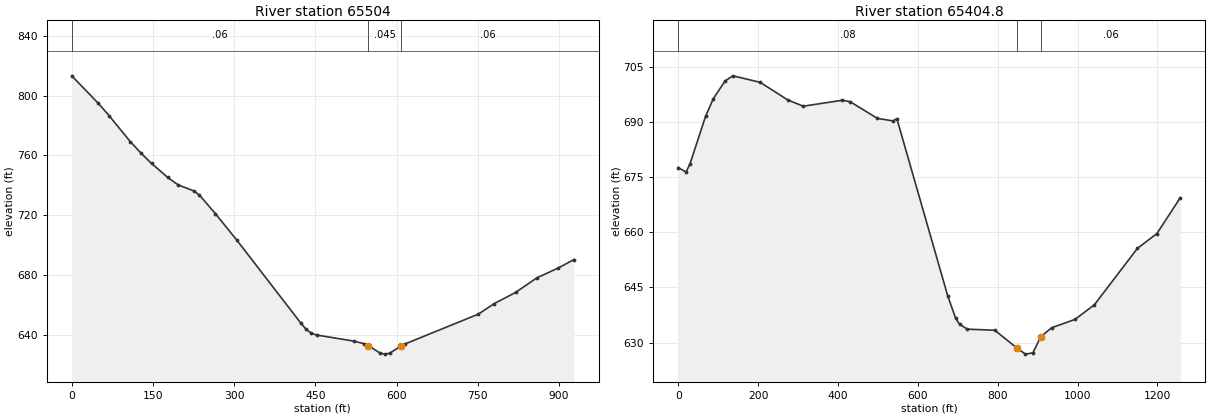
Type RM Length L Ch R = 1 ,65504   ,102.5,99.2,99
XS GIS Cut Line= 4
     1738928.117      594669.757     1738429.269      594437.482
      1738348.14      594419.036     1738057.957      594465.272
#Sta/Elev= 30
       0   813.2    49.1  794.75    68.8  786.59   108.1  769.19   127.7  761.55
   147.4  754.56   176.9  745.33   196.5  740.21     226  736.12   235.8   733.4
   265.3  721.01   304.6  703.39   422.5  648.03   432.4  643.79   442.2  641.05
     452   639.8   520.8  635.74   540.4  633.91   547.7  632.74   568.8  627.84
     578  627.01   587.2  627.62   607.7  632.34     615  633.75     751  653.77
   780.4  660.83   819.6  668.26   858.8     678   897.9  684.53   927.3  690.22
#Mann= 3 , 0 , 0
       0     .06       0   547.7    .045       0   607.7     .06       0
Bank Sta=547.7,607.7
XS Rating Curve= 0 ,0
Exp/Cntr=0.3,0.1

Type RM Length L Ch R = 1 ,65404.8 ,613.6,541.8,470.4
XS GIS Cut Line= 5
      1739183.38      594173.628     1738719.106      594463.833
     1738461.322      594343.803     1738351.426      594318.817
     1738042.466      594368.044
#Sta/Elev= 30
       0  677.56    19.6  676.35    29.3  678.51    68.4  691.47      88   696.3
   117.3  701.08   136.9  702.48   205.3  700.71   273.8  695.96   312.9  694.23
   410.6  695.84   430.2  695.47   498.6  690.94   537.7  690.23   547.5  690.85
     675   642.7   694.6  636.68   704.4  635.03     724  633.68   792.6  633.39
   847.9  628.59   869.4   626.9   888.2  627.24   907.9  631.62   935.2  634.07
   993.4  636.31  1042.3  640.31  1149.9  655.61  1198.8  659.65  1257.4  669.38
#Mann= 3 , 0 , 0
       0     .08       0   847.9    .045       0   907.9     .06       0
Bank Sta=847.9,907.9
XS Rating Curve= 0 ,0
Exp/Cntr=0.3,0.1