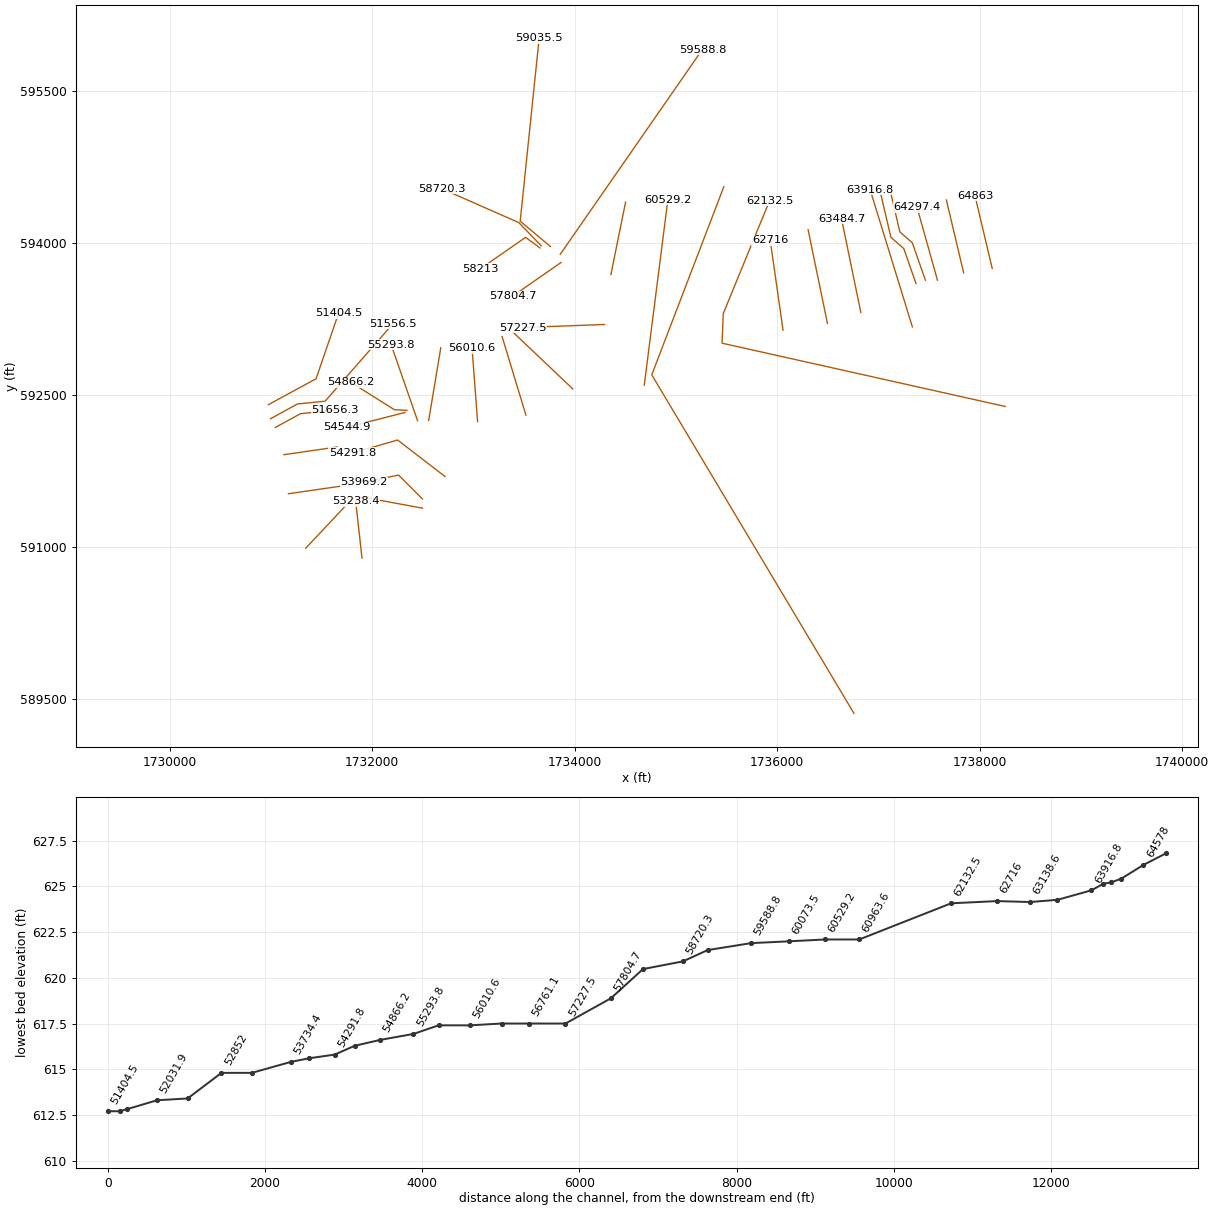
HEC-RAS study EightenmC1.prj: EightenmC1

--- EightenmC1.g01 (geometry) --- (continued)

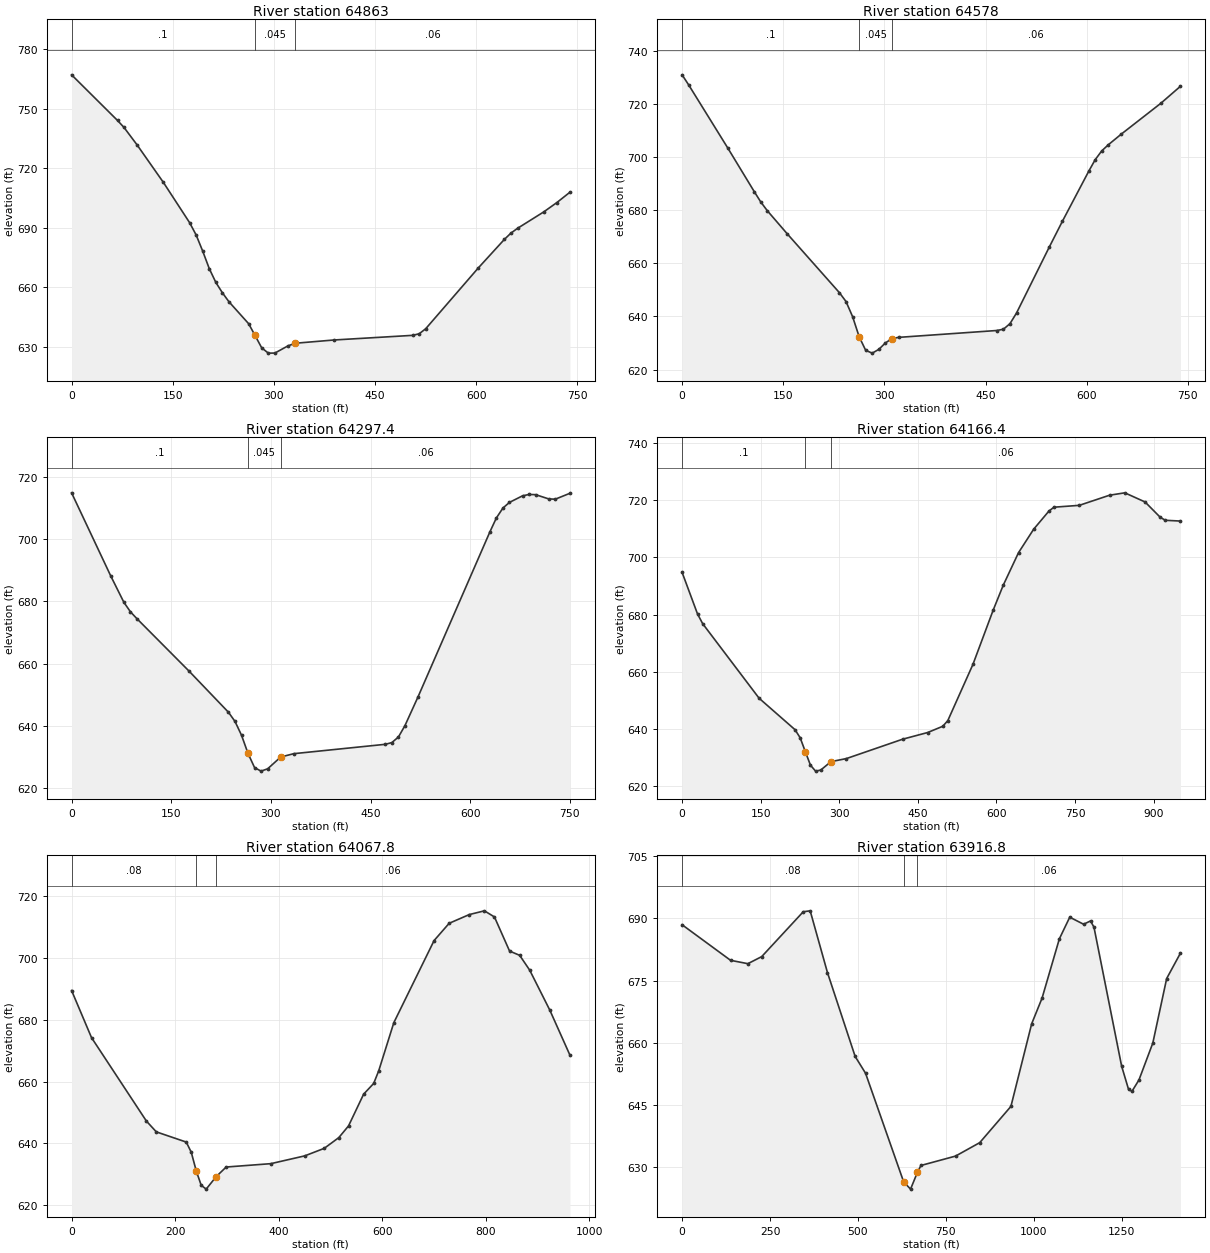
Type RM Length L Ch R = 1 ,64863   ,285,285,285
XS GIS Cut Line= 2
     1738123.309      593751.684     1737952.808      594470.903
#Sta/Elev= 30
       0  767.14    68.1  744.14    77.8  740.59    97.3  731.73   136.2  712.87
   175.1  692.57   184.8  686.34   194.5  678.22   204.2  669.43     214  662.43
   223.7  657.23   233.4  652.71   262.6  641.65   271.7  635.97     282  629.46
   291.8  626.81   301.5  626.84     321  630.48   331.7  631.79     389  633.43
   505.7  635.77   515.5  636.56   525.2   639.1     603  669.68   641.9  684.16
   651.6  687.32   661.4  689.74   700.2     698   719.7  702.72   739.2  707.97
#Mann= 3 , 0 , 0
       0      .1       0   271.7    .045       0   331.7     .06       0
Bank Sta=271.7,331.7
XS Rating Curve= 0 ,0
Exp/Cntr=0.3,0.1

Type RM Length L Ch R = 1 ,64578   ,278.8,280.6,282.4
XS GIS Cut Line= 2
     1737841.112      593708.244     1737670.611      594427.463
#Sta/Elev= 30
       0  731.11     9.7  727.33    68.1  703.37     107  687.08   116.7  683.17
   126.4  679.87   155.6  671.26   233.4  648.95   243.1  645.64   252.9  639.92
   262.6  632.37   272.3  627.23     282  626.18   291.8   627.6   301.5  630.02
   311.2  631.64     321  632.12   466.8  634.71   476.6   635.2   486.3  637.29
     496   641.3   544.6  666.18   564.1  675.92     603  694.71   612.7  699.12
   622.4  702.43   632.2  704.75   651.6   708.8     710  720.37   739.2  726.81
#Mann= 3 , 0 , 0
       0      .1       0   262.6    .045       0   311.2     .06       0
Bank Sta=262.6,311.2
XS Rating Curve= 0 ,0
Exp/Cntr=0.3,0.1

Type RM Length L Ch R = 1 ,64297.4 ,128.1,131,133.8
XS GIS Cut Line= 3
     1737582.313      593636.027     1737385.802       594337.09
     1737379.803       594358.49
#Sta/Elev= 30
       0  714.88      59  688.14    78.7   679.7    88.6  676.64    98.4  674.42
   177.1  657.52   236.1  644.37     246  641.41   255.8  636.98   265.6  631.12
   275.5  626.55   285.3  625.43   295.2  626.18   314.8  629.96   334.5  631.04
   472.3  634.05   482.1   634.6     492  636.39   501.8  640.03   521.5  649.28
   629.7  702.31   639.5  706.81   649.4     710   659.2  711.81   678.9  713.92
   688.7  714.35   698.6  714.29   718.2  712.93   728.1  712.83   750.3  714.74
#Mann= 3 , 0 , 0
       0      .1       0   265.6    .045       0   314.8     .06       0
Bank Sta=265.6,314.8
XS Rating Curve= 0 ,0
Exp/Cntr=0.3,0.1

Type RM Length L Ch R = 1 ,64166.4 ,98.5,98.5,98.5
XS GIS Cut Line= 4
     1737463.446      593635.045     1737334.094      594005.034
     1737211.192      594112.554     1737120.985       594498.29
#Sta/Elev= 30
       0  694.76    29.4  680.23    39.2  676.83     147  650.72   215.6  639.71
   225.4  636.88   235.2  632.05     245  627.31   254.8  625.22   264.6  625.59
   284.2  628.54   313.6  629.61   420.8  636.38   468.8  638.73   497.6  640.91
   507.2  642.89   555.2  662.57   593.9  681.58   613.2  690.33   642.2  701.65
   671.2  709.88   700.2   716.2   709.8  717.56   758.2  718.21   816.1  721.76
   845.1  722.59   883.8  719.39   912.7  714.04   922.4  712.98   951.4  712.71
#Mann= 3 , 0 , 0
       0      .1       0   235.2    .045       0   284.2     .06       0
Bank Sta=235.2,284.2
XS Rating Curve= 0 ,0
Exp/Cntr=0.3,0.1

Type RM Length L Ch R = 1 ,64067.8 ,152.9,151,149.2
XS GIS Cut Line= 4
     1737370.508      593602.553     1737249.725      593948.031
     1737122.535      594059.303     1737025.117      594475.871
#Sta/Elev= 30
       0  689.51    38.5  674.24   144.5  647.21   163.7   643.7   221.5   640.4
   231.2   637.1   240.8  631.06   250.4   626.4     260  625.15   279.3  629.19
   298.6  632.31   384.8   633.4   450.5  635.93     488  638.36   516.2  641.84
     535  645.63   564.2  655.93   583.6   659.4   593.3  663.48   622.5  679.09
   700.3   705.7   729.4  711.29   768.3  714.12   797.5  715.33   816.9  713.34
   846.1  702.29   865.6  700.91     885   696.1   923.9  683.13   962.8  668.53
#Mann= 3 , 0 , 0
       0     .08       0   240.8    .045       0   279.3     .06       0
Bank Sta=240.8,279.3
XS Rating Curve= 0 ,0
Exp/Cntr=0.3,0.1

Type RM Length L Ch R = 1 ,63916.8 ,436.6,432.2,427.5
XS GIS Cut Line= 2
     1737334.777      593173.991     1736917.871      594528.521
#Sta/Elev= 30
       0  688.42   137.8  679.86     187  679.05   226.4  680.75   344.5  691.55
   364.2  691.77   413.4  676.89   492.1  656.72   521.6  652.69   629.9  626.56
   649.6  624.79   669.2  628.84   679.1  630.48   777.5  632.74   846.4  635.98
     935   644.7     994  664.58  1023.6  670.77  1072.8  685.04  1102.3  690.24
  1141.7  688.54  1161.4  689.34  1171.2  687.82  1249.9  654.36  1269.6  648.77
  1279.4  648.36  1299.1  651.07  1338.5  659.95  1377.9  675.48  1417.2  681.61
#Mann= 3 , 0 , 0
       0     .08       0   629.9    .045       0   669.2     .06       0
Bank Sta=629.9,669.2
XS Rating Curve= 0 ,0
Exp/Cntr=0.3,0.1

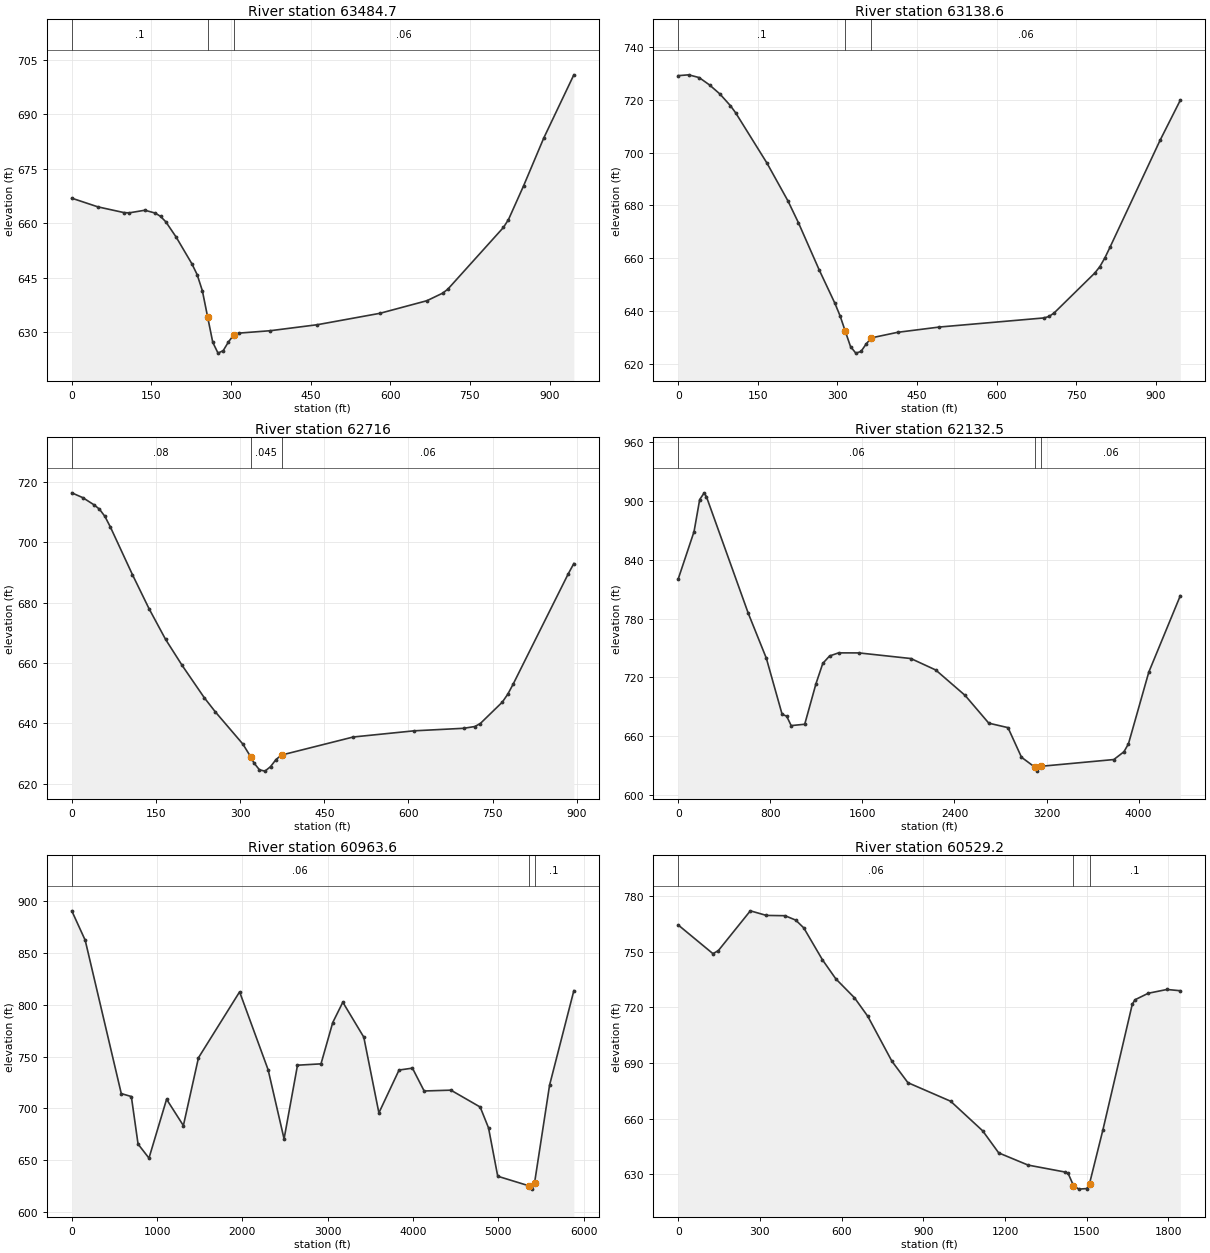
Type RM Length L Ch R = 1 ,63484.7 ,346.1,346.1,346.1
XS GIS Cut Line= 3
     1736825.659       593316.79     1736678.644      594029.792
     1736634.658      594243.118
#Sta/Elev= 30
       0  666.93    49.2  664.54    98.4  662.96   108.2  662.89   137.7  663.61
   157.4  662.82   167.2  661.92   177.1  660.44   196.8  656.18   226.3  648.86
   236.1  645.91     246  641.45   255.8  634.33   265.6  627.25   275.5  624.27
   285.3  624.96   295.1  627.34     305  629.27   314.8  629.78   373.8  630.44
   462.4  632.09   580.4  635.23     669   638.7   698.5  640.77   708.3  641.86
   813.2  658.88   822.7  661.05   851.1  670.32     889  683.45   945.8  700.89
#Mann= 3 , 0 , 0
       0      .1       0   255.8    .045       0     305     .06       0
Bank Sta=255.8,305
XS Rating Curve= 0 ,0
Exp/Cntr=0.3,0.1

Type RM Length L Ch R = 1 ,63138.6 ,425.3,422.6,419.7
XS GIS Cut Line= 3
      1736495.71      593208.223     1736348.695      593921.225
     1736304.709       594134.55
#Sta/Elev= 30
       0  729.12    19.7  729.43    39.4  728.39      59   725.6    78.7  722.14
    98.4  717.73   108.2  715.05   167.2  696.02   206.6  681.76   226.3  673.53
   265.6  655.61   295.1  643.01     305  638.18   314.8  632.35   324.6  626.61
   334.5  624.15   344.3  624.78   354.2  627.66     364  629.93   413.2  632.02
   491.9  634.02   688.6  637.46   698.5  638.01   708.3  639.39   784.8  654.47
   794.3  656.89   803.8  660.22   813.2  664.15   907.9  704.76   945.8  719.84
#Mann= 3 , 0 , 0
       0      .1       0   314.8    .045       0     364     .06       0
Bank Sta=314.8,364
XS Rating Curve= 0 ,0
Exp/Cntr=0.3,0.1

Type RM Length L Ch R = 1 ,62716   ,592.5,583.6,565.7
XS GIS Cut Line= 3
     1736057.172      593142.369     1735954.217      593863.052
     1735930.635      594028.128
#Sta/Elev= 30
       0  716.32    19.7  714.72    39.4  712.38    49.2  710.94      59  708.54
    68.9  704.97   108.2  689.21   137.7  677.98   167.2  667.81   196.8  659.17
   236.1  648.52   255.8  643.83     305  633.14   319.1  628.87   324.6  626.94
   334.5  624.63   344.3   624.2   354.2  625.68     364  628.04   373.8  629.52
   501.7   635.5     610  637.54   698.5  638.38   718.2  638.96     728  639.94
   767.2  647.02     777  649.65   786.8  653.06   884.9  689.54   894.8  692.92
#Mann= 3 , 0 , 0
       0     .08       0   319.1    .045       0   373.8     .06       0
Bank Sta=319.1,373.8
XS Rating Curve= 0 ,0
Exp/Cntr=0.3,0.1

Type RM Length L Ch R = 1 ,62132.5 ,1182.3,1168.8,1156.8
XS GIS Cut Line= 4
      1738251.18      592388.539     1735455.166      593013.484
     1735466.734      593306.122     1735923.932      594420.187
#Sta/Elev= 30
       0  820.45   137.4  868.81   186.4  901.54   225.7   908.4   245.3  904.37
   608.3  785.38   765.3  739.46   902.7  682.08   941.9  680.25   981.2  670.59
  1098.9  671.98    1197  713.52  1255.9  734.15  1314.8  741.72  1393.3   744.9
  1569.9  744.86  2021.2  739.11  2237.1  727.41  2492.2  701.46  2698.2  673.07
    2865  668.51  2982.2  638.27  3099.3  628.05  3118.8  624.08  3148.1  628.98
  3784.5  635.92  3872.6  643.88  3911.7  652.02    4088  725.14  4362.1  803.32
#Mann= 3 , 0 , 0
       0     .06       0  3099.3    .045       0  3148.1     .06       0
Bank Sta=3099.3,3148.1
XS Rating Curve= 0 ,0
Exp/Cntr=0.3,0.1

Type RM Length L Ch R = 1 ,60963.6 ,423.9,434.4,445.4
XS GIS Cut Line= 3
     1736757.674       589356.85     1734760.545      592700.832
     1735472.398      594559.078
#Sta/Elev= 30
       0  890.51   157.4  862.14   580.3  714.24   698.3   711.4     777  665.55
   904.9     652  1111.4  708.78  1308.2  683.38  1485.2  748.82  1967.2  812.36
  2301.6  737.19  2488.4  670.57  2645.8  741.62  2921.2  742.92  3058.9  782.77
    3177  802.37  3422.8  768.67  3599.9  695.63    3836  736.94    3993  738.79
  4130.2  716.76  4443.9  717.55    4787  701.28    4885  681.13  4992.8  634.53
  5355.6  625.37  5394.8   622.1  5424.2  627.96  5600.6  722.45  5884.9  813.52
#Mann= 3 , 0 , 0
       0     .06       0  5355.6    .045       0  5424.2      .1       0
Bank Sta=5355.6,5424.2
XS Rating Curve= 0 ,0
Exp/Cntr=0.3,0.1

Type RM Length L Ch R = 1 ,60529.2 ,460,455.8,451.5
XS GIS Cut Line= 2
      1734686.48       592599.81     1734919.383      594428.966
#Sta/Elev= 30
       0  764.29   127.5  748.86   147.1  750.47   264.8  771.92   323.7  769.45
   392.3  769.29   431.6  766.91     461  762.74   529.6  745.56   578.7  735.31
   647.3  725.11   696.4  715.09   784.6  690.99   843.5   679.4  1000.4  669.42
  1118.1  653.48    1177   641.6  1284.9  635.04  1422.2  631.26    1432  630.55
  1451.6  624.01  1471.2   622.1  1500.6  622.41  1510.4  625.03  1559.5  653.91
  1667.4  721.57  1677.2  724.02  1726.2  727.54  1794.9  729.58  1843.9   728.9
#Mann= 3 , 0 , 0
       0     .06       0  1451.6    .045       0  1510.4      .1       0
Bank Sta=1451.6,1510.4
XS Rating Curve= 0 ,0
Exp/Cntr=0.3,0.1

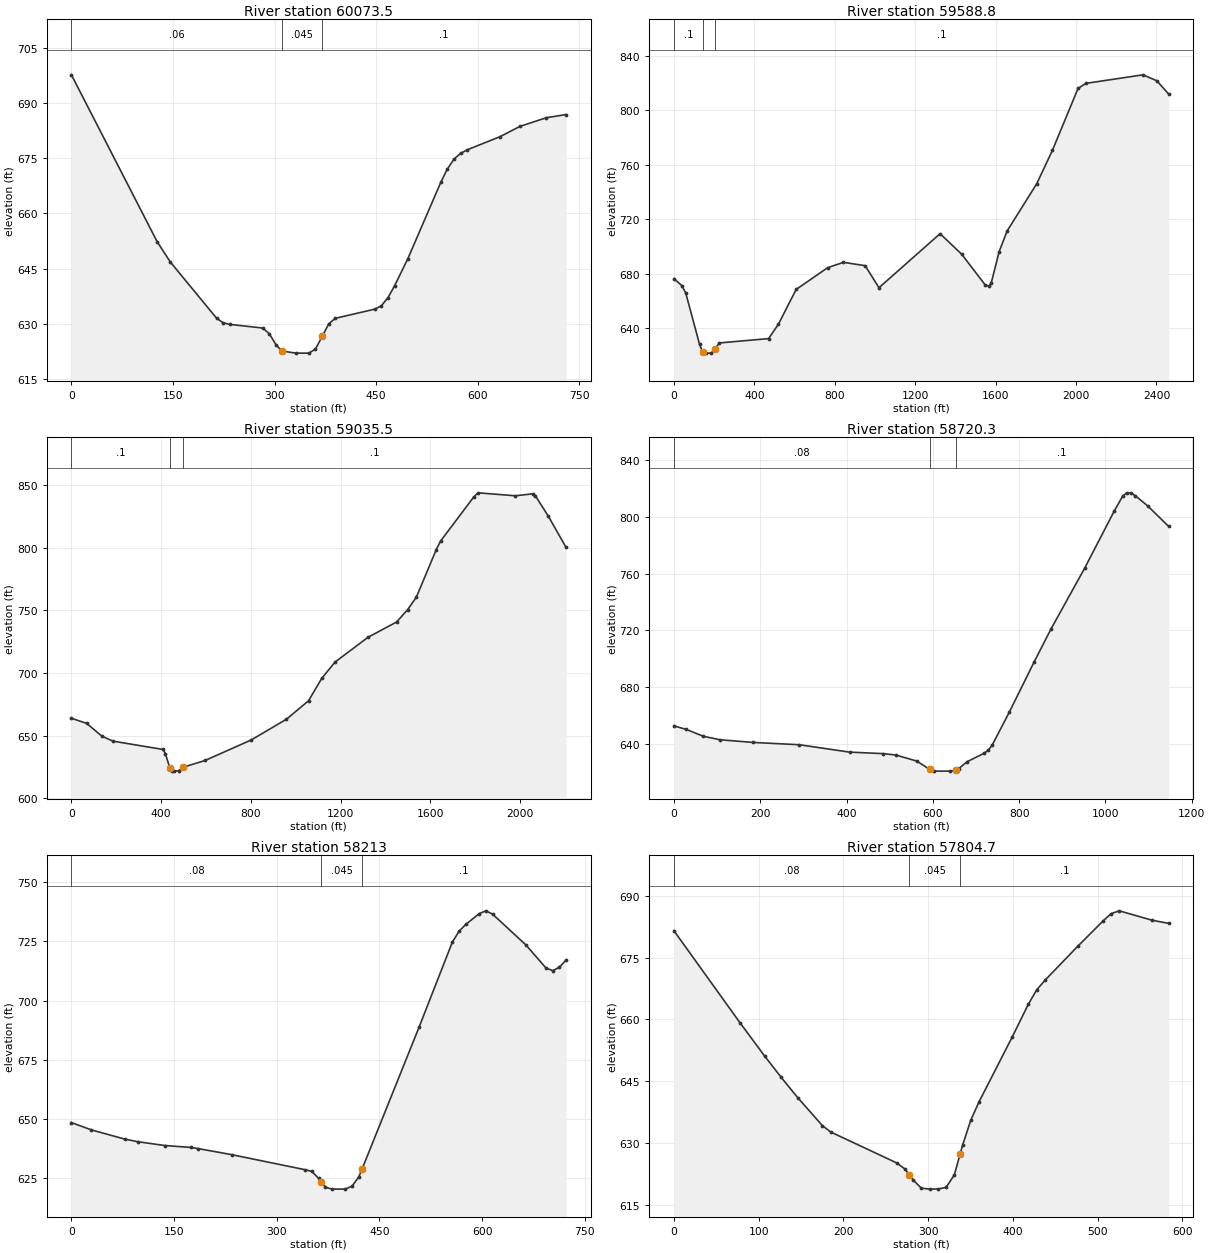
Type RM Length L Ch R = 1 ,60073.5 ,502.2,484.7,467.2
XS GIS Cut Line= 2
     1734356.789      593691.586     1734501.856      594407.608
#Sta/Elev= 30
       0  697.67   126.6  652.31   146.1  646.78   214.3  631.52     224  630.25
   233.8  629.82   282.5  628.82   292.2   627.3     302   624.3   310.6   622.6
   331.2     622   350.7     622   360.4  623.11   370.6  626.61   379.9  629.92
   389.6  631.46   448.1  633.96   457.8  634.88   467.6  637.11   477.3  640.32
   496.8  647.65   545.5  668.44   555.2  672.06     565  674.74   574.7  676.31
   584.5  677.28   633.2  680.87   662.4  683.65   701.4  686.01   730.6  686.87
#Mann= 3 , 0 , 0
       0     .06       0   310.6    .045       0   370.6      .1       0
Bank Sta=310.6,370.6
XS Rating Curve= 0 ,0
Exp/Cntr=0.3,0.1

Type RM Length L Ch R = 1 ,59588.8 ,529.7,553.2,576.7
XS GIS Cut Line= 2
     1733856.821      593892.075     1735259.833      595913.624
#Sta/Elev= 30
       0  676.43    39.2  671.35    58.8  665.84   127.4  628.25   142.2  622.81
   156.9   621.9   186.3   621.9   202.2  624.73   225.5  629.37   470.6  632.54
   519.6  643.14   607.8  668.58   764.7  684.54   843.1  688.42     951     686
  1019.6  669.82  1323.5  709.42  1431.3  694.35    1549  671.69  1568.6  671.08
  1578.4  673.49  1617.6  696.32  1656.8  711.34  1803.9  745.91  1882.3  770.48
  2009.8  815.84    2049  819.58  2333.3  825.84  2401.9  821.44  2460.7  811.74
#Mann= 3 , 0 , 0
       0      .1       0   142.2    .045       0   202.2      .1       0
Bank Sta=142.2,202.2
XS Rating Curve= 0 ,0
Exp/Cntr=0.3,0.1

Type RM Length L Ch R = 1 ,59035.5 ,250.5,315.2,380
XS GIS Cut Line= 3
     1733759.563      593968.477     1733460.843      594218.524
     1733648.239      596024.626
#Sta/Elev= 30
       0   663.8    68.2  659.71   136.4  649.43     185  645.51   409.2  638.83
     419  635.37   439.2  623.86   448.4  621.71   458.3  621.52   477.9  621.82
   499.2   624.7   595.7  630.02   801.8  646.47   958.8  663.05    1057  677.78
  1115.9  695.66  1174.8  708.67    1322  728.53  1449.6  740.79  1498.7  750.59
  1537.9  760.68  1626.3  798.57  1645.9  805.57  1793.1  840.64  1812.8  844.09
  1979.6  841.73  2058.1  843.33    2068  841.86  2126.8  825.19  2205.4  800.38
#Mann= 3 , 0 , 0
       0      .1       0   439.2    .045       0   499.2      .1       0
Bank Sta=439.2,499.2
XS Rating Curve= 0 ,0
Exp/Cntr=0.3,0.1

Type RM Length L Ch R = 1 ,58720.3 ,467.8,507.3,546.9
XS GIS Cut Line= 3
     1733669.258      593975.416     1733446.951       594204.63
     1732689.756      594537.995
#Sta/Elev= 30
       0  652.79      29  650.21    67.7  645.47   106.4     643   183.8  641.09
   290.3  639.49   406.9  634.28   484.8  633.22     514  632.25   562.6     628
   592.7  622.14   601.6   620.9   640.5   620.9   652.7  621.54     660  622.67
   679.4  627.51   718.4  633.42   728.1   635.5   737.8  639.38   776.8  662.19
   835.2  698.05   874.1  721.12     952  763.86  1020.1  803.83  1039.6  814.35
  1049.3  816.84    1059  816.69  1068.8  814.92    1098  807.63  1146.6  793.18
#Mann= 3 , 0 , 0
       0     .08       0   592.7    .045       0   652.7      .1       0
Bank Sta=592.7,652.7
XS Rating Curve= 0 ,0
Exp/Cntr=0.3,0.1

Type RM Length L Ch R = 1 ,58213   ,408.2,408.3,408.4
XS GIS Cut Line= 3
     1733655.367      593954.575     1733514.296      594058.787
     1733064.935      593746.129
#Sta/Elev= 30
       0  648.56    29.2  645.49      78  641.59    97.4  640.48   136.4  638.89
   175.4  638.06   185.2  637.59     234  635.04   341.6  628.67   351.4  627.94
   361.1  625.04     365  623.56   370.9  621.32   380.7  620.48   400.2  620.52
     410  621.71   419.8  625.59     425  629.18   507.8  688.72   556.6  724.74
   566.4  729.34   576.2  732.21   595.7  736.73   605.5  737.94   615.3  736.57
   664.2  723.51   693.5  713.77   703.3  712.69     713  714.15   722.8   717.2
#Mann= 3 , 0 , 0
       0     .08       0     365    .045       0     425      .1       0
Bank Sta=365,425
XS Rating Curve= 0 ,0
Exp/Cntr=0.3,0.1

Type RM Length L Ch R = 1 ,57804.7 ,603.3,577.2,551
XS GIS Cut Line= 2
     1733863.631      593810.226     1733384.353      593476.753
#Sta/Elev= 30
       0  681.47    77.8  659.23     107  651.13   126.5  645.98     146  641.06
   175.2  634.27   184.9  632.73   262.7  625.25   272.5  623.78   277.6  622.38
   282.2  621.12   291.9  619.12   301.7  618.88   311.4  618.91   321.1  619.29
   330.9  622.32   337.6  627.28   340.6   629.5   350.3  635.57   360.1  640.05
     399  655.65   418.4  663.74   428.2  667.18   437.9  669.49   476.8  677.77
     506  683.77   515.8  685.61   525.5  686.31   564.4  684.03   583.9  683.27
#Mann= 3 , 0 , 0
       0     .08       0   277.6    .045       0   337.6      .1       0
Bank Sta=277.6,337.6
XS Rating Curve= 0 ,0
Exp/Cntr=0.3,0.1

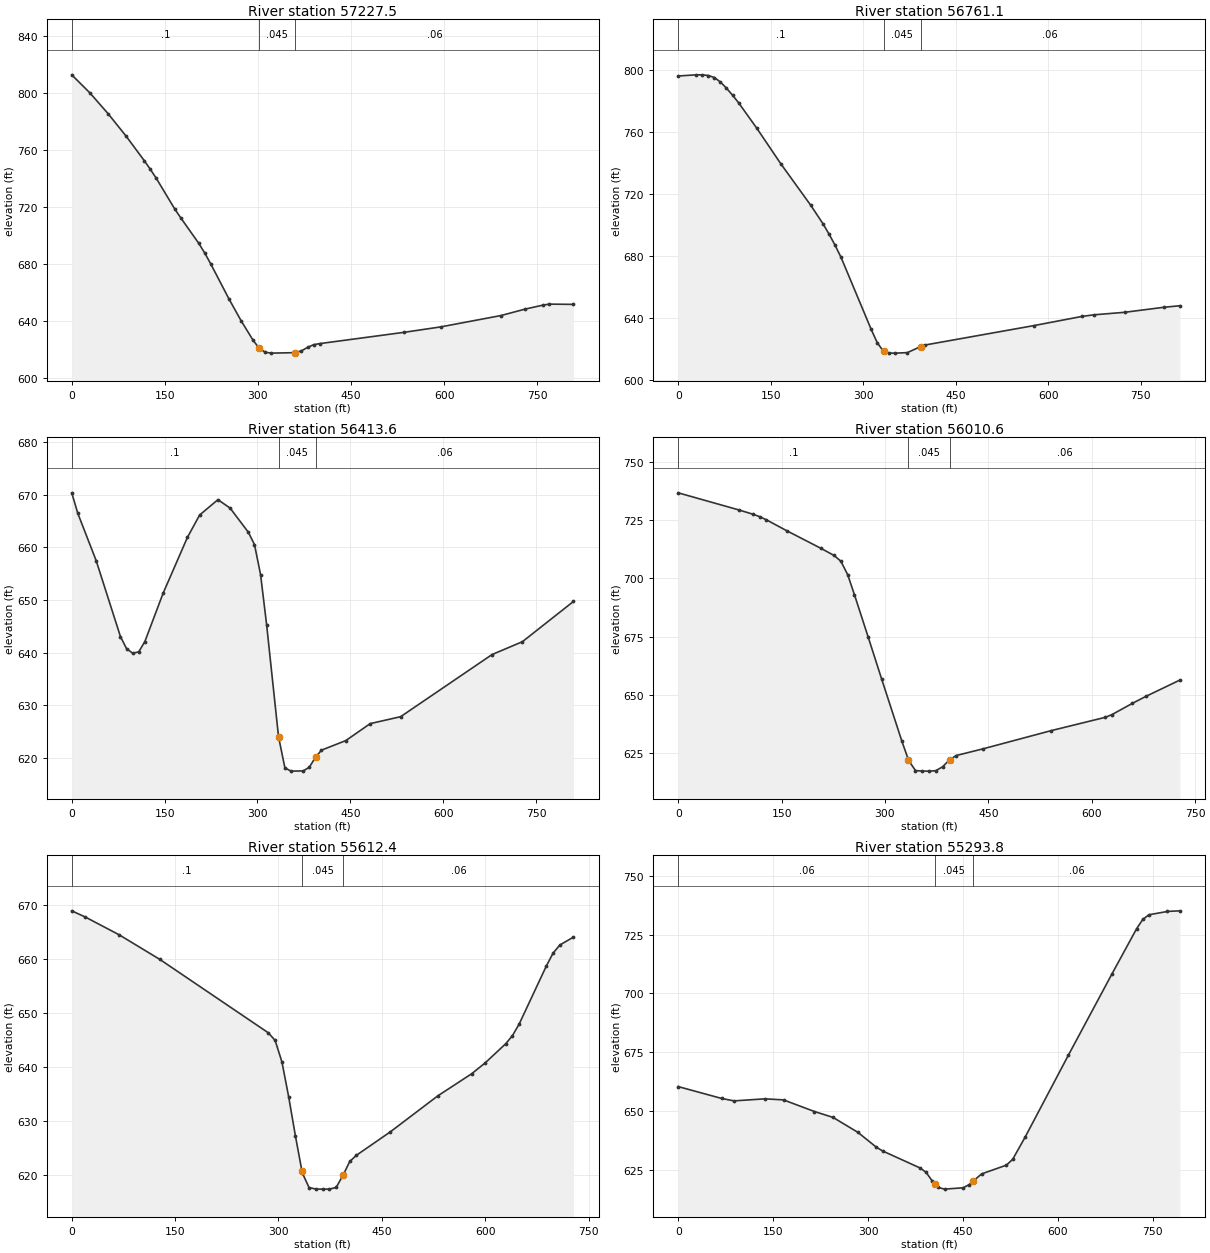
Type RM Length L Ch R = 1 ,57227.5 ,502.5,466.4,430.3
XS GIS Cut Line= 2
     1734293.117      593197.952     1733485.207      593168.282
#Sta/Elev= 30
       0  812.62    29.2  799.97    58.4  785.47    87.7  769.57   116.9  752.42
   126.6   746.4   136.4  739.94   165.6  718.82   175.3  712.56   204.6  694.53
   214.3  687.69     224  680.04   253.2   655.6   272.7  640.36   292.2  626.52
     302  620.99   311.7  618.12   321.4   617.5   360.4  617.84   370.1   619.1
   379.9  621.49   389.6  623.39   399.4  624.16   535.7   632.1   594.2  635.87
   691.6  643.85   730.5  648.36   759.8  651.21   769.5  651.86   808.4  651.68
#Mann= 3 , 0 , 0
       0      .1       0     302    .045       0   360.4     .06       0
Bank Sta=302,360.4
XS Rating Curve= 0 ,0
Exp/Cntr=0.3,0.1

Type RM Length L Ch R = 1 ,56761.1 ,370.8,347.5,324.1
XS GIS Cut Line= 3
     1733980.261      592561.775     1733441.283      593073.228
     1733390.296       593121.61
#Sta/Elev= 30
       0  796.36    29.3  797.11    39.1   797.1    48.9  796.66    58.7  795.37
    68.4  792.48    78.2   788.5      88  784.01    97.8  779.12   127.1  762.82
   166.2  739.77   215.1  712.78   234.6  701.06   244.4  694.41   254.2  687.21
     264  679.28   312.8  632.85   322.6  624.27   332.8  618.62   342.2  617.53
     352   617.5   371.5  617.82   392.8  621.71   400.8  622.78   576.8  635.28
     655  641.22   674.6  642.25   723.5  643.84     787  647.07   813.3  648.09
#Mann= 3 , 0 , 0
       0      .1       0   332.8    .045       0   392.8     .06       0
Bank Sta=332.8,392.8
XS Rating Curve= 0 ,0
Exp/Cntr=0.3,0.1

Type RM Length L Ch R = 1 ,56413.6 ,412.9,403,393.2
XS GIS Cut Line= 3
     1733517.458      592302.943     1733306.119      592999.619
     1733282.193      593078.491
#Sta/Elev= 30
       0  670.35     9.8  666.44    39.4  657.49    78.7  643.04    88.5  640.77
    98.4  639.89   108.2  640.15   118.1   642.1   147.6  651.29   186.9   661.9
   206.6  666.14   236.1  669.05   255.8  667.45   285.3  662.86   295.2  660.52
     305  654.83   314.8  645.29     334  624.06   344.3  618.12   354.2   617.5
   373.8  617.54   383.7  618.23     394  620.18   403.4  621.48   442.7   623.3
   482.1  626.52   531.3  627.84   678.8  639.63     728  642.08   810.4  649.72
#Mann= 3 , 0 , 0
       0      .1       0     334    .045       0     394     .06       0
Bank Sta=334,394
XS Rating Curve= 0 ,0
Exp/Cntr=0.3,0.1

Type RM Length L Ch R = 1 ,56010.6 ,409.1,398.2,387.3
XS GIS Cut Line= 2
     1733040.167      592239.144     1732985.035      592965.053
#Sta/Elev= 30
       0   736.6    88.5  729.23   108.2  727.46     118  726.42   127.9  725.05
   157.4  720.38   206.6   712.9   226.3  709.76   236.1  707.28     246  701.48
   255.8  692.89   275.5  674.97   295.1  656.94   324.6  630.18     334   622.3
   334.5  621.88   344.3  617.66   354.2   617.4     364   617.4   373.8  617.58
   383.7  619.27     394  622.33   403.4  624.08   442.7  626.98   541.1  634.74
   619.8  640.45   629.6  641.64   659.1  646.44   678.8  649.44     728  656.41
#Mann= 3 , 0 , 0
       0      .1       0     334    .045       0     394     .06       0
Bank Sta=334,394
XS Rating Curve= 0 ,0
Exp/Cntr=0.3,0.1

Type RM Length L Ch R = 1 ,55612.4 ,295.7,318.6,341.3
XS GIS Cut Line= 2
     1732556.783      592250.282     1732676.614      592968.361
#Sta/Elev= 30
       0  668.86    19.7  667.71    68.9  664.42   127.9  659.87   285.3   646.3
   295.1   644.9     305  640.92   314.8  634.45   324.6  627.21     334  620.76
   334.5  620.42   344.3   617.7   354.2  617.41     364   617.4   373.8   617.4
   383.7  617.71     394  620.05   403.4  622.51   413.2  623.67   462.4     628
   531.2  634.65   580.4  638.74   600.1  640.76   629.6  644.27   639.5  645.78
   649.3  647.94   688.7  658.66   698.5  661.05   708.3  662.54     728     664
#Mann= 3 , 0 , 0
       0      .1       0     334    .045       0     394     .06       0
Bank Sta=334,394
XS Rating Curve= 0 ,0
Exp/Cntr=0.3,0.1

Type RM Length L Ch R = 1 ,55293.8 ,396.6,427.5,458.6
XS GIS Cut Line= 2
     1732447.223      592247.654     1732186.929      592996.399
#Sta/Elev= 30
       0  660.47    68.5  655.44    88.1   654.4     137  655.27   166.4  654.82
   215.3  649.88   244.7  647.38   283.8  641.06   313.2  634.71     323  633.13
   381.7  625.97   391.5  624.11   401.2  620.47   405.4  619.26     411  617.64
   420.8  616.93   450.2   617.5     460  618.87   465.4  620.25   479.5   623.4
   518.7  627.13   528.5   629.6     548  638.94   616.5  673.81     685  708.14
   724.2  727.45     734  731.45   743.8  733.42   773.1  734.85   792.7   735.1
#Mann= 3 , 0 , 0
       0     .06       0   405.4    .045       0   465.4     .06       0
Bank Sta=405.4,465.4
XS Rating Curve= 0 ,0
Exp/Cntr=0.3,0.1

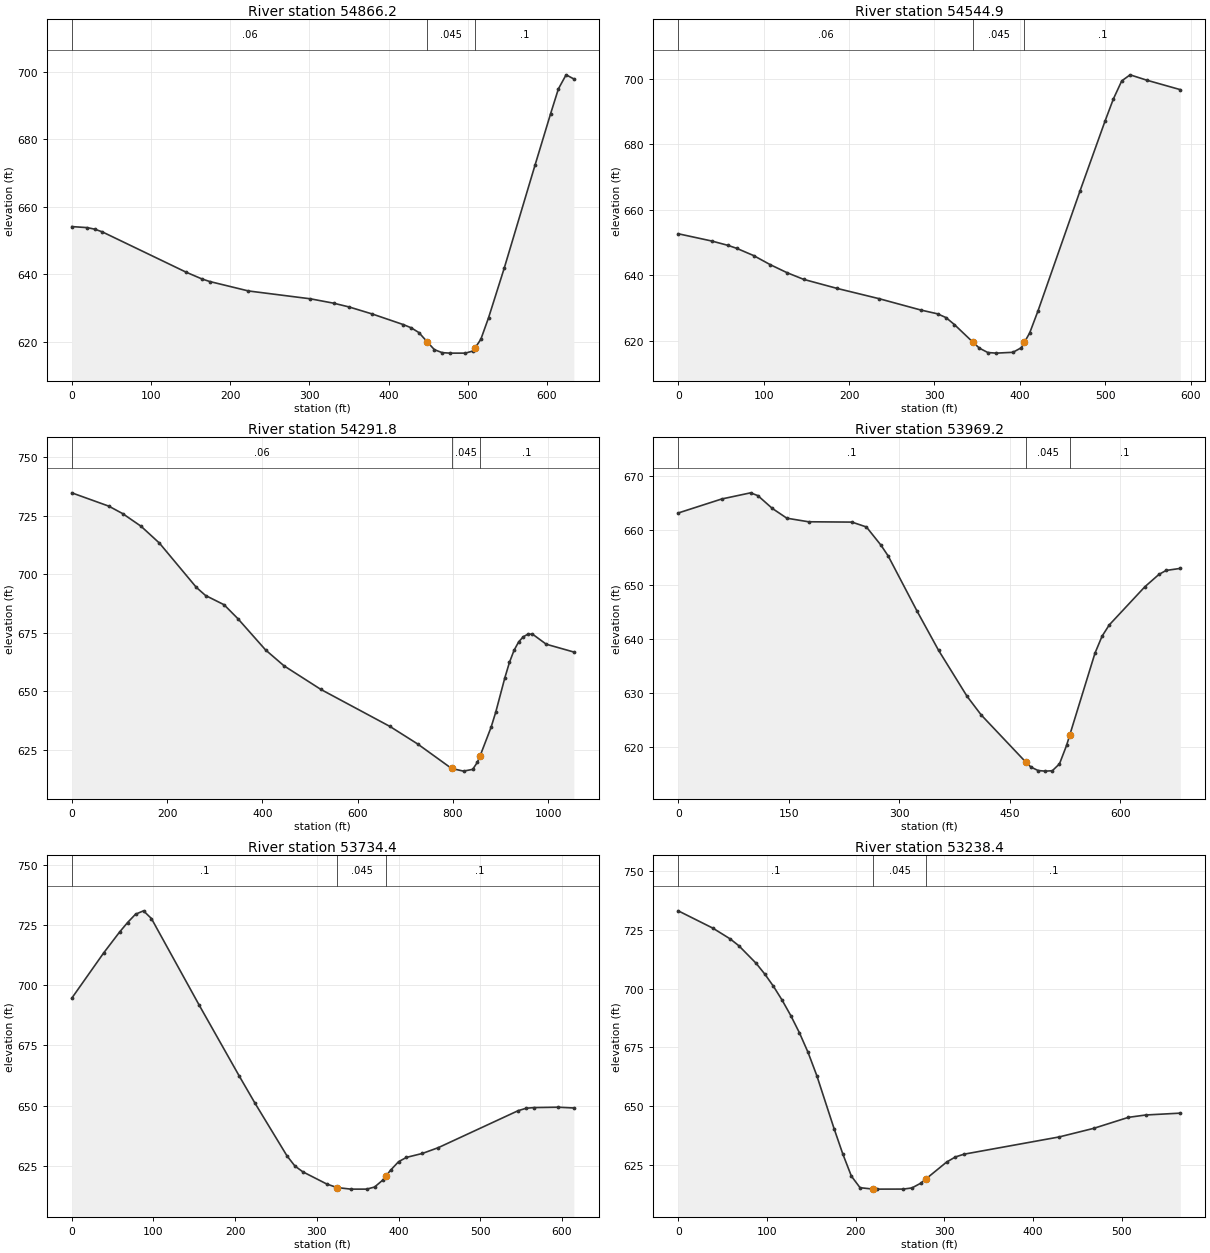
Type RM Length L Ch R = 1 ,54866.2 ,284.1,321.3,358.5
XS GIS Cut Line= 3
     1732342.624      592349.826     1732217.587      592356.761
     1731786.883      592627.636
#Sta/Elev= 30
       0  654.11    19.3  653.81    28.9  653.35    38.5  652.55   144.8  640.55
   164.4  638.59   174.2  637.83   223.1  635.03   301.4   632.7   330.7   631.4
   350.3  630.28   379.6  628.19   418.8  625.05   428.6  624.11   438.3   622.7
   449.1  619.88   457.9  617.63   467.7  616.74   477.5   616.6     497   616.6
   506.8  617.24   509.1  618.06   516.6  620.73   526.4  627.16     546  641.72
   585.1  672.42   604.7  687.61   614.5  694.94   624.2   699.1     634  697.88
#Mann= 3 , 0 , 0
       0     .06       0   449.1    .045       0   509.1      .1       0
Bank Sta=449.1,509.1
XS Rating Curve= 0 ,0
Exp/Cntr=0.3,0.1

Type RM Length L Ch R = 1 ,54544.9 ,251.7,253.1,254.5
XS GIS Cut Line= 2
     1732321.787      592328.984     1731752.189      592183.059
#Sta/Elev= 30
       0  652.69    39.2  650.48    58.8  649.11    68.6  648.23    88.2  646.05
   107.8  643.26   127.4  640.82     147  638.77   186.2  636.01   235.2  632.89
   284.2  629.42   303.8  628.26   313.6  627.12   323.4     625   345.3  619.58
   352.8  617.78   362.6  616.46   372.4  616.28     392  616.53   401.8  617.93
   405.3  619.54   411.6  622.44   421.4  629.21   470.4  665.65   499.8  687.03
   509.6  693.81   519.4  699.32   529.2  701.17   548.8  699.53     588  696.65
#Mann= 3 , 0 , 0
       0     .06       0   345.3    .045       0   405.3      .1       0
Bank Sta=345.3,405.3
XS Rating Curve= 0 ,0
Exp/Cntr=0.3,0.1

Type RM Length L Ch R = 1 ,54291.8 ,326.2,322.6,319
XS GIS Cut Line= 3
      1732717.79       591696.89     1732249.674      592057.192
     1731804.892      591928.376
#Sta/Elev= 30
       0  734.84    77.5  729.16   106.5  725.99   145.3  720.56     184  713.33
   261.5  694.39   280.8  690.92   319.6  686.98   348.6  681.03   406.7  667.65
   445.5  660.84   522.9  650.74   667.9   634.9   725.8  627.44   797.2  616.94
   822.2   615.8   841.5  616.56   851.2  619.55   857.2  622.42   880.1  634.56
   889.8  640.97   909.1  655.82   918.7  662.36   928.4  667.52     938   671.1
   947.7  673.27   957.3  674.36     967   674.4   995.9  670.08  1053.8  666.74
#Mann= 3 , 0 , 0
       0     .06       0   797.2    .045       0   857.2      .1       0
Bank Sta=797.2,857.2
XS Rating Curve= 0 ,0
Exp/Cntr=0.3,0.1

Type RM Length L Ch R = 1 ,53969.2 ,252.4,234.9,217.3
XS GIS Cut Line= 3
     1732495.522      591474.584     1732259.322      591710.743
     1731918.951      591641.249
#Sta/Elev= 30
       0  663.22    58.9   665.8    98.2  666.94   108.1  666.42   127.7  664.06
   147.4  662.26   176.8   661.6   235.8  661.54   255.4  660.64   275.1  657.29
   284.9   655.3   324.2   645.1   353.3  637.89   391.9  629.42   411.2  625.96
   471.4  617.31   478.8  616.34   488.4  615.71   498.1   615.6   507.7  615.67
   517.4  616.94     527  620.33   531.4  622.28   565.6  637.37   575.2  640.49
   584.9  642.56   633.2   649.6   652.4  651.89   662.1  652.62   681.4     653
#Mann= 3 , 0 , 0
       0      .1       0   471.4    .045       0   531.4      .1       0
Bank Sta=471.4,531.4
XS Rating Curve= 0 ,0
Exp/Cntr=0.3,0.1

Type RM Length L Ch R = 1 ,53734.4 ,555.1,496,436.8
XS GIS Cut Line= 2
      1732495.53       591384.28     1731891.178      591495.371
#Sta/Elev= 30
       0   694.6      39  713.36    58.5  722.03    68.3  725.98      78  729.42
    87.8  730.84    97.5  727.64   156.1  691.63   204.8  662.42   224.3  651.02
   263.4  629.21   273.1  624.99   282.8  622.58   312.1  617.52   324.6  616.06
   341.4   615.4   360.9   615.4   370.6  616.27   380.4  619.08   384.6  620.87
   390.1  623.22   399.9  626.76   409.6  628.56   429.2  630.21   448.7  632.62
   546.2  647.92     556  648.94   565.7  649.22     595  649.38   614.5  649.06
#Mann= 3 , 0 , 0
       0      .1       0   324.6    .045       0   384.6      .1       0
Bank Sta=324.6,384.6
XS Rating Curve= 0 ,0
Exp/Cntr=0.3,0.1

Type RM Length L Ch R = 1 ,53238.4 ,425.6,386.4,347.2
XS GIS Cut Line= 2
     1731898.177      590891.029      1731835.61      591453.688
#Sta/Elev= 30
       0  733.09      39  725.74    58.6  721.15    68.3  718.27    87.8   710.8
    97.6  706.21   107.4  700.99   117.1  695.15   126.9  688.56   136.6  681.29
   146.4   672.9   156.2  663.09   175.7  640.53   185.5   629.8   195.2  620.35
     205  615.41   219.8  614.81   224.5   614.8   253.8  614.82   263.5  615.31
   273.3  617.29   279.8  619.29   302.6   626.3   312.4  628.46   322.1  629.64
   429.5  636.98   468.5  640.64   507.6  645.31   527.1  646.31   566.1   647.1
#Mann= 3 , 0 , 0
       0      .1       0   219.8    .045       0   279.8      .1       0
Bank Sta=219.8,279.8
XS Rating Curve= 0 ,0
Exp/Cntr=0.3,0.1

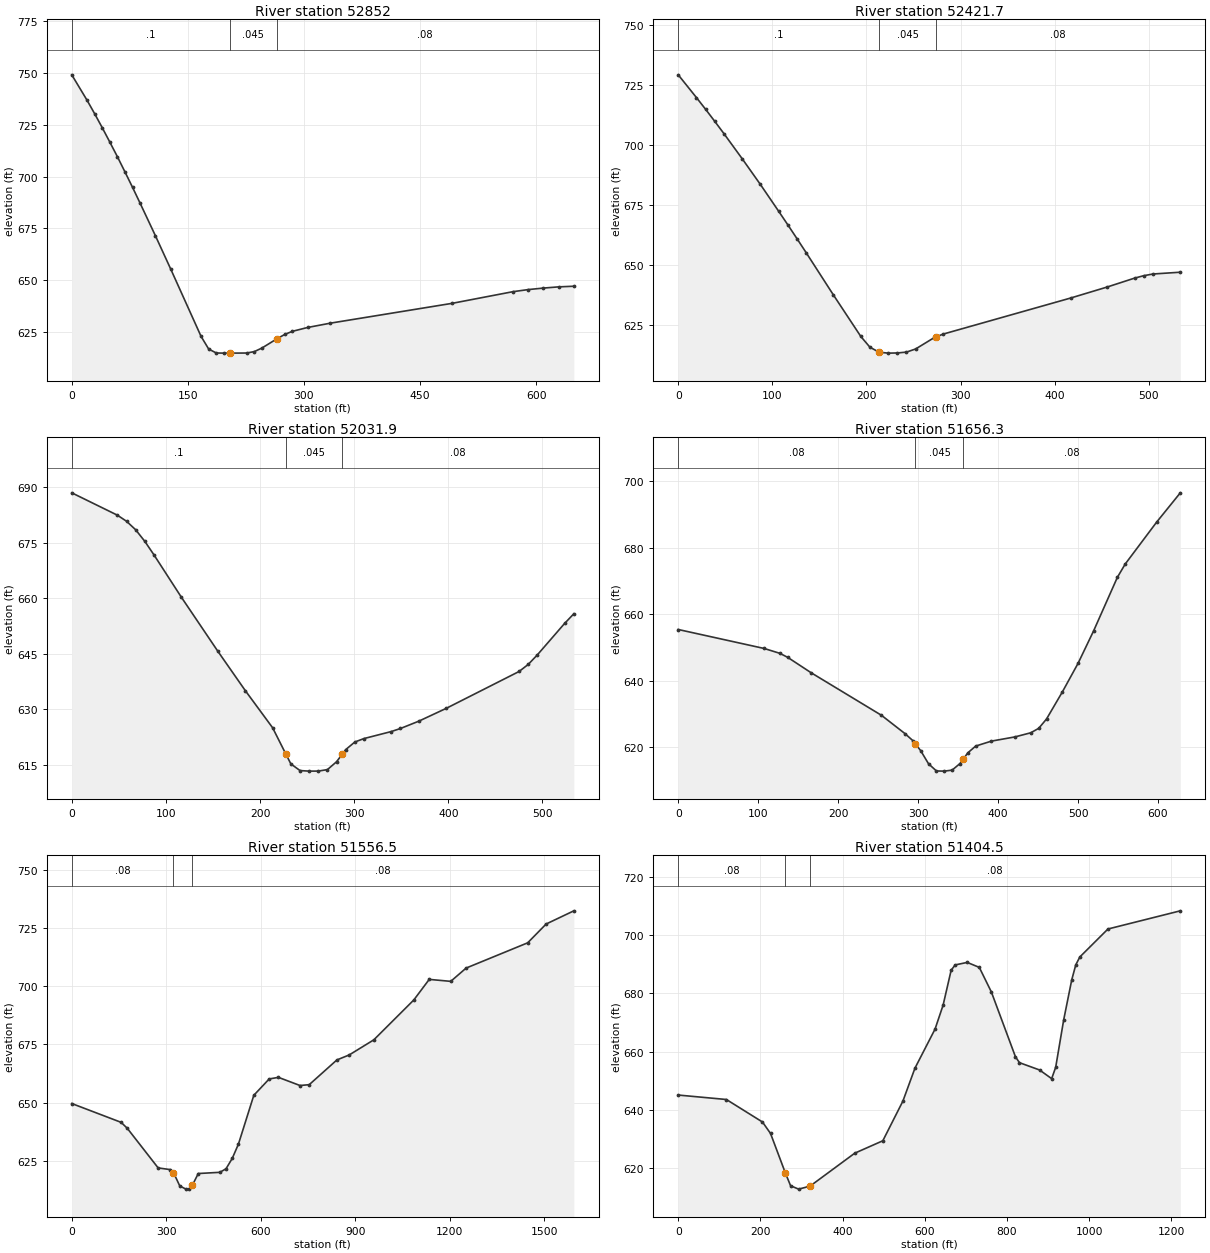
Type RM Length L Ch R = 1 ,52852   ,460.7,430.3,400
XS GIS Cut Line= 2
     1731342.452      590988.232     1731786.984       591460.63
#Sta/Elev= 30
       0  749.13    19.7  736.89    29.5   730.4    39.3  723.66    49.1  716.71
      59  709.57    68.8  702.22    78.6  694.76    88.4  687.09   108.1  671.44
   127.8  655.42   167.1  622.85   176.9  616.77   186.7  614.87   196.6   614.8
   204.7   614.8     226  614.85   235.9  615.54   245.7  617.26   264.7  621.63
   275.2  623.83     285  625.32   304.7  627.18   334.2  629.27   491.4  638.83
     570  644.46   589.7  645.47   609.4   646.2     629  646.78   648.7  647.09
#Mann= 3 , 0 , 0
       0      .1       0   204.7    .045       0   264.7     .08       0
Bank Sta=204.7,264.7
XS Rating Curve= 0 ,0
Exp/Cntr=0.3,0.1

Type RM Length L Ch R = 1 ,52421.7 ,390,389.8,389.5
XS GIS Cut Line= 2
     1731172.459      591526.473     1731700.383       591602.93
#Sta/Elev= 29
       0  729.16    19.4  719.67    29.1  714.81    38.8  709.81    48.5  704.73
    67.9  694.28    87.3  683.55   106.7  672.41   116.4  666.78   126.1  661.05
   135.8  655.25   164.9  637.57     194  620.32   203.7  615.84   213.4  613.79
   213.8  613.77   223.1   613.4   232.8  613.47   242.5  613.83   252.2  615.13
   271.6  619.77   273.8  620.12   281.3   621.3     417  636.33   455.8  640.91
   484.9  644.61   494.6  645.61   504.3  646.31   533.4  647.06
#Mann= 3 , 0 , 0
       0      .1       0   213.8    .045       0   273.8     .08       0
Bank Sta=213.8,273.8
XS Rating Curve= 0 ,0
Exp/Cntr=0.3,0.1

Type RM Length L Ch R = 1 ,52031.9 ,376.8,375.6,373.6
XS GIS Cut Line= 2
     1731127.031      591912.092     1731654.955       591988.55
#Sta/Elev= 30
       0  688.44    48.5   682.4    58.2  680.76    67.9  678.46    77.6  675.34
    87.3   671.7   116.4  660.27   155.2  645.66   184.3  635.06   213.4     625
   227.3  617.98   232.8  615.24   242.5  613.45   252.2   613.3   261.9  613.31
   271.6  613.71   281.3  615.83   287.3  617.85     291   619.1   300.7  621.16
   310.4  622.09   339.5  623.99   349.2  624.81   368.6  626.78   397.6  630.22
   475.2   640.2   484.9   642.1   494.6  644.68   523.7  653.21   533.4  655.79
#Mann= 3 , 0 , 0
       0      .1       0   227.3    .045       0   287.3     .08       0
Bank Sta=227.3,287.3
XS Rating Curve= 0 ,0
Exp/Cntr=0.3,0.1

Type RM Length L Ch R = 1 ,51656.3 ,100.7,99.8,99.6
XS GIS Cut Line= 3
     1731042.112      592180.904     1731290.724      592317.158
     1731633.369      592351.452
#Sta/Elev= 30
       0  655.43   107.5  649.72   127.1  648.26   136.9  647.05   166.2  642.42
   254.2  629.61   283.5  624.12   293.3  622.02   296.7  620.98   303.2  618.98
     313  615.04   322.9  612.87   332.7  612.82   342.5  613.12   352.4  615.11
   356.7  616.52   362.2  618.33     372  620.36   391.7  621.85   421.2  623.12
   440.9  624.36   450.8  625.69   460.6  628.51   480.3  636.61     500  645.24
   519.6  655.08   549.2  671.13     559  675.13   598.3  687.74   627.9  696.55
#Mann= 3 , 0 , 0
       0     .08       0   296.7    .045       0   356.7     .08       0
Bank Sta=296.7,356.7
XS Rating Curve= 0 ,0
Exp/Cntr=0.3,0.1

Type RM Length L Ch R = 1 ,51556.5 ,133.9,152,170
XS GIS Cut Line= 4
     1730994.794      592267.241     1731260.979      592413.126
     1731533.839      592440.436     1732203.163      593204.453
#Sta/Elev= 30
       0  649.57   156.7  641.46   176.2   638.9   274.2  621.83   313.3   621.1
   322.8  619.85   342.7  614.09   362.3   612.7   372.1  612.82   382.8  614.38
   401.5  619.42     470  619.94   489.6  621.48   509.2  625.91   528.8  632.02
   577.8  653.12   626.6  660.16   655.9  660.84   724.3  657.33   753.6  657.69
   841.5  668.35   880.5  670.49   958.7  677.01  1085.6  694.18  1134.5  703.04
  1202.8  702.19  1251.7  707.92    1447  718.79  1505.6  726.89  1593.5  732.57
#Mann= 3 , 0 , 0
       0     .08       0   322.8    .045       0   382.8     .08       0
Bank Sta=322.8,382.8
XS Rating Curve= 0 ,0
Exp/Cntr=0.3,0.1

Type RM Length L Ch R = 1 ,51404.5 ,473.2,479.9,486.6
XS GIS Cut Line= 3
     1730973.147      592405.748     1731444.855      592662.341
     1731667.174      593310.191
#Sta/Elev= 30
       0  645.05   117.2  643.52     205  635.78   224.6  631.85   260.7  618.26
   273.4  613.87   292.9   612.7   320.7  613.72   429.6  625.06   497.9  629.33
   546.8  642.98   576.1   654.3     625  667.73   644.6  675.96   664.2  687.98
     674   689.8   703.3  690.66   732.7  688.95     762  680.52   820.7  658.21
   830.5  656.18   879.4  653.67   908.8  650.69   918.6   654.6   938.2     671
   957.7  684.68   967.5  689.82   977.3  692.52  1045.8  702.15  1221.9   708.4
#Mann= 3 , 0 , 0
       0     .08       0   260.7    .045       0   320.7     .08       0
Bank Sta=260.7,320.7
XS Rating Curve= 0 ,0
Exp/Cntr=0.3,0.1