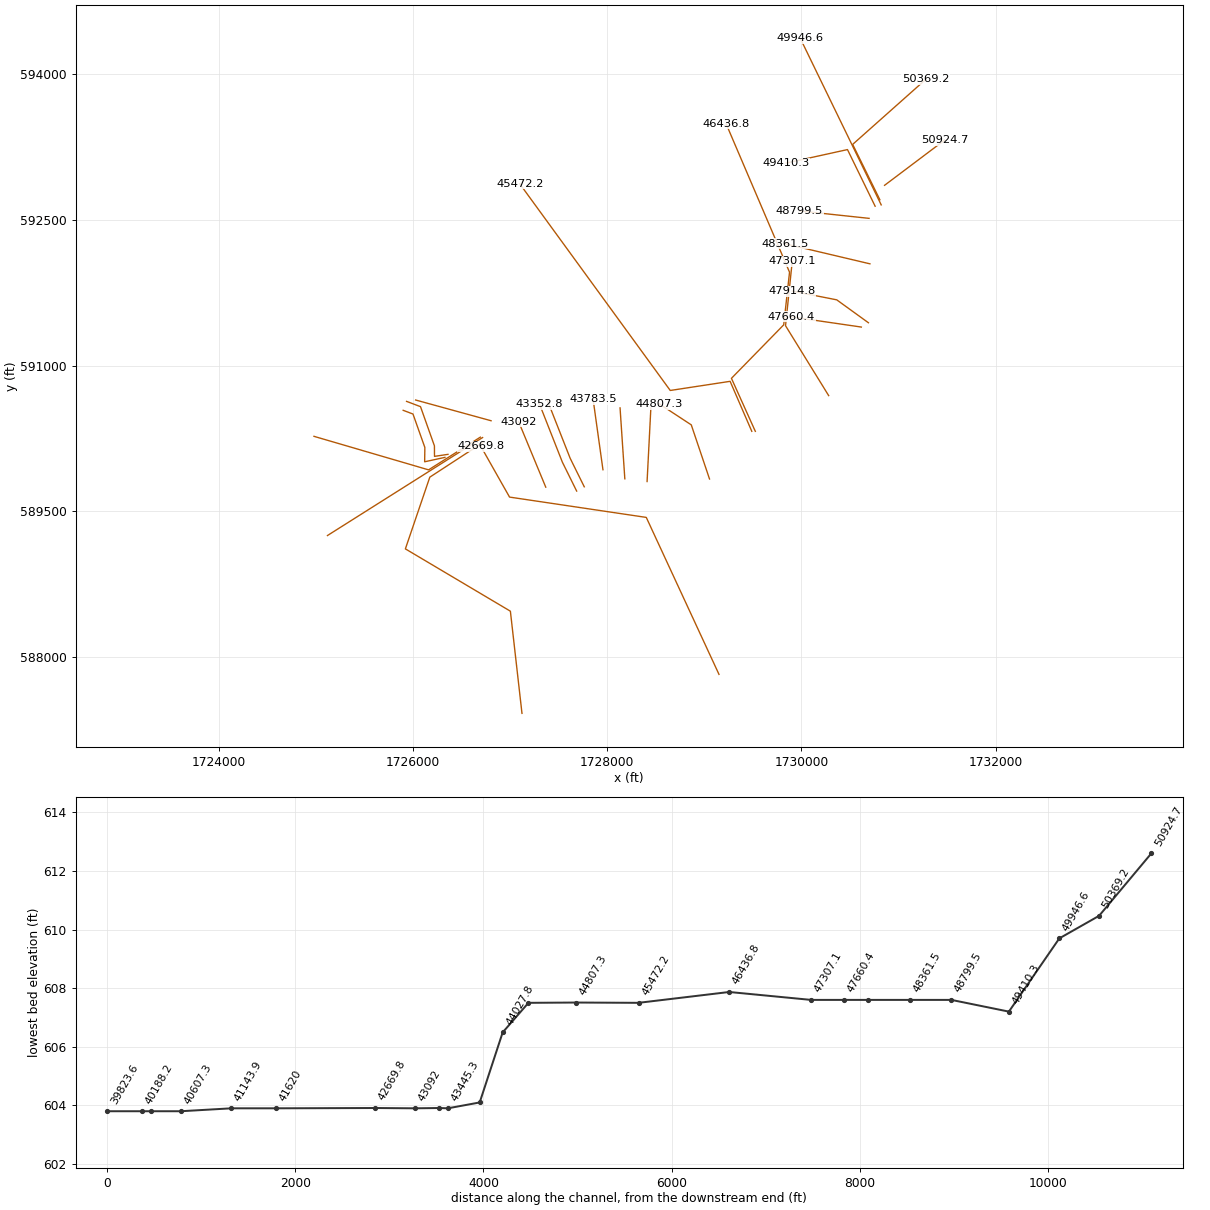
HEC-RAS study EightenmC1.prj: EightenmC1

--- EightenmC1.g01 (geometry) --- (continued)

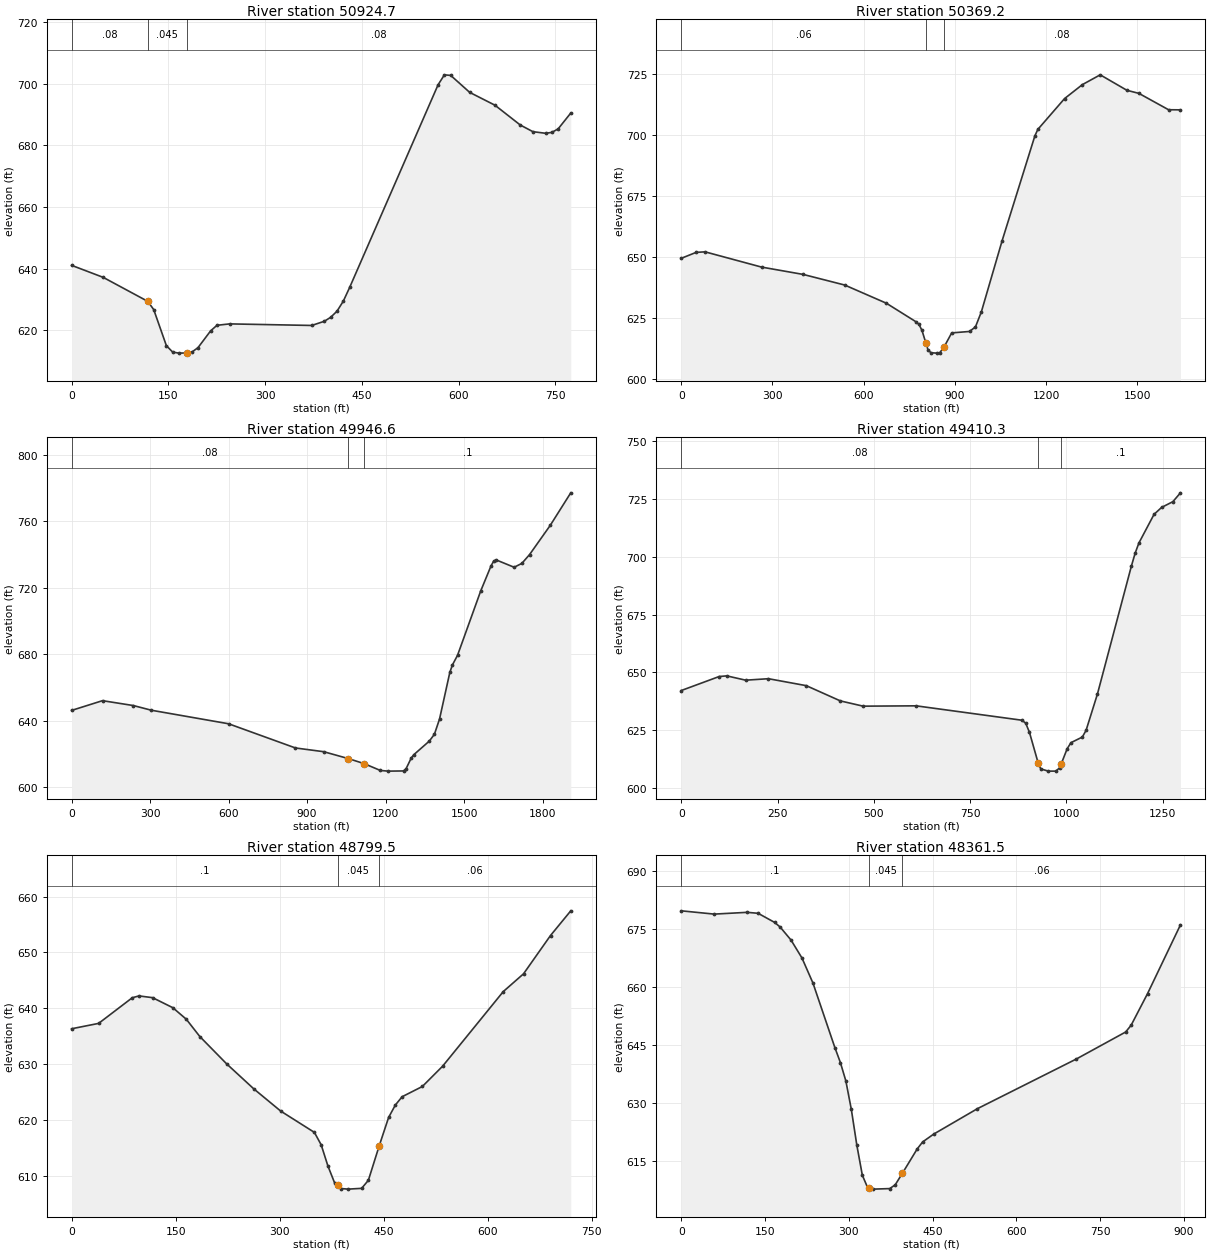
Type RM Length L Ch R = 1 ,50924.7 ,551.8,555.5,559.2
XS GIS Cut Line= 2
     1730856.036      592856.788     1731474.231      593322.255
#Sta/Elev= 30
       0  641.06      49  637.16   118.1  629.38   127.3   626.7   146.9  615.02
   156.7  612.93   166.5   612.6   178.1  612.66   186.1  612.89   195.9  614.37
   215.5  619.82   225.3  621.62   244.9  622.08   372.2  621.57   391.8  622.93
   401.6  624.22   411.4   626.2   421.2  629.46     431  633.89   568.1   699.6
   577.9  702.83   587.7  702.64   617.1  697.14   656.3  692.98   695.5  686.56
   715.1   684.4   734.7  683.88   744.4  684.16   754.2   685.3   773.8  690.44
#Mann= 3 , 0 , 0
       0     .08       0   118.1    .045       0   178.1     .08       0
Bank Sta=118.1,178.1
XS Rating Curve= 0 ,0
Exp/Cntr=0.3,0.1

Type RM Length L Ch R = 1 ,50369.2 ,363.6,422.6,481.6
XS GIS Cut Line= 3
     1730807.566      592708.077     1730527.266      593278.298
     1731279.674       593947.42
#Sta/Elev= 30
       0  649.38    48.9  651.82    78.2  652.03   263.9  645.78   400.8  642.77
   537.6  638.41   674.5  630.96   772.2  623.33     782  622.26   791.8  619.81
   804.2   614.8   811.4  611.93   821.1  610.63   840.7  610.47   850.4  610.66
   864.2  612.92   889.6  618.77   948.2  619.36   967.8  621.23   987.3  627.44
  1055.7  656.67  1163.3  699.62    1173  702.27    1261  714.92  1319.7  720.66
  1378.3  724.67  1466.3  718.31  1505.4  717.07  1603.2  710.34  1642.3   710.3
#Mann= 3 , 0 , 0
       0     .06       0   804.2    .045       0   864.2     .08       0
Bank Sta=804.2,864.2
XS Rating Curve= 0 ,0
Exp/Cntr=0.3,0.1

Type RM Length L Ch R = 1 ,49946.6 ,475.4,536.3,597.2
XS GIS Cut Line= 2
     1730821.322      592655.337     1729987.594       594371.04
#Sta/Elev= 30
       0  646.25     118  652.11     236  649.17   304.8  646.35   599.8  638.21
   855.4  623.64   963.6  621.39  1057.4  617.25  1117.4  614.25  1179.9   610.1
  1209.4   609.7  1268.4  609.81  1278.2  611.17  1297.9  617.57  1307.8   619.6
  1366.8  627.75  1386.4  631.86  1406.1  641.07  1445.4  669.12  1455.2  673.58
  1474.9  679.43  1563.4  718.14  1602.7  733.18  1612.6  736.01  1622.4  736.84
  1691.2  732.41  1720.7  734.74  1750.2  740.05  1828.9  757.56  1907.6  777.21
#Mann= 3 , 0 , 0
       0     .08       0  1057.4    .045       0  1117.4      .1       0
Bank Sta=1057.4,1117.4
XS Rating Curve= 0 ,0
Exp/Cntr=0.3,0.1

Type RM Length L Ch R = 1 ,49410.3 ,626,610.8,595.9
XS GIS Cut Line= 3
     1730758.805      592641.439     1730473.948      593224.916
     1729841.833      593085.931
#Sta/Elev= 30
       0  642.12    98.4  648.18     118  648.46   167.2  646.59   226.3  647.23
   324.6  644.22   413.2  637.61   472.2  635.34     610  635.48   884.6  629.25
   894.5  627.99   904.3  623.99   926.8  610.79   933.7  608.16   953.3   607.2
   972.9   607.2   982.7  608.66   986.8  610.34  1002.3  616.92  1012.1  619.53
  1041.6  621.96  1051.4  624.88  1080.8  640.57    1169  695.98  1178.8   701.6
  1188.6  706.03  1227.9  718.42  1247.5  721.42  1276.9  723.92  1296.5  727.74
#Mann= 3 , 0 , 0
       0     .08       0   926.8    .045       0   986.8      .1       0
Bank Sta=926.8,986.8
XS Rating Curve= 0 ,0
Exp/Cntr=0.3,0.1

Type RM Length L Ch R = 1 ,48799.5 ,443.1,438.1,432.6
XS GIS Cut Line= 2
     1730696.297      592516.397     1729980.805      592592.745
#Sta/Elev= 30
       0  636.32    38.9  637.28    87.5  641.88    97.2   642.2   116.7  641.89
   145.9  640.09   165.3  638.03   184.8  634.93   223.6  630.02   262.5  625.57
   301.4  621.58     350  617.76   359.8  615.53   369.5  611.74   379.2   608.7
   383.4  608.27     389   607.7   398.7   607.6   418.1  607.74   427.8  609.18
   443.4  615.34     457  620.44   466.7  622.66   476.5  624.15   505.6  625.98
   534.8  629.61   622.3  642.98   651.5  646.16   690.4  653.02   719.6  657.44
#Mann= 3 , 0 , 0
       0      .1       0   383.4    .045       0   443.4     .06       0
Bank Sta=383.4,443.4
XS Rating Curve= 0 ,0
Exp/Cntr=0.3,0.1

Type RM Length L Ch R = 1 ,48361.5 ,445,446.7,448.5
XS GIS Cut Line= 2
     1730705.206      592047.982     1729835.248      592253.472
#Sta/Elev= 30
       0  679.66    58.9  678.81   117.9  679.27   137.5  679.02     167  676.67
   176.8  675.49   196.5  672.09   216.1  667.44   235.8  660.94     275  644.25
   284.9  640.37   294.7   635.6   304.5  628.22   314.3     619   324.2  611.19
     334  607.88   335.7  607.83   343.8   607.6   373.3  607.74   383.1  608.72
   395.7  611.65   422.4     618   432.2  619.82   451.9  621.84   530.4  628.44
   707.3  641.28   795.7  648.28   805.5  650.02     835  658.23   893.9  676.03
#Mann= 3 , 0 , 0
       0      .1       0   335.7    .045       0   395.7     .06       0
Bank Sta=335.7,395.7
XS Rating Curve= 0 ,0
Exp/Cntr=0.3,0.1

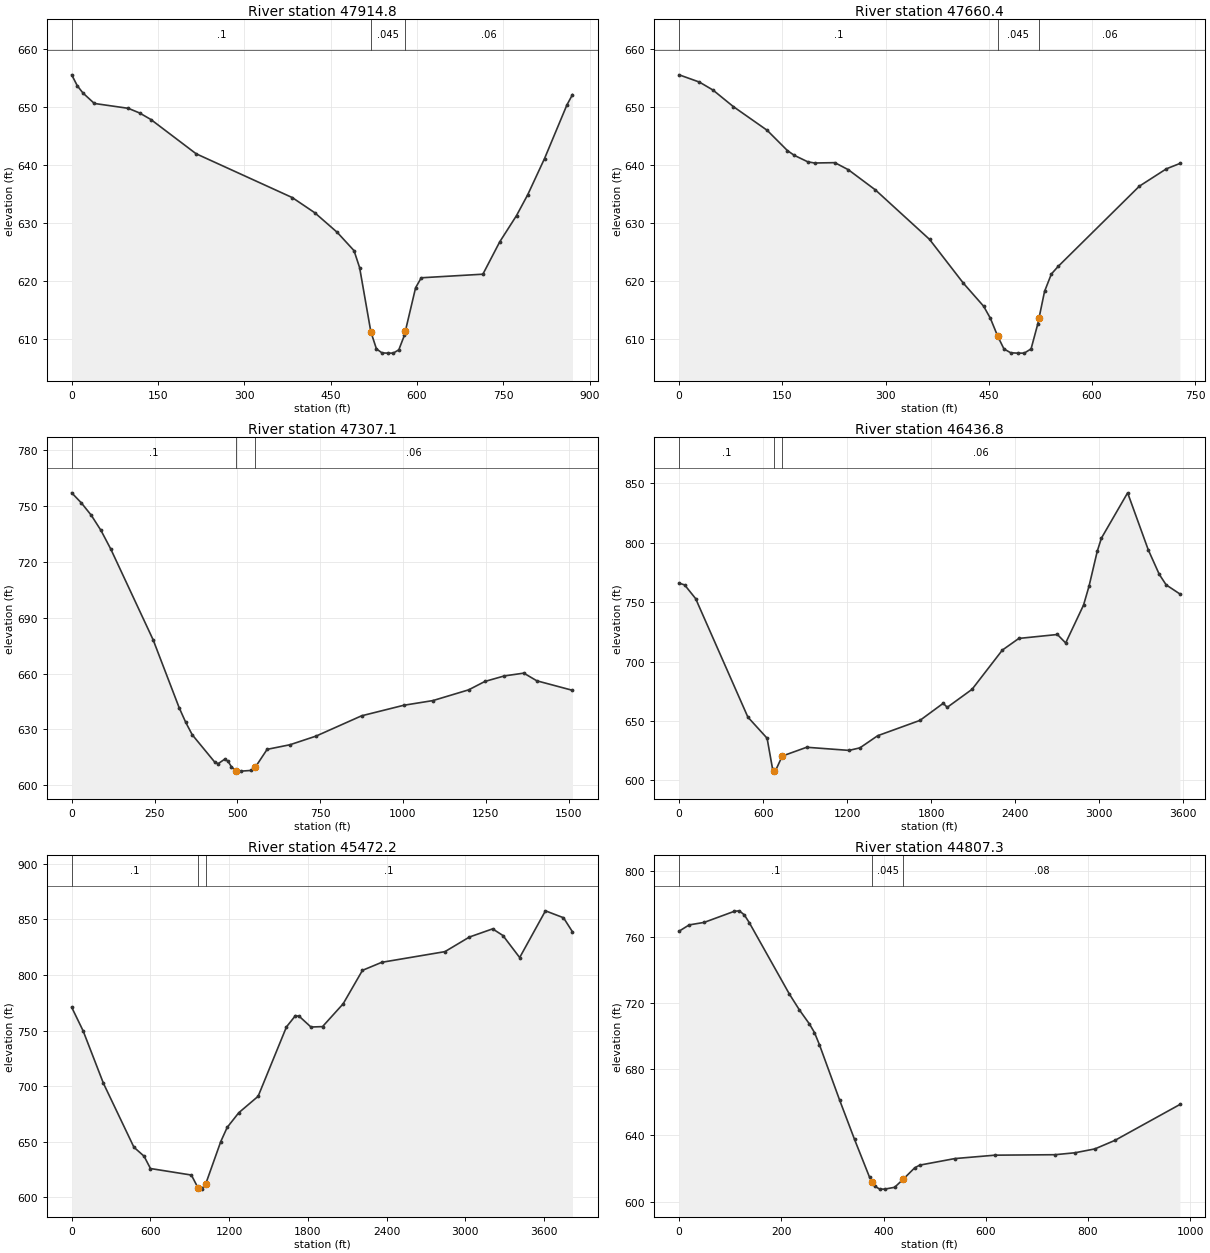
Type RM Length L Ch R = 1 ,47914.8 ,252,254.4,256.7
XS GIS Cut Line= 3
     1730689.733      591440.811     1730363.229      591676.962
     1729904.755      591767.226
#Sta/Elev= 30
       0  655.62     9.8  653.72    19.7  652.47    39.3  650.68    98.3  649.84
   117.9  649.04   137.6  647.91   216.2     642   383.3  634.44   422.4  631.82
   461.4  628.44   490.6  625.28   500.3  622.35   519.8  611.29   529.5  608.33
   539.2  607.64     549   607.6   558.7   607.6   568.4  608.17   578.2   610.7
   579.8  611.41   597.6  618.89   607.4   620.6   714.5  621.22   743.7  626.79
   772.9  631.33   792.4  634.93   821.6  641.17   860.5  650.42   870.2  652.21
#Mann= 3 , 0 , 0
       0      .1       0   519.8    .045       0   579.8     .06       0
Bank Sta=519.8,579.8
XS Rating Curve= 0 ,0
Exp/Cntr=0.3,0.1

Type RM Length L Ch R = 1 ,47660.4 ,398.8,353.3,307.9
XS GIS Cut Line= 2
      1730616.72      591396.498     1729896.326      591501.459
#Sta/Elev= 30
       0  655.48    29.5  654.23    49.2  652.86    78.7  650.02   127.9  645.94
   157.4  642.45   167.2  641.64   186.9  640.52   196.8  640.31   226.3  640.37
     246  639.15   285.3  635.68     364  627.17   413.2  619.63   442.7  615.66
   452.5  613.58   463.2  610.48   472.2  608.32     482  607.66   491.9   607.6
   501.7   607.6   511.6  608.33   521.4  612.64   523.2  613.66   531.2  618.22
   541.1  621.21   550.9  622.51     669  636.32   708.3  639.31     728  640.23
#Mann= 3 , 0 , 0
       0      .1       0   463.2    .045       0   523.2     .06       0
Bank Sta=463.2,523.2
XS Rating Curve= 0 ,0
Exp/Cntr=0.3,0.1

Type RM Length L Ch R = 1 ,47307.1 ,924.8,870.3,815.9
XS GIS Cut Line= 3
     1730279.957      590690.558     1729835.765       591410.22
     1729904.728       592072.87
#Sta/Elev= 30
       0  757.22    29.5  751.73      59  745.18    88.5  736.97     118  726.97
   245.8  678.21   324.5  641.66   344.2  633.84   363.8  627.17   432.7  612.26
   442.5  611.64   462.2  614.06     472  612.88   481.9  610.02   494.5  607.86
   511.4   607.6   540.9  607.96   554.5  609.76     590  619.31   658.9  621.78
   737.5  626.42   875.1  637.34  1002.5  643.01  1090.6  645.53  1198.4   651.3
  1247.4  655.81  1306.2  658.79    1365  660.28  1404.2  656.16  1511.9  651.04
#Mann= 3 , 0 , 0
       0      .1       0   494.5    .045       0   554.5     .06       0
Bank Sta=494.5,554.5
XS Rating Curve= 0 ,0
Exp/Cntr=0.3,0.1

Type RM Length L Ch R = 1 ,46436.8 ,850.4,964.5,1078.4
XS GIS Cut Line= 5
     1729524.563       590322.33     1729278.359      590868.347
     1729816.943      591419.276     1729876.952      591961.724
      1729223.85      593489.887
#Sta/Elev= 30
       0   766.1    39.3  764.58   117.8  753.07     491  653.33   628.2  635.57
   667.2  609.77   676.4  608.01   686.7  607.87   736.4  620.55     911  627.96
  1213.4  625.32  1291.4  627.47  1418.1  637.68  1720.2  650.59  1885.9  664.93
  1915.2  661.59  2092.2  676.73  2308.5  709.74  2426.5  719.56  2701.8  722.87
  2760.8  715.73  2888.7  747.67    2928  763.69    2987  793.22  3016.5  804.03
  3203.4  842.11  3350.9  794.11  3429.5  773.48  3478.7  764.63    3577  756.96
#Mann= 3 , 0 , 0
       0      .1       0   676.4    .045       0   736.4     .06       0
Bank Sta=676.4,736.4
XS Rating Curve= 0 ,0
Exp/Cntr=0.3,0.1

Type RM Length L Ch R = 1 ,45472.2 ,728,664.9,601.7
XS GIS Cut Line= 4
     1729488.094      590322.327     1729264.836      590837.427
      1728647.98      590743.256      1727098.29      592871.463
#Sta/Elev= 30
       0  770.94    87.1  749.77     242  702.59   474.3  645.18   551.7   637.1
   600.4  626.02   912.4  620.16   962.6  608.73   990.4   607.5  1022.6  612.49
  1136.6   650.3  1185.4     663  1273.8  676.18  1421.2  690.94  1637.3  753.32
    1706   763.5  1735.5  762.78  1823.9  753.22  1912.3  753.59  2069.5  774.09
  2216.8  804.18  2364.2   811.4  2845.5  820.98  3032.2  834.12    3209  841.45
  3287.6  835.49  3415.3  815.67  3611.8  857.67  3749.3  851.46    3818  838.78
#Mann= 3 , 0 , 0
       0      .1       0   962.6    .045       0  1022.6      .1       0
Bank Sta=962.6,1022.6
XS Rating Curve= 0 ,0
Exp/Cntr=0.3,0.1

Type RM Length L Ch R = 1 ,44807.3 ,522.4,505.4,488.4
XS GIS Cut Line= 3
     1729052.586      589831.254     1728864.633      590388.855
     1728537.274      590603.575
#Sta/Elev= 30
       0  763.74    19.6  767.52      49  769.05   107.9  775.76   117.7  776.05
   127.5  773.62   137.3  768.86   215.8   725.6   235.4     716     255   707.5
   264.8  702.34   274.6   694.9   313.8  661.61   343.2  637.61   372.7  614.62
   378.2  611.68   382.5  609.38   392.3  607.54   402.1  607.51   421.7  608.62
   438.2  613.44   460.9  620.41   470.7  622.04   539.4  626.01   617.8  628.07
   735.2  628.35   774.4  629.52   813.5  631.87   852.7  637.04   979.9  658.78
#Mann= 3 , 0 , 0
       0      .1       0   378.2    .045       0   438.2     .08       0
Bank Sta=378.2,438.2
XS Rating Curve= 0 ,0
Exp/Cntr=0.3,0.1

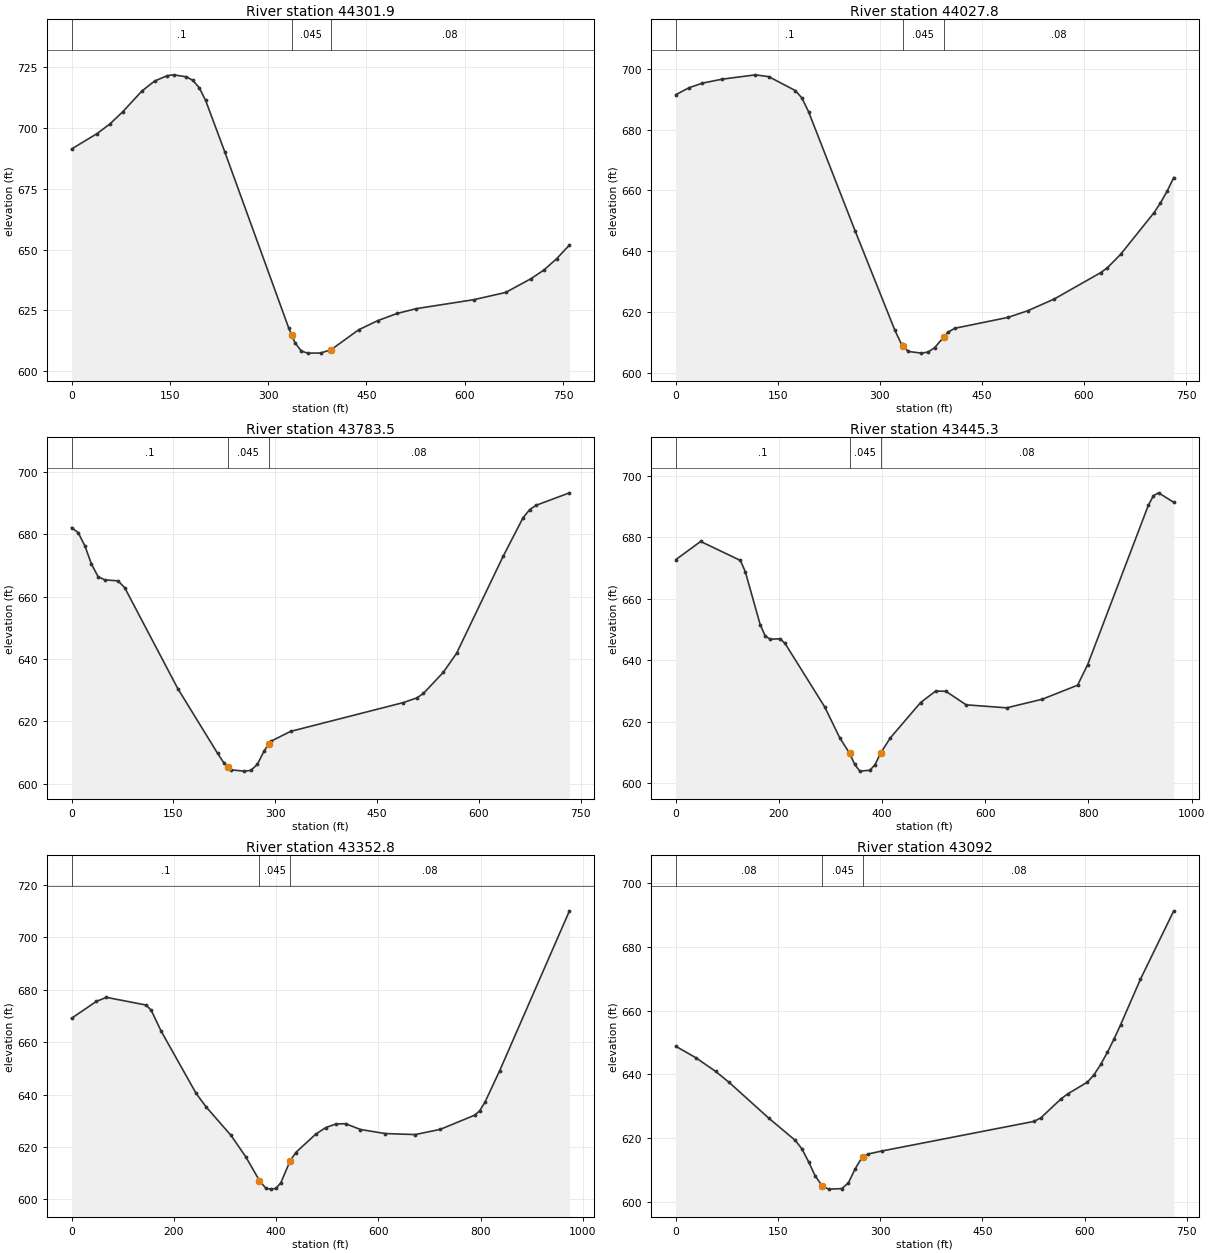
Type RM Length L Ch R = 1 ,44301.9 ,268.7,274,280.4
XS GIS Cut Line= 2
     1728409.362      589805.138     1728448.389      590563.891
#Sta/Elev= 30
       0  691.28      39  697.63    58.4  701.54    77.9  706.51   107.2  715.04
   126.6  719.16   146.1   721.4   155.8  721.73   175.3  720.92   185.1  719.44
   194.8  716.45   204.6  711.21   233.8  690.13   331.2  617.95     336   614.9
   340.9  611.78   350.7  608.33   360.4   607.5   379.9  607.54     396   608.9
   438.3  617.11   467.5  620.87   496.8  623.78     526  625.76   613.6  629.43
   662.4   632.4   701.3  638.09   720.8  641.61   740.3  646.28   759.8  651.87
#Mann= 3 , 0 , 0
       0      .1       0     336    .045       0     396     .08       0
Bank Sta=336,396
XS Rating Curve= 0 ,0
Exp/Cntr=0.3,0.1

Type RM Length L Ch R = 1 ,44027.8 ,241.1,244.3,246.5
XS GIS Cut Line= 2
     1728180.034      589833.444     1728130.943      590563.766
#Sta/Elev= 30
       0  691.47    19.5  693.75      39  695.26    68.3  696.57   117.1  697.99
   136.6  697.39   175.7  692.81   185.4  690.36   195.2  685.82   263.5  646.73
   322.1  613.96   331.8  609.39   333.6  608.96   341.6  607.05   361.1  606.49
   370.9  606.85   380.6   608.3   393.6  611.72   400.1  613.36   409.9  614.65
     488  618.22   517.3  620.42   556.3  624.28   624.6  632.95   634.4  634.54
   653.9  638.97   702.7  652.57   712.4  655.85   722.2   659.7     732  664.23
#Mann= 3 , 0 , 0
       0      .1       0   333.6    .045       0   393.6     .08       0
Bank Sta=333.6,393.6
XS Rating Curve= 0 ,0
Exp/Cntr=0.3,0.1

Type RM Length L Ch R = 1 ,43783.5 ,326.8,338.3,349.3
XS GIS Cut Line= 2
     1727954.725      589926.996     1727853.121      590653.137
#Sta/Elev= 30
       0  682.09     9.8  680.48    19.6  676.25    29.3  670.43    39.1  666.37
    48.9  665.35    68.4  665.04    78.2  662.87   156.4  630.55   215.1  609.78
   224.8  606.57   230.3  605.41   234.6  604.51   254.2   604.1     264  604.32
   273.7  606.29   283.5  610.56   290.3   612.7   293.3  613.65   322.6  616.83
   488.8  626.07   508.4  627.55   518.1  628.97   547.5  635.77     567  641.86
   635.4  672.85   664.8  685.22   674.6  687.86   684.3  689.26   733.2  693.23
#Mann= 3 , 0 , 0
       0      .1       0   230.3    .045       0   290.3     .08       0
Bank Sta=230.3,290.3
XS Rating Curve= 0 ,0
Exp/Cntr=0.3,0.1

Type RM Length L Ch R = 1 ,43445.3 ,93,92.5,92.4
XS GIS Cut Line= 3
     1727762.148      589750.757     1727617.163      590044.114
     1727383.426      590637.827
#Sta/Elev= 30
       0  672.79    48.1  678.71   125.1  672.53   134.7  668.84   163.6  651.59
   173.2  647.95   182.9  646.85   202.1  647.02   211.7   645.5   288.7   624.8
   317.6  614.81   336.9  609.72   346.9  606.06   356.7   603.9   376.3  604.19
   386.1     606   396.9  609.71   415.6  614.69   474.5  626.24   503.9  629.99
   523.6   629.9   562.8   625.5   641.4  624.52   710.1  627.31   778.8  631.88
   798.4  638.58   916.2  690.55     926  693.62   935.8  694.55   965.3  691.45
#Mann= 3 , 0 , 0
       0      .1       0   336.9    .045       0   396.9     .08       0
Bank Sta=336.9,396.9
XS Rating Curve= 0 ,0
Exp/Cntr=0.3,0.1

Type RM Length L Ch R = 1 ,43352.8 ,259.8,260.8,261.8
XS GIS Cut Line= 3
     1727683.653      589707.136     1727536.835      590004.201
     1727301.583      590601.762
#Sta/Elev= 30
       0  669.13    48.7  675.59    68.2  677.11   146.2  674.16   155.9  672.11
   175.4  664.14   243.6  640.44   263.1   635.3   311.9  624.39   341.1  616.12
   367.4  607.17     380  604.23   389.8  603.91   399.5  604.16   409.2  606.34
   427.4  614.73   438.4  617.88   477.3  624.87   496.8  627.38   516.2  628.74
   535.7   628.9   564.9  626.67   613.5  625.12   671.9  624.74   720.6   626.7
   788.7  632.17   798.4  633.92   808.2  637.03   837.3  649.19   973.6  710.14
#Mann= 3 , 0 , 0
       0      .1       0   367.4    .045       0   427.4     .08       0
Bank Sta=367.4,427.4
XS Rating Curve= 0 ,0
Exp/Cntr=0.3,0.1

Type RM Length L Ch R = 1 ,43092   ,416.8,422.2,427.6
XS GIS Cut Line= 2
     1727365.502      589747.043     1727085.857       590422.17
#Sta/Elev= 30
       0  648.81    29.2  645.23    58.5  640.91      78   637.5   136.4  626.22
   175.4  619.21   185.1  616.54   194.9  612.48   204.6  608.02     215  604.89
   224.1   603.9   243.6  604.06   253.3  605.87   263.1  610.24   272.8   613.7
     275  613.98   282.6  614.96     302  615.87   526.1  625.22   535.9  626.34
   565.1  632.23   574.9  633.81   604.1  637.54   613.8  639.88   623.6   643.1
   633.3  646.89   643.1  651.06   652.8  655.59     682  669.93   730.8   691.4
#Mann= 3 , 0 , 0
       0     .08       0     215    .045       0     275     .08       0
Bank Sta=215,275
XS Rating Curve= 0 ,0
Exp/Cntr=0.3,0.1

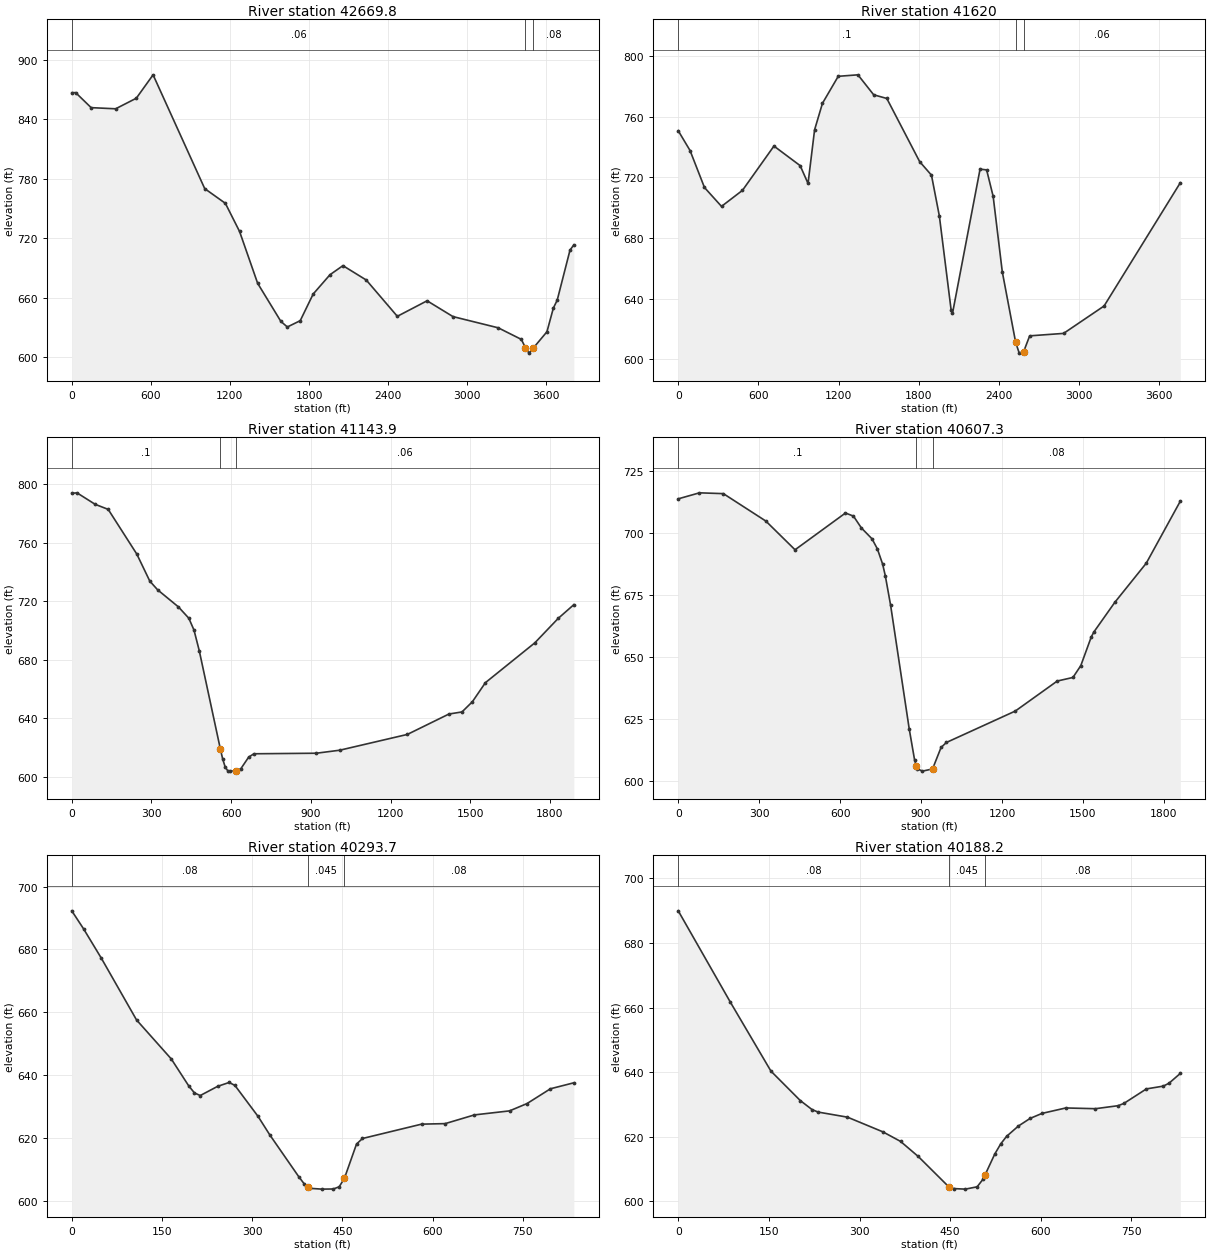
Type RM Length L Ch R = 1 ,42669.8 ,1092,1049.8,974.9
XS GIS Cut Line= 4
     1729150.171       587818.35     1728401.118      589435.505
     1726992.531      589644.828     1726695.636      590169.261
#Sta/Elev= 30
       0  866.55    29.4  866.67   146.9  851.51   332.9  850.35   489.6  861.01
   616.9  884.61  1008.6  769.84  1165.3     755    1273  726.61  1410.1  674.34
  1586.4  635.91  1635.3  630.28  1733.2  636.64  1831.3  663.51    1959     683
  2057.2  692.15    2234  677.66  2469.7  641.03  2695.6   656.7    2892  640.75
  3235.4  629.44  3410.4  617.78  3441.4  609.52  3468.7  603.91  3501.4  609.06
  3604.8  625.45  3653.4  649.32  3682.6  657.28  3779.8  707.84  3808.9  713.11
#Mann= 3 , 0 , 0
       0     .06       0  3441.4    .045       0  3501.4     .08       0
Bank Sta=3441.4,3501.4
XS Rating Curve= 0 ,0
Exp/Cntr=0.3,0.1

Type RM Length L Ch R = 1 ,41620   ,507,476.1,476.8
XS GIS Cut Line= 5
     1727120.543      587416.585      1727001.06      588469.394
     1725919.275      589111.335      1726170.96      589850.154
     1726722.797      590210.218
#Sta/Elev= 30
       0  750.91    88.3  737.84   196.2  713.39   323.8   700.9   480.7  711.51
   716.2  740.78   912.4  727.83   971.3  716.04  1020.3  751.52  1079.2  769.05
  1197.2  786.89  1344.6  787.87  1462.5  774.67  1560.8  772.24  1806.4   730.5
  1894.9  721.53  1953.9  694.56  2042.3  632.19  2052.1  630.13  2258.5  725.52
  2307.6  725.03  2356.5  707.53  2424.8  657.65  2524.9  610.98  2551.6   603.9
  2584.9  604.93  2629.7  615.32  2883.4  616.94  3186.5  635.06  3756.9  716.53
#Mann= 3 , 0 , 0
       0      .1       0  2524.9    .045       0  2584.9     .06       0
Bank Sta=2524.9,2584.9
XS Rating Curve= 0 ,0
Exp/Cntr=0.3,0.1

Type RM Length L Ch R = 1 ,41143.9 ,573.7,536.6,499.1
XS GIS Cut Line= 2
     1725116.583      589248.858     1726714.491       590258.08
#Sta/Elev= 30
       0  793.57    19.6  793.92    88.1  786.07   137.1  782.62   244.8   752.1
   293.8  733.61   323.2  727.69   401.5  716.02   440.7  708.28   460.2  700.13
   479.8  686.19   559.1   619.2     568  612.24   577.8  606.51   587.5  604.12
   597.3   603.9   619.1  603.99   636.5  605.57   665.9  613.47   685.5  615.75
   920.5  616.12  1008.6  618.18  1263.2  628.96  1419.9   642.9  1468.9  644.31
    1508  651.28    1557   664.3    1743  691.49  1831.2  708.22  1889.9  717.56
#Mann= 3 , 0 , 0
       0      .1       0   559.1    .045       0   619.1     .06       0
Bank Sta=559.1,619.1
XS Rating Curve= 0 ,0
Exp/Cntr=0.3,0.1

Type RM Length L Ch R = 1 ,40607.3 ,358,313.5,268.2
XS GIS Cut Line= 3
     1724977.762      590270.764     1726158.169      589925.505
     1726691.533      590262.314
#Sta/Elev= 30
       0  713.91    78.7  716.34   167.3  716.01   324.7  704.92   432.9  693.31
   619.8  708.18   649.4  706.92   678.9  702.12   718.2  697.73   737.9   693.7
   757.6  687.47   767.4  682.81   787.1  670.86     856  620.89   875.7  608.46
   882.5  605.89   885.5  604.75   905.2   603.8   942.5  604.68     974  613.36
   993.7  615.38  1249.3   628.1  1404.6  640.23  1462.8  641.68  1491.9  646.46
  1530.7  658.06  1540.4  660.07    1618  672.06  1734.5  687.88  1860.7  712.96
#Mann= 3 , 0 , 0
       0      .1       0   882.5    .045       0   942.5     .08       0
Bank Sta=882.5,942.5
XS Rating Curve= 0 ,0
Exp/Cntr=0.3,0.1

Type RM Length L Ch R = 1 ,40293.7 ,107,105.6,105.1
XS GIS Cut Line= 5
     1725896.761      590538.724     1725997.528      590500.666
     1726119.933      590156.031     1726117.811      590008.678
     1726326.864      590053.889
#Sta/Elev= 30
       0  692.29    19.6  686.57      49  677.28   107.7  657.59   165.5  645.18
   194.3  636.67     204  634.38   213.6  633.56   242.5  636.48   261.7  637.72
   271.3  636.76   309.8   626.9   329.1  621.08   377.2   607.8   386.8  605.38
   393.3  604.48   396.4  604.05   415.7   603.8   434.9  603.85   444.6  604.55
   453.3  607.25   473.4  618.13   483.3   619.9   581.5  624.46   620.8  624.63
   669.4   627.4   727.8  628.68   756.9  631.01   795.8  635.71   834.7  637.61
#Mann= 3 , 0 , 0
       0     .08       0   393.3    .045       0   453.3     .08       0
Bank Sta=393.3,453.3
XS Rating Curve= 0 ,0
Exp/Cntr=0.3,0.1

Type RM Length L Ch R = 1 ,40188.2 ,318.5,364.6,409.7
XS GIS Cut Line= 5
     1725931.547      590630.827     1726075.024      590576.639
     1726218.631      590172.307     1726219.193      590064.299
      1726358.12       590085.15
#Sta/Elev= 30
       0  689.96    86.3  661.67   153.4  640.34   202.1   631.2   221.6  628.41
   231.4  627.66   280.1  626.08   338.6  621.54   367.9  618.58   397.2  613.91
   447.3   604.6   455.7  603.97   475.2   603.8   494.7  604.52   504.4  606.87
   507.3  608.02   523.9  614.68   533.7  617.81   543.4  620.14   562.9  623.33
   582.4   625.7   602.1  627.25   641.4  628.93   690.5   628.7   727.9  629.63
   737.3  630.31   774.8  634.83   802.8  635.69   812.2  636.59   830.9  639.62
#Mann= 3 , 0 , 0
       0     .08       0   447.3    .045       0   507.3     .08       0
Bank Sta=447.3,507.3
XS Rating Curve= 0 ,0
Exp/Cntr=0.3,0.1

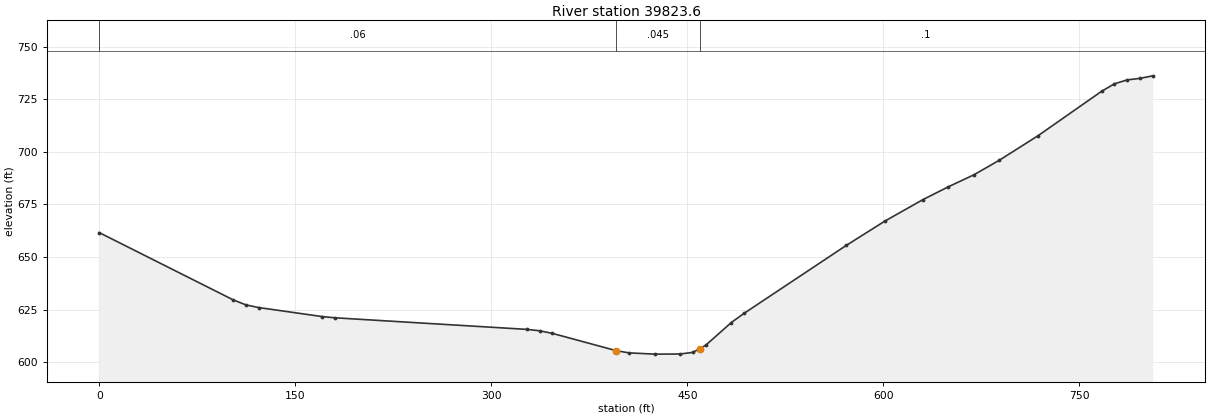
Type RM Length L Ch R = 1 ,39823.6 ,366.9,384.5,401.5
XS GIS Cut Line= 3
     1726024.824      590644.938     1726066.928      590633.372
      1726802.17      590431.404
#Sta/Elev= 30
       0  661.54   102.3  629.63   112.1  627.21   121.9  625.94   170.7  621.63
   180.5  621.06   327.2  615.56   336.9  614.91   346.7  613.66   395.6  605.44
   405.4  604.39   424.9   603.8   444.4  603.86   454.2  604.63   459.4  606.42
     464  608.01   483.6  618.82   493.3  623.16   571.5  655.44   600.9  666.95
   630.2  677.23   649.7  683.34   669.3  689.05   688.8     696   718.2  707.56
     767  728.74   776.8  732.29   786.6  734.15   796.4  734.88   806.1  736.08
#Mann= 3 , 0 , 0
       0     .06       0   395.6    .045       0   459.4      .1       0
Bank Sta=395.6,459.4
XS Rating Curve= 0 ,0
Exp/Cntr=0.3,0.1