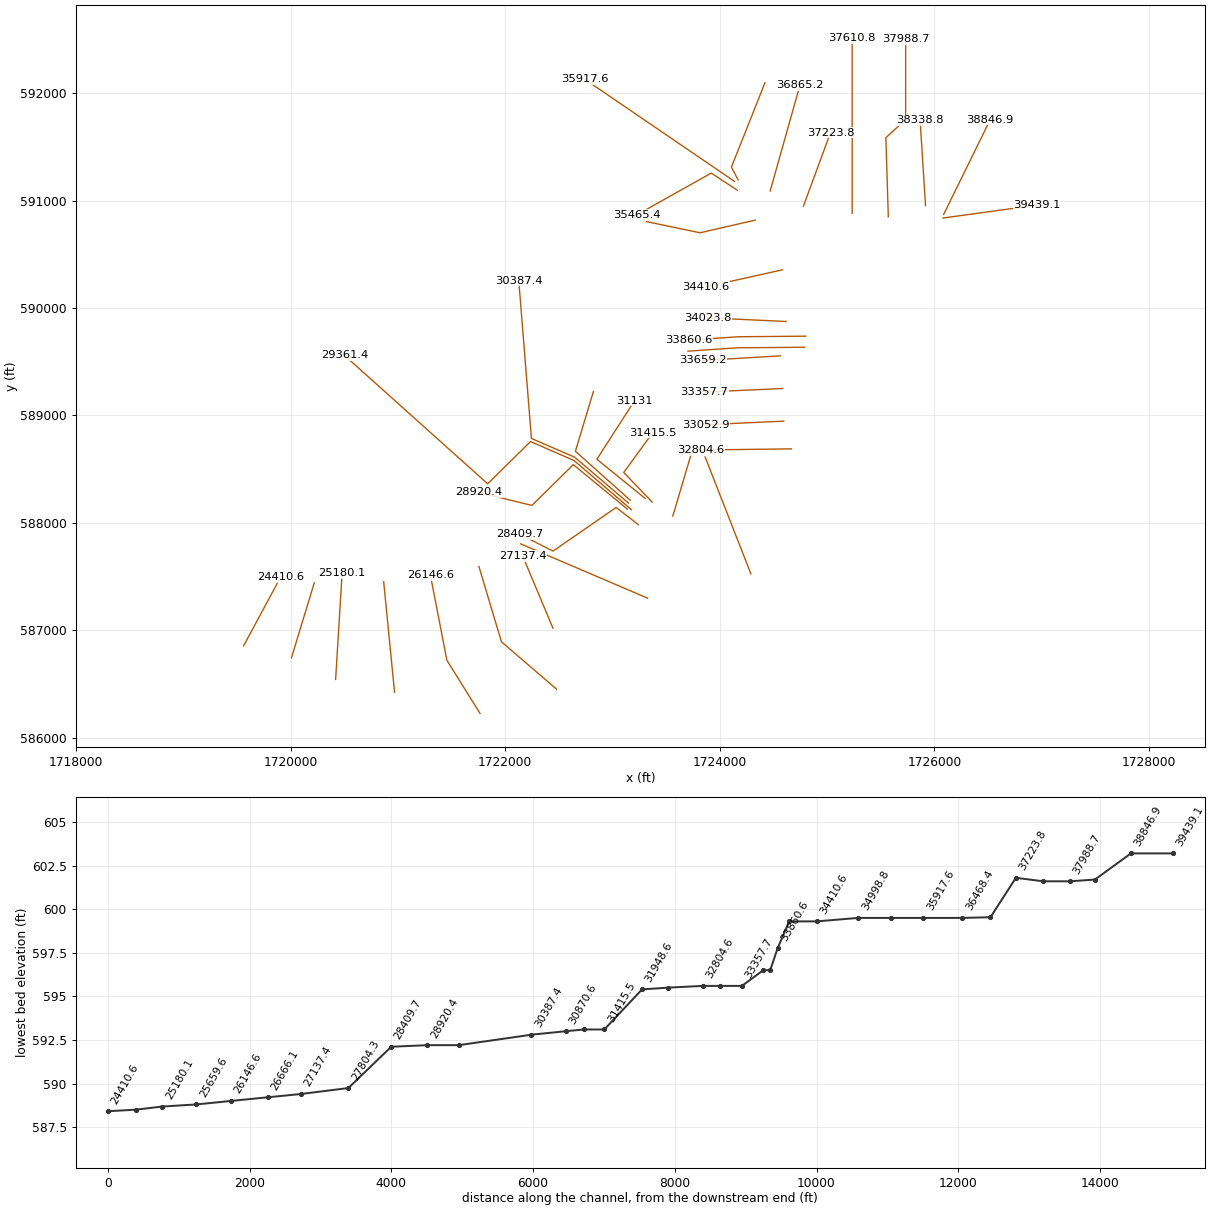
HEC-RAS study EightenmC1.prj: EightenmC1

--- EightenmC1.g01 (geometry) --- (continued)

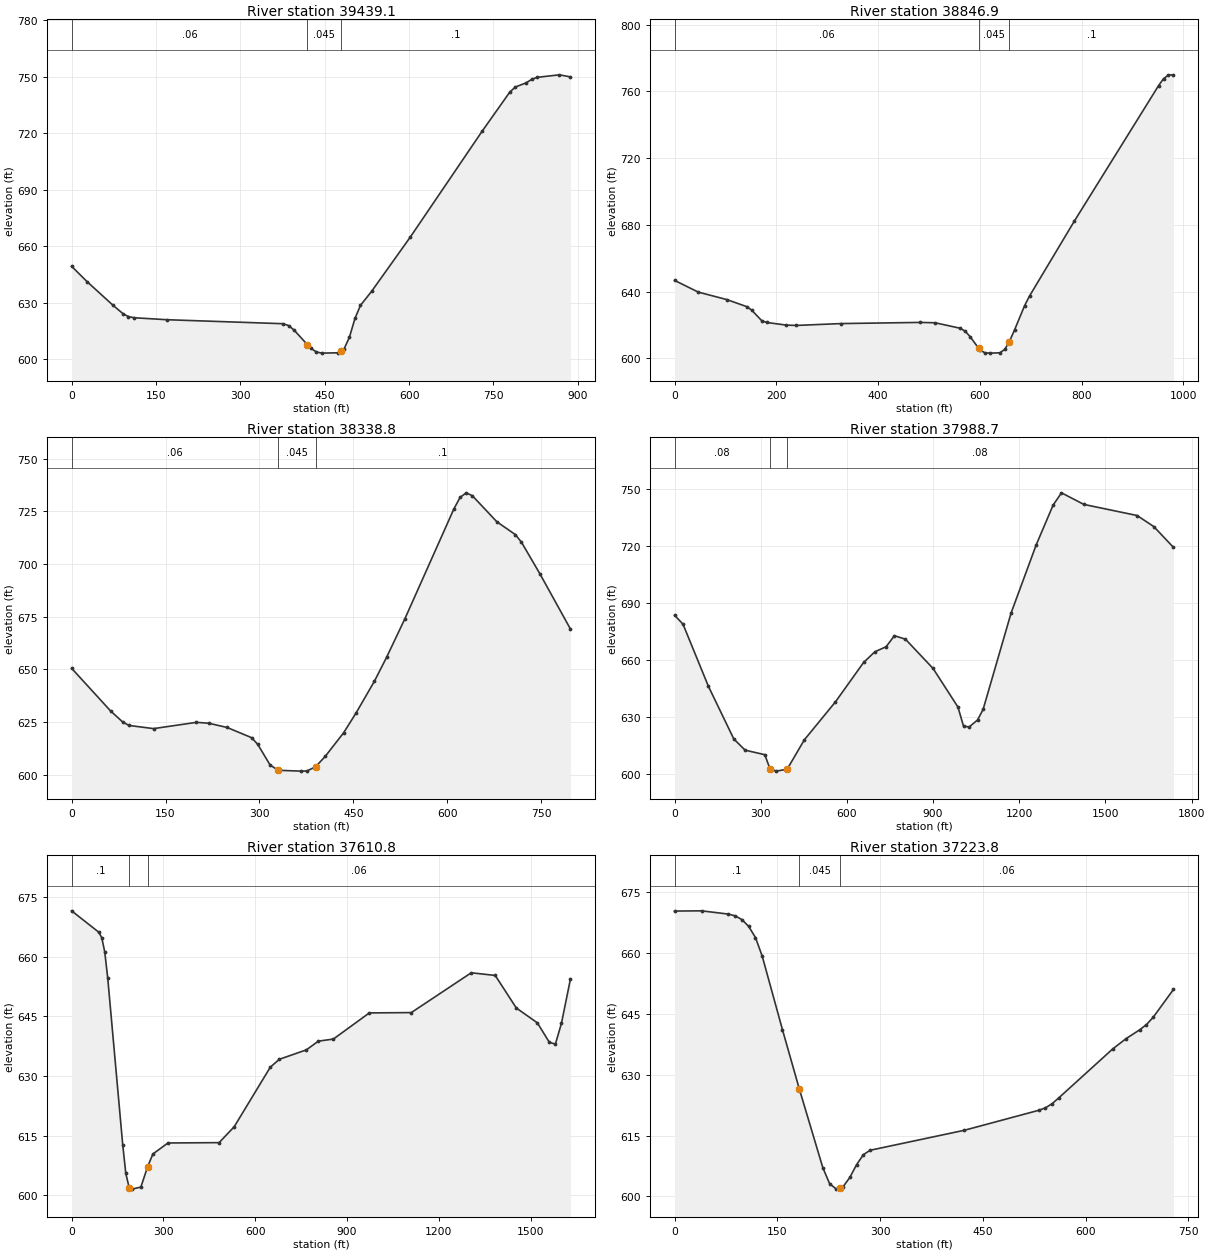
Type RM Length L Ch R = 1 ,39439.1 ,548.2,592.1,636.7
XS GIS Cut Line= 3
     1726078.201       590837.87     1726178.168      590851.561
     1726957.035      590958.223
#Sta/Elev= 30
       0  649.33    27.5  641.16    73.4  628.67    91.7  624.06   100.9  622.62
   110.7     622   169.7  620.94     376  618.82   385.9  617.83   395.7   615.4
   419.3  607.66   425.2  605.84     435  603.84   444.8   603.2   474.3  603.38
   479.3  604.32   484.1  605.22     494  611.67   503.8  621.63   513.6  628.56
   533.3  635.98   602.1   664.8   729.8  721.01   778.9  741.75   788.8  744.51
   808.4  746.78   818.2  748.62   828.1  749.67   867.4     751     887  749.88
#Mann= 3 , 0 , 0
       0     .06       0   419.3    .045       0   479.3      .1       0
Bank Sta=419.3,479.3
XS Rating Curve= 0 ,0
Exp/Cntr=0.3,0.1

Type RM Length L Ch R = 1 ,38846.9 ,484.4,508.1,531.8
XS GIS Cut Line= 3
     1726085.395      590871.772     1726126.443      590955.238
     1726518.149      591751.717
#Sta/Elev= 30
       0  646.78    46.5  639.76   102.8  635.27   141.8  631.06   151.5     629
     171  622.74   180.8  621.58   219.8  619.98   239.3  619.79   327.1   620.9
   483.2   621.6   512.4  621.37   561.2  618.12     571  616.42   580.7  613.16
   597.8  606.07   600.2  605.12     610   603.4   619.7   603.2   639.2  603.39
     649  605.42   657.8  609.87   668.5  617.26     688   631.6   697.7  637.41
   785.5  682.12   951.3   763.4   961.1   767.6   970.8  769.78   980.6  769.91
#Mann= 3 , 0 , 0
       0     .06       0   597.8    .045       0   657.8      .1       0
Bank Sta=597.8,657.8
XS Rating Curve= 0 ,0
Exp/Cntr=0.3,0.1

Type RM Length L Ch R = 1 ,38338.8 ,374.9,350.1,348.8
XS GIS Cut Line= 3
     1725916.513      590952.936     1725912.542       591015.16
     1725865.777      591747.994
#Sta/Elev= 30
       0  650.52    62.4  630.22    81.9  624.94    91.7  623.38   130.9  621.88
   199.4  624.86     219  624.43   248.4  622.42   287.5  617.57   297.3  614.38
   316.9  604.65   329.6  602.11   365.9   601.7   375.7  601.77   389.6  603.75
     405  608.69   434.4  619.91     454  629.17   483.4  644.28     503  655.72
   532.3  674.07   610.6  726.25   620.4  731.64   630.2  733.81     640  732.43
   679.2  720.04   708.6     714   718.4  710.38   747.7  695.45   796.7  669.12
#Mann= 3 , 0 , 0
       0     .06       0   329.6    .045       0   389.6      .1       0
Bank Sta=329.6,389.6
XS Rating Curve= 0 ,0
Exp/Cntr=0.3,0.1

Type RM Length L Ch R = 1 ,37988.7 ,357.2,378,375.2
XS GIS Cut Line= 4
     1725569.667      590849.305      1725546.83      591585.459
     1725731.077       591754.28      1725731.01      592504.496
#Sta/Elev= 30
       0  683.63    29.5  678.87   117.8  646.23   206.2  618.53   245.5  612.64
   314.2  610.24   331.8  602.94   353.5   601.6   391.8  602.57   451.7  618.05
   559.8  637.99     658  658.75   697.2  664.39   736.5  667.05   765.3  672.85
   803.8     671   899.9   655.6   986.4  635.33  1005.9  625.26  1025.4  624.84
  1054.6   628.5  1074.1  634.09  1171.5   684.8  1259.2  720.76  1317.7  741.54
  1346.9  748.01  1424.8  741.91    1610  736.08  1668.4  730.24  1736.6  719.31
#Mann= 3 , 0 , 0
       0     .08       0   331.8    .045       0   391.8     .08       0
Bank Sta=331.8,391.8
XS Rating Curve= 0 ,0
Exp/Cntr=0.3,0.1

Type RM Length L Ch R = 1 ,37610.8 ,402.9,386.9,371
XS GIS Cut Line= 4
     1725232.866      590880.919     1725232.726      591608.919
     1725232.598      592275.012     1725232.552      592511.122
#Sta/Elev= 30
       0   671.5    88.5  666.15    98.4  664.78   108.2  661.22     118  654.64
   167.2   612.6   177.1  605.54     188     602   196.8   601.6   226.3  602.11
     248  607.14   265.6  610.43   314.8  613.19     482  613.28   531.2  617.26
   649.3  632.23   678.8  634.21   767.2  636.58   806.4  638.77   855.3  639.29
   972.9  645.86    1110  645.94  1305.9  655.94  1384.3  655.27  1453.1   647.1
    1522  643.36  1561.3  638.45    1581  638.05  1600.7  643.26  1630.2  654.44
#Mann= 3 , 0 , 0
       0      .1       0     188    .045       0     248     .06       0
Bank Sta=188,248
XS Rating Curve= 0 ,0
Exp/Cntr=0.3,0.1

Type RM Length L Ch R = 1 ,37223.8 ,355.1,358.7,362.2
XS GIS Cut Line= 2
     1724778.839      590949.207      1725030.61      591632.354
#Sta/Elev= 30
       0  670.37    39.4  670.43    78.7  669.62    88.6  669.18    98.4  668.26
   108.2  666.58   118.1  663.84   127.9  659.27   157.4  641.16   181.9   626.6
   216.4  607.08   226.3  603.14   236.1   601.8   241.9  602.16     246  602.41
   255.8  604.68   265.6  607.82   275.5  610.28   285.3  611.38   423.1  616.32
   531.3  621.23   541.1  621.82     551  622.87   560.8  624.31   639.5  636.38
   659.2  638.94   678.9  641.09   688.7  642.38   698.6  644.19   728.1  651.04
#Mann= 3 , 0 , 0
       0      .1       0   181.9    .045       0   241.9     .06       0
Bank Sta=181.9,241.9
XS Rating Curve= 0 ,0
Exp/Cntr=0.3,0.1

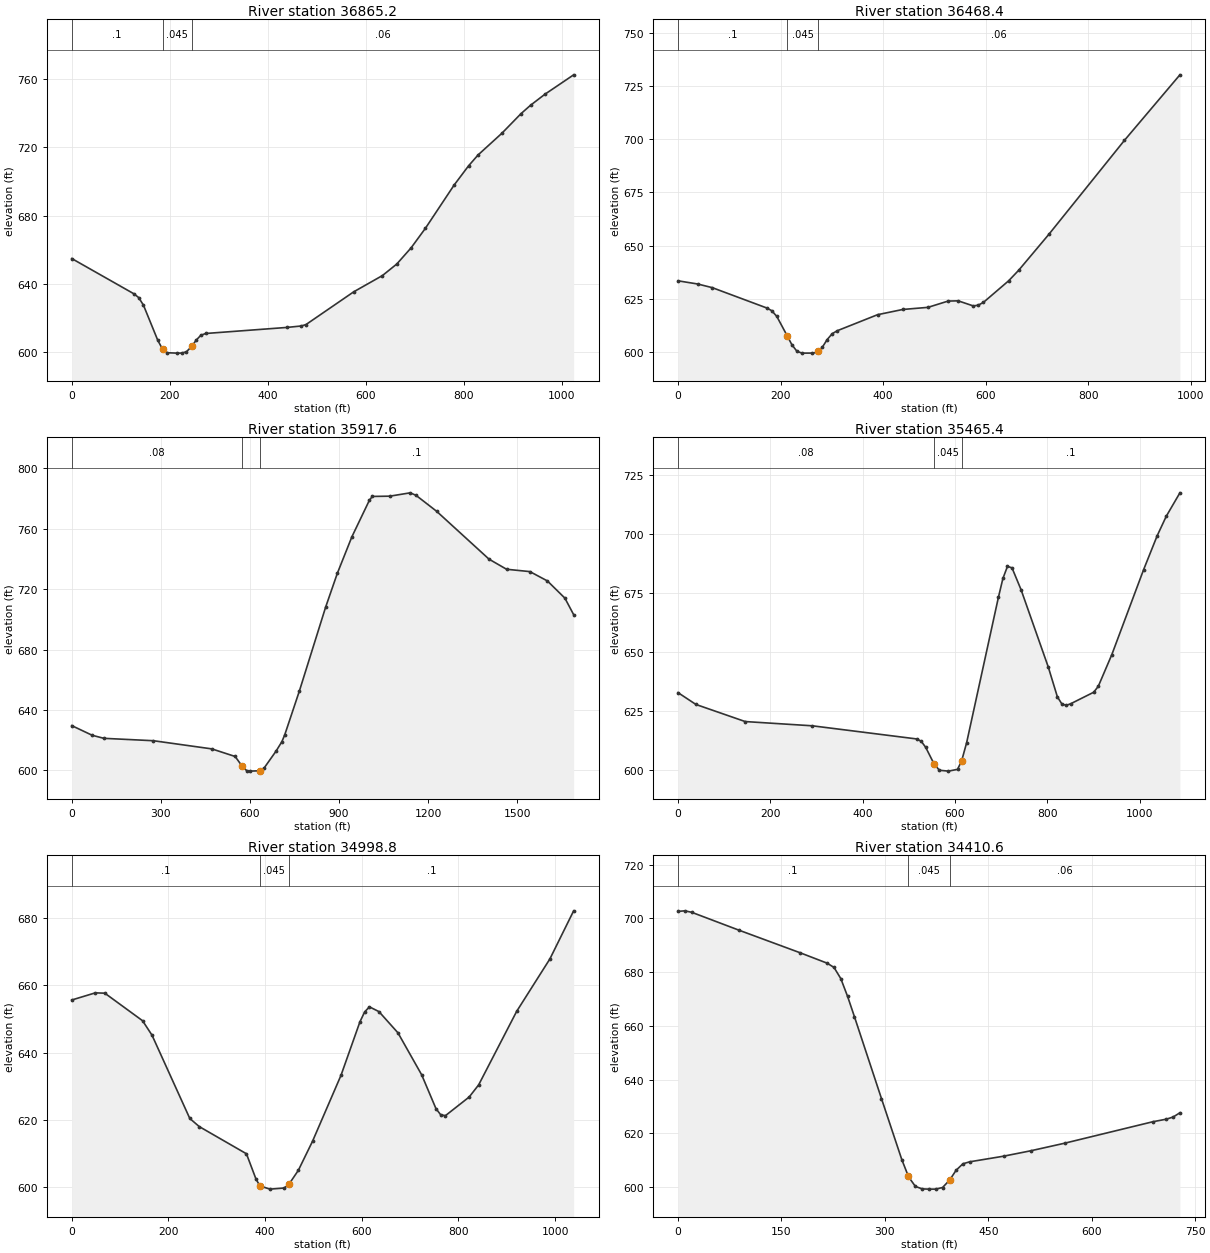
Type RM Length L Ch R = 1 ,36865.2 ,401.4,396.7,392
XS GIS Cut Line= 2
     1724468.664      591089.605     1724746.434      592076.024
#Sta/Elev= 30
       0  654.84   126.9  634.23   136.6  632.03   146.4  627.58   175.7     607
   185.7  601.67   195.2  599.76   214.7  599.54   224.5  599.56   234.2  600.34
   245.7  603.72   253.8  607.06   263.5  609.95   273.3  611.02   439.2  614.56
   468.5  615.41   478.2  616.23   575.8   635.4   634.4   644.9   663.7  651.65
     693  661.14   722.2  672.57   780.8  697.84   810.1     709   829.6   715.4
   878.4  728.13   917.4  739.58   936.9   744.5   966.2  750.92  1024.8  762.26
#Mann= 3 , 0 , 0
       0      .1       0   185.7    .045       0   245.7     .06       0
Bank Sta=185.7,245.7
XS Rating Curve= 0 ,0
Exp/Cntr=0.3,0.1

Type RM Length L Ch R = 1 ,36468.4 ,488.6,550.8,612.4
XS GIS Cut Line= 3
     1724169.959      591193.775      1724107.43      591311.859
     1724419.949      592096.834
#Sta/Elev= 30
       0  633.45    38.2  631.96    66.8  630.24   172.9  620.71   182.7  619.43
   192.6  616.73   213.3  607.42     222  603.44   231.9  600.35   241.7   599.5
   261.3  599.52   271.2  599.82   273.3  600.32     281  602.15   290.8  605.87
   300.6  608.63   310.5  610.02     389  617.54   438.2     620   487.3  620.99
   526.6  623.94   546.2  624.05   575.7  621.66   585.5  622.03   595.4  623.32
   644.5  633.44   664.1  638.39   723.1   655.3   870.4  699.41   978.5  730.16
#Mann= 3 , 0 , 0
       0      .1       0   213.3    .045       0   273.3     .06       0
Bank Sta=213.3,273.3
XS Rating Curve= 0 ,0
Exp/Cntr=0.3,0.1

Type RM Length L Ch R = 1 ,35917.6 ,402.5,452.2,502.5
XS GIS Cut Line= 2
     1724135.228      591179.879     1722738.909      592131.414
#Sta/Elev= 30
       0  629.65    68.8  623.25   108.1  621.23   275.1  619.64   471.6  614.23
   550.1   609.2   573.3  602.86   589.4  599.71   599.3   599.5   633.3  599.74
   648.4  601.78   687.7  612.73   707.3  618.96   717.1  623.58   766.3  652.57
   854.7  708.12     894  730.49   943.1  754.74    1002  778.93  1011.9  781.47
  1070.8  781.65  1139.6  783.86  1159.2  782.17    1228   771.7  1404.8  739.92
  1463.8  733.23  1542.4  731.67  1601.3   725.5  1660.2   714.1  1689.7  703.15
#Mann= 3 , 0 , 0
       0     .08       0   573.3    .045       0   633.3      .1       0
Bank Sta=573.3,633.3
XS Rating Curve= 0 ,0
Exp/Cntr=0.3,0.1

Type RM Length L Ch R = 1 ,35465.4 ,480.2,466.7,453.1
XS GIS Cut Line= 3
     1724163.021      591096.524     1723919.881       591256.27
     1723225.273      590867.208
#Sta/Elev= 30
       0  632.75    38.8  627.74   145.5   620.5   290.9   618.7     517  613.13
   526.8  612.15   536.6  609.53   554.3  602.65   566.1  599.87   585.8   599.5
   605.4  600.25   614.3  603.83   625.1  611.51   693.9  673.07   703.7  681.11
   713.6  686.24   723.4  685.61     743  676.36     802  643.59   821.7  630.96
   831.5  627.92   841.3  627.37   851.2  628.11   900.3  632.91   910.2  635.39
   939.6  648.84  1008.4  684.81  1037.9  699.23  1057.6  707.49  1087.1  717.39
#Mann= 3 , 0 , 0
       0     .08       0   554.3    .045       0   614.3      .1       0
Bank Sta=554.3,614.3
XS Rating Curve= 0 ,0
Exp/Cntr=0.3,0.1

Type RM Length L Ch R = 1 ,34998.8 ,588.6,588.2,587.8
XS GIS Cut Line= 3
      1724329.76      590818.682     1723815.735      590700.546
     1723315.582      590804.698
#Sta/Elev= 30
       0  655.58    48.8   657.7    68.4   657.6   146.5  649.43     166  645.15
   244.2  620.45   263.7  618.05   361.4  609.98   380.9  602.57   389.2  600.43
   410.2   599.5   439.5  599.83   449.2  600.92   468.8  605.09   498.1   613.7
   556.9  633.21   596.2  649.12     606  652.06   615.8  653.55   635.5  652.14
   674.8  645.85   723.9  633.39   753.4  623.39   763.2  621.55     773  621.28
   822.2  626.82   841.8  630.42   920.4  652.21   989.2  667.77  1038.3  682.02
#Mann= 3 , 0 , 0
       0      .1       0   389.2    .045       0   449.2      .1       0
Bank Sta=389.2,449.2
XS Rating Curve= 0 ,0
Exp/Cntr=0.3,0.1

Type RM Length L Ch R = 1 ,34410.6 ,398.8,386.8,374.8
XS GIS Cut Line= 2
     1724582.287      590355.515     1723871.622       590197.59
#Sta/Elev= 30
       0  702.61     9.8  702.82    19.7  702.29    88.5  695.61   177.1  687.22
   216.4  683.34   226.3  681.75   236.1  677.62     246  670.96   255.8  663.51
   295.1  632.99   324.6  610.28     334  604.15   334.5  603.82   344.3  600.31
   354.2  599.38     364   599.3   373.8   599.3   383.7   599.9     394  602.68
   403.4  606.33   413.2  608.72     423  609.46   472.2  611.55   511.6  613.56
   560.8  616.38   688.6  624.36   708.3  625.32   718.2  626.13     728   627.7
#Mann= 3 , 0 , 0
       0      .1       0     334    .045       0     394     .06       0
Bank Sta=334,394
XS Rating Curve= 0 ,0
Exp/Cntr=0.3,0.1

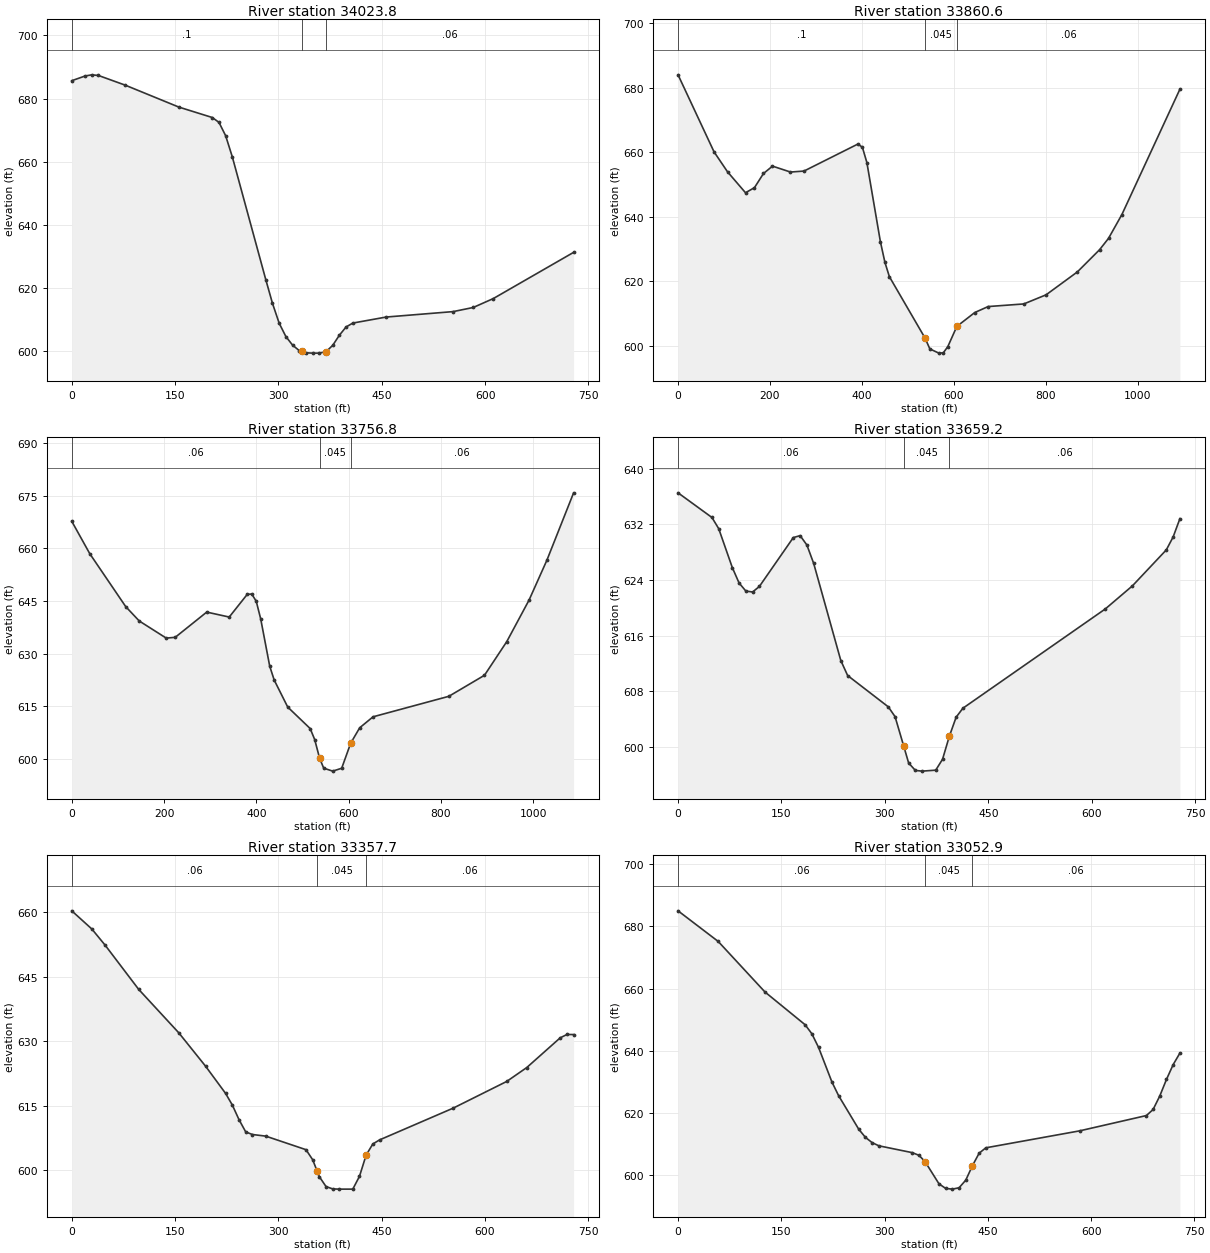
Type RM Length L Ch R = 1 ,34023.8 ,160.6,163.2,165.8
XS GIS Cut Line= 2
     1724617.202      589874.507     1723889.534      589908.839
#Sta/Elev= 30
       0  685.65    19.4  687.14    29.1  687.51    38.8   687.3    77.7  684.23
   155.4  677.29     204  673.98   213.7  672.44   223.4   668.2   233.1  661.48
   281.7  622.56   291.4  615.06   301.1  608.78   310.8  604.56   320.5  601.85
   330.2   600.1     334  599.83     340   599.4   349.7   599.3   359.4   599.3
   369.1  599.76   378.8  601.76   388.5  604.98   398.2  607.59     408  608.83
   456.5  610.74   553.6  612.46   582.8  613.77   611.9  616.59   728.5  631.24
#Mann= 3 , 0 , 0
       0      .1       0     334    .045       0   369.1     .06       0
Bank Sta=334,369.1
XS Rating Curve= 0 ,0
Exp/Cntr=0.3,0.1

Type RM Length L Ch R = 1 ,33860.6 ,103.8,103.8,103.8
XS GIS Cut Line= 3
     1724799.947      589737.752     1724173.801      589732.478
     1723709.164      589701.113
#Sta/Elev= 30
       0  683.98    78.3  660.12   107.6  653.94   146.8  647.44   166.3  649.03
   185.9  653.41   205.5  655.69   244.6  653.86     274  654.16   391.4  662.54
   401.1  661.53   410.9  656.77   440.3  632.24   450.1  625.88   459.8  621.44
   537.3  602.44   547.9  599.05   567.5  597.75   577.2  597.85     587  599.78
   606.6  606.03   645.6  610.33   674.7  612.18   752.3  612.99   800.8  615.82
   868.7   622.9   917.2   629.8   936.6  633.31   965.7  640.69  1091.9  679.52
#Mann= 3 , 0 , 0
       0      .1       0   537.3    .045       0   606.6     .06       0
Bank Sta=537.3,606.6
XS Rating Curve= 0 ,0
Exp/Cntr=0.3,0.1

Type RM Length L Ch R = 1 ,33756.8 ,95.2,97.5,99.9
XS GIS Cut Line= 3
     1724789.508      589634.733     1724165.298      589629.476
     1723702.592      589598.241
#Sta/Elev= 30
       0   667.7      39  658.48     117  643.38   146.3  639.29   204.8  634.41
   224.3  634.63   292.6  641.82   341.4  640.41   380.4  646.87   390.2  646.97
   399.9  644.93   409.6   639.9   429.2  626.39   438.9  622.45   468.2  614.76
   516.9  608.63   526.7  605.49   537.3  600.18   546.2  597.35   565.7   596.5
   585.2  597.32   604.7  604.45   624.2  608.85   653.2  611.98   817.5  617.82
   894.8  623.82   943.1  633.41   991.4  645.24    1030  656.58    1088  675.81
#Mann= 3 , 0 , 0
       0     .06       0   537.3    .045       0   604.7     .06       0
Bank Sta=537.3,604.7
XS Rating Curve= 0 ,0
Exp/Cntr=0.3,0.1

Type RM Length L Ch R = 1 ,33659.2 ,302.2,301.5,300.7
XS GIS Cut Line= 2
     1724565.186      589554.519     1723838.461      589511.453
#Sta/Elev= 30
       0  636.55    49.2     633      59  631.39    78.7   625.8    88.5  623.58
    98.4  622.41   108.2  622.28     118  623.08   167.2  630.11   177.1  630.39
   186.9  629.04   196.8  626.38   236.1  612.42     246  610.26     305  605.75
   314.8  604.34   327.2  600.16   334.5  597.67   344.3   596.6   354.2   596.5
   373.8  596.64   383.7  598.21   393.5   601.5   403.4  604.26   413.2  605.55
   619.8  619.84   659.1  623.16   708.3  628.34   718.2   630.2     728  632.83
#Mann= 3 , 0 , 0
       0     .06       0   327.2    .045       0   393.5     .06       0
Bank Sta=327.2,393.5
XS Rating Curve= 0 ,0
Exp/Cntr=0.3,0.1

Type RM Length L Ch R = 1 ,33357.7 ,304.9,304.9,304.8
XS GIS Cut Line= 2
     1724582.783      589250.394     1723854.646      589217.364
#Sta/Elev= 30
       0   660.3    29.2  656.07    48.6  652.29    97.2  642.04   155.5  631.93
   194.4  624.17   223.5  617.84   233.2  615.15     243  611.73   252.7  608.89
   262.4   608.3   281.8  607.92   340.2  604.77   349.9  602.44   356.2  599.87
   359.6  598.49   369.3   596.2     379  595.65   388.7   595.6   408.2   595.6
   417.9  598.58   427.6  603.53   437.3   606.1     447  607.04     554  614.43
   631.7  620.63   660.9  623.87   709.4  630.77   719.2  631.55   728.9  631.54
#Mann= 3 , 0 , 0
       0     .06       0   356.2    .045       0   427.6     .06       0
Bank Sta=356.2,427.6
XS Rating Curve= 0 ,0
Exp/Cntr=0.3,0.1

Type RM Length L Ch R = 1 ,33052.9 ,249.8,248.3,246.9
XS GIS Cut Line= 2
     1724595.834      588946.489     1723867.697      588913.459
#Sta/Elev= 30
       0     685    58.3  675.17   126.3  658.92   184.6   648.4   194.4  645.49
   204.1  641.12   223.5  630.01   233.2  625.62   262.4  614.86   272.1  612.24
   281.8  610.55   291.6  609.52   340.2  607.32   349.9  606.47   358.7  604.46
     379   597.3   388.7  595.83   398.5   595.6   408.2  596.04   417.9  598.49
   427.6  603.14   437.3  607.14     447  608.87   583.1  614.31   680.3  619.24
     690  621.19   699.7  625.53   709.4  630.84   719.2  635.63   728.9  639.29
#Mann= 3 , 0 , 0
       0     .06       0   358.7    .045       0   427.6     .06       0
Bank Sta=358.7,427.6
XS Rating Curve= 0 ,0
Exp/Cntr=0.3,0.1

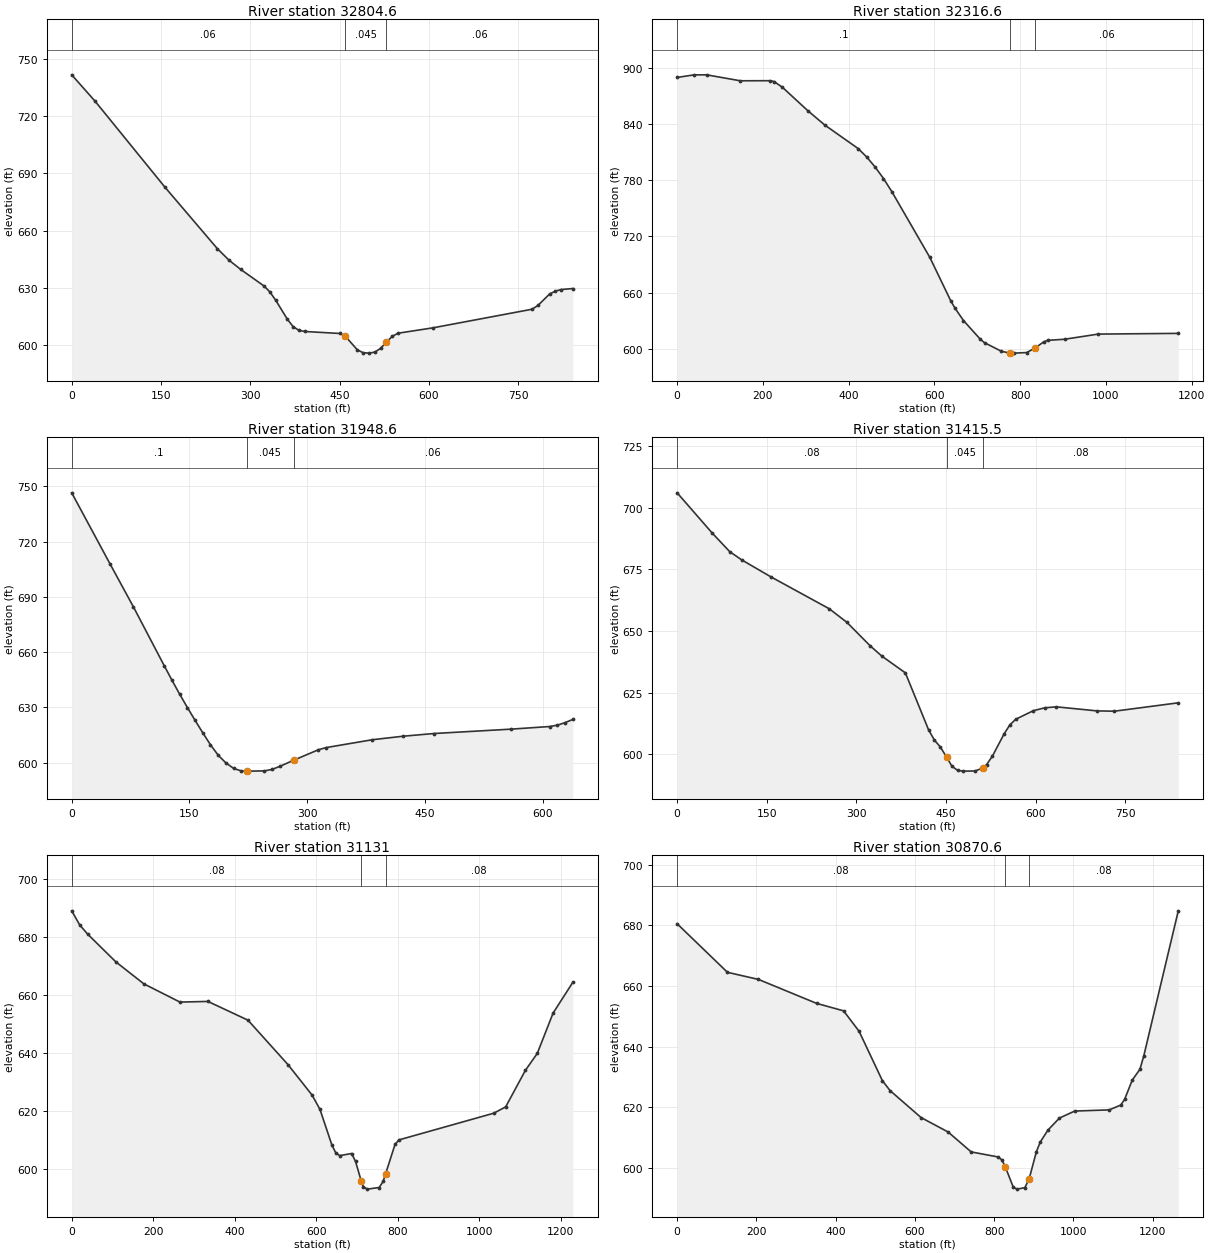
Type RM Length L Ch R = 1 ,32804.6 ,544.5,488,430.9
XS GIS Cut Line= 2
     1724666.562      588688.492     1723824.616      588678.135
#Sta/Elev= 30
       0  741.82    39.2  727.98   156.6   682.8   244.8  650.45   264.4   644.4
   283.9  639.58   323.1  630.88   332.9  627.76   342.7   623.4   362.3  613.42
     372  609.52   381.8  607.58   391.6  606.97   450.4  605.93   458.9  604.74
   479.8  597.36   489.5  595.82   499.3   595.6   509.1  596.11   518.9   598.1
   528.7  601.39   538.5  604.41   548.3  606.06     607  608.89   773.5  618.67
   783.3  620.64   802.8  626.63   812.6  628.18   822.4  629.01     842  629.55
#Mann= 3 , 0 , 0
       0     .06       0   458.9    .045       0   528.7     .06       0
Bank Sta=458.9,528.7
XS Rating Curve= 0 ,0
Exp/Cntr=0.3,0.1

Type RM Length L Ch R = 1 ,32316.6 ,398.2,368,337.8
XS GIS Cut Line= 2
     1724288.952      587524.933     1723862.671      588613.083
#Sta/Elev= 30
       0  889.79    39.3  892.52    68.8  892.58   147.3  886.21   216.1  886.32
   225.9  885.44   245.5  879.28   304.4  854.44   343.7  839.19   422.3  813.81
   441.9  804.97   461.6  794.22   481.2  781.91   500.9  767.71   589.2  697.77
   638.4  651.06   648.2  643.36   667.8  630.28   707.1  610.27   716.9  606.61
   756.2  597.48   775.7  595.56   785.7   595.5   815.1  596.11   835.7  601.19
   854.4   607.4   864.2  609.15   903.5  610.31   982.1  615.83  1168.7  616.58
#Mann= 3 , 0 , 0
       0      .1       0   775.7    .045       0   835.7     .06       0
Bank Sta=775.7,835.7
XS Rating Curve= 0 ,0
Exp/Cntr=0.3,0.1

Type RM Length L Ch R = 1 ,31948.6 ,548.5,533.1,517.7
XS GIS Cut Line= 2
     1723561.413      588062.786     1723743.039      588674.974
#Sta/Elev= 30
       0   746.5    49.1  707.69    78.6   684.6   117.9  652.62   127.7  644.79
   137.5  637.21   147.4  629.94   157.2  622.96     167  616.21   176.8  609.72
   186.7     604   196.5  599.87   206.3  596.87   216.1   595.5   222.8  595.43
     226   595.4   245.6  595.53   255.4  596.34   265.2  597.99   282.8  601.31
   314.4  607.02   324.2  608.18   383.1  612.45   422.4  614.36   461.7  615.82
     560   618.2   609.1  619.62   618.9  620.35   628.7  621.73   638.6  623.48
#Mann= 3 , 0 , 0
       0      .1       0   222.8    .045       0   282.8     .06       0
Bank Sta=222.8,282.8
XS Rating Curve= 0 ,0
Exp/Cntr=0.3,0.1

Type RM Length L Ch R = 1 ,31415.5 ,281.9,284.5,287.2
XS GIS Cut Line= 3
     1723368.492      588193.445     1723104.147      588468.914
     1723373.171      588837.786
#Sta/Elev= 30
       0  706.12    58.7  689.77    88.1   682.2   107.7  678.94   156.6  672.03
   254.5  659.03   283.9  653.54     323  643.96   342.6  639.78   381.8     633
   420.6  609.87   430.4  605.68   440.1  602.96     451  598.69   459.5  595.15
   469.2  593.39   478.9   593.1   498.4  593.16     511  594.35   517.8  595.78
   527.5  599.25   546.9  608.21   556.6  611.89   566.4  614.16   595.5  617.61
   614.9  618.82   634.4  619.21   702.4  617.56   731.5  617.44   838.3  620.84
#Mann= 3 , 0 , 0
       0     .08       0     451    .045       0     511     .08       0
Bank Sta=451,511
XS Rating Curve= 0 ,0
Exp/Cntr=0.3,0.1

Type RM Length L Ch R = 1 ,31131   ,247.7,260.3,272.9
XS GIS Cut Line= 3
      1723304.56      588226.262     1722853.746      588591.608
     1723205.493      589137.971
#Sta/Elev= 30
       0  688.93    19.7  684.05    39.3  680.88   108.2  671.37     177  663.79
   265.6  657.51   334.4  657.73   432.7  651.27   531.1  635.93     590  625.48
   609.4  620.54   638.5  608.34   648.2  605.56   657.9  604.64     687  605.36
   696.6  602.66   710.6  595.93     716  593.88   725.8   593.1   754.8  593.66
   764.5  595.79   770.6  598.43   793.6   608.5   803.3  610.06  1036.1  619.25
  1065.2  621.43  1113.7  634.02  1142.8  639.84  1181.6  653.72  1230.1  664.33
#Mann= 3 , 0 , 0
       0     .08       0   710.6    .045       0   770.6     .08       0
Bank Sta=710.6,770.6
XS Rating Curve= 0 ,0
Exp/Cntr=0.3,0.1

Type RM Length L Ch R = 1 ,30870.6 ,466.4,483.2,500
XS GIS Cut Line= 3
      1723164.44      588210.793     1722653.867      588666.084
      1722821.37      589222.336
#Sta/Elev= 30
       0  680.56     127  664.54   205.2   662.2   351.8   654.3   420.2  651.82
   459.3  645.08     518  628.81   537.5  625.51   615.7  616.62   684.1  611.84
   742.2  605.28     810  603.62   819.6  602.68   828.5  600.32   848.7  593.56
   858.4     593   877.7  593.49   888.5  596.36   906.8  605.33   916.5  608.52
   935.8  612.45   964.9  616.44  1003.6  618.76  1090.7  619.15  1119.8  620.74
  1129.5  622.61  1148.8  628.97  1168.2  632.55  1177.9  636.94    1265  684.83
#Mann= 3 , 0 , 0
       0     .08       0   828.5    .045       0   888.5     .08       0
Bank Sta=828.5,888.5
XS Rating Curve= 0 ,0
Exp/Cntr=0.3,0.1

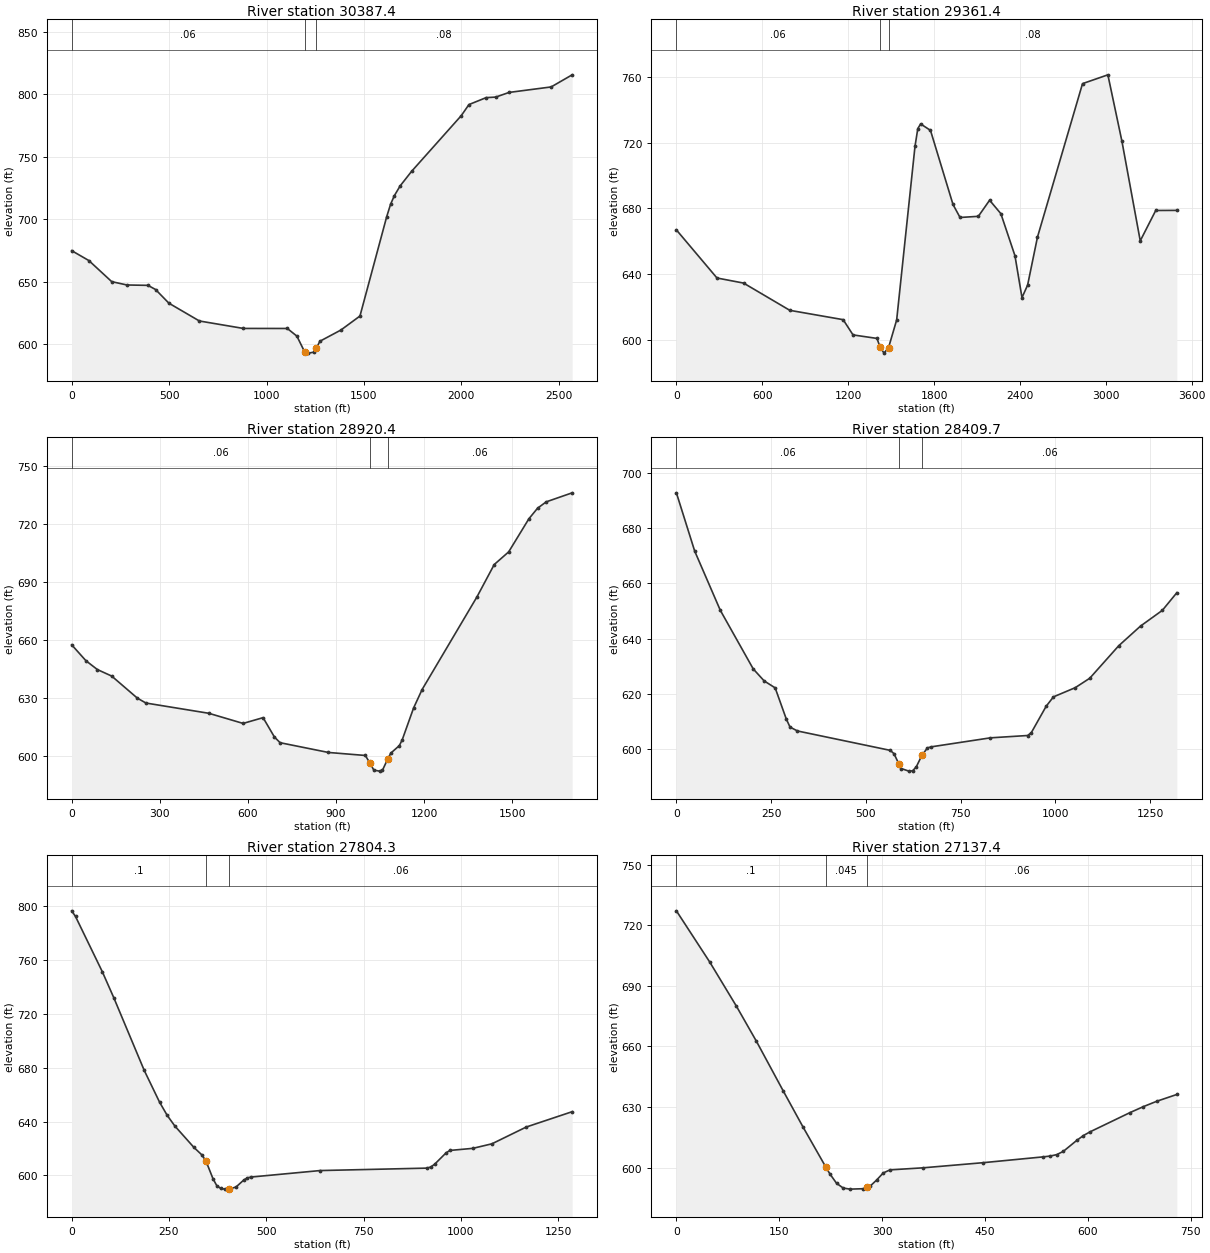
Type RM Length L Ch R = 1 ,30387.4 ,923,1026,1126.7
XS GIS Cut Line= 4
     1723147.424      588184.099     1722648.755      588609.597
      1722244.06      588785.715     1722126.195      590252.712
#Sta/Elev= 30
       0  674.84    88.1  666.92   205.5  650.02   283.7  647.36   391.4  647.06
   430.5  643.73     499  632.77   655.5  618.53   881.1  612.57  1106.7  612.54
  1155.8  606.42  1195.8  593.72  1214.6   592.8  1244.1  593.58  1255.8  596.65
  1273.5  602.29  1381.4  611.26  1479.5   622.5  1616.9   702.1  1636.5  711.92
  1656.1  718.88  1685.6  726.65  1744.4  738.32  1999.5  782.95  2038.8   791.8
  2127.1  797.36  2176.2  797.79  2244.8  801.53  2460.7  805.92  2568.6  815.62
#Mann= 3 , 0 , 0
       0     .06       0  1195.8    .045       0  1255.8     .08       0
Bank Sta=1195.8,1255.8
XS Rating Curve= 0 ,0
Exp/Cntr=0.3,0.1

Type RM Length L Ch R = 1 ,29361.4 ,441.2,441.1,443.2
XS GIS Cut Line= 5
     1723175.591      588122.659     1722640.468      588580.379
     1722235.774      588756.497     1721835.891      588363.189
     1720502.725      589558.062
#Sta/Elev= 30
       0     667   283.6   637.8   469.4  634.72   792.4  618.18  1165.2  612.51
  1234.1  603.26  1401.4  601.13  1422.6     596  1450.6   592.2  1482.6  595.61
  1539.1  612.37  1667.1  717.69  1686.7  728.49  1706.4  731.33  1775.3  727.41
  1932.7  682.42  1981.8  674.54  2109.7  675.24  2188.4  685.01  2267.1  676.84
  2365.5  651.33  2414.7  625.89    2454  633.52  2522.9  662.65  2837.6  755.78
  3014.7  761.13  3113.1  720.72  3240.9  660.36  3349.1  678.79  3496.7  678.85
#Mann= 3 , 0 , 0
       0     .06       0  1422.6    .045       0  1482.6     .08       0
Bank Sta=1422.6,1482.6
XS Rating Curve= 0 ,0
Exp/Cntr=0.3,0.1

Type RM Length L Ch R = 1 ,28920.4 ,518.6,510.7,502.8
XS GIS Cut Line= 4
     1723137.854       588127.26     1722634.644      588541.698
     1722248.523      588161.926      1721752.03      588283.432
#Sta/Elev= 30
       0  657.54    48.6   649.3    87.6  644.73   136.2  641.38   223.8  629.94
     253  627.42     467  622.12   583.8  616.88   651.9  619.86   690.6  609.83
   709.9   606.9   874.3  601.86  1000.1   600.3  1015.8  596.38  1029.1  592.72
  1048.4   592.2  1058.1  592.53  1075.8  598.27  1087.1  601.53  1116.1  605.42
  1125.8   608.4  1164.5  624.86  1193.5   634.4  1380.3  682.32  1439.2  699.07
  1488.4  705.62  1557.2  722.73  1586.7  728.19  1616.2  731.49  1704.6  736.16
#Mann= 3 , 0 , 0
       0     .06       0  1015.8    .045       0  1075.8     .06       0
Bank Sta=1015.8,1075.8
XS Rating Curve= 0 ,0
Exp/Cntr=0.3,0.1

Type RM Length L Ch R = 1 ,28409.7 ,649.2,605.4,561.6
XS GIS Cut Line= 4
     1723239.601      587983.032     1723033.657      588142.881
     1722444.983      587736.463     1722137.591      587892.731
#Sta/Elev= 30
       0  692.66    48.3  671.61   115.9  650.22   202.8  629.04   231.7   624.7
   260.7  622.19   290.1  610.92   299.9  608.03   319.5  606.62   564.5  599.61
   574.3  598.42   587.8  594.53   593.9  593.03   613.5  592.11   623.3  592.21
   633.1  593.64   647.8  597.76   662.5  600.49   672.3  600.88     829  604.14
     927  604.98   936.8  606.02     976  615.56   995.2  618.94  1052.7  622.26
    1091  625.67  1167.6  637.43  1225.1  644.53  1282.6   650.2  1320.9  656.58
#Mann= 3 , 0 , 0
       0     .06       0   587.8    .045       0   647.8     .06       0
Bank Sta=587.8,647.8
XS Rating Curve= 0 ,0
Exp/Cntr=0.3,0.1

Type RM Length L Ch R = 1 ,27804.3 ,704.4,666.9,629.3
XS GIS Cut Line= 2
      1723325.48      587298.916     1722142.808      587804.164
#Sta/Elev= 30
       0  796.65     9.8  792.46    78.5  751.49     108  732.18   186.5  677.96
   225.8  654.42   245.4  644.59   265.1  636.66   314.2  620.72   333.8  615.39
   344.7  610.89   363.2  597.42   373.1  592.18   382.9  590.32   392.7  589.74
   404.7  589.82   422.2  591.29   441.8   596.4   451.6  598.12   461.4  598.73
   638.1  603.54     913  605.36   922.8  606.21   932.6  608.23   962.1  616.71
   971.9   618.5  1030.8  620.06  1079.9  623.43  1168.3  635.93  1286.1  647.31
#Mann= 3 , 0 , 0
       0      .1       0   344.7    .045       0   404.7     .06       0
Bank Sta=344.7,404.7
XS Rating Curve= 0 ,0
Exp/Cntr=0.3,0.1

Type RM Length L Ch R = 1 ,27137.4 ,476.1,471.3,466.5
XS GIS Cut Line= 2
     1722444.668      587018.267      1722162.32      587691.438
#Sta/Elev= 30
       0   727.1    48.7  701.73    87.6  679.89   116.8  662.52   155.7  638.08
   184.9  620.02   217.9  600.35   223.9  596.93   233.6   592.3   243.3  589.94
   253.1   589.4   272.5   589.6   277.9  590.26   282.3  590.79     292  593.87
   301.7   597.4   311.5  598.92   360.1  599.95   447.7  602.49   535.3  605.37
   545.1  605.76   554.8  606.47   564.5  608.11     584  613.52   593.7  615.91
   603.4  617.75   661.8  627.29   681.3  630.24   700.8  632.89     730  636.24
#Mann= 3 , 0 , 0
       0      .1       0   217.9    .045       0   277.9     .06       0
Bank Sta=217.9,277.9
XS Rating Curve= 0 ,0
Exp/Cntr=0.3,0.1

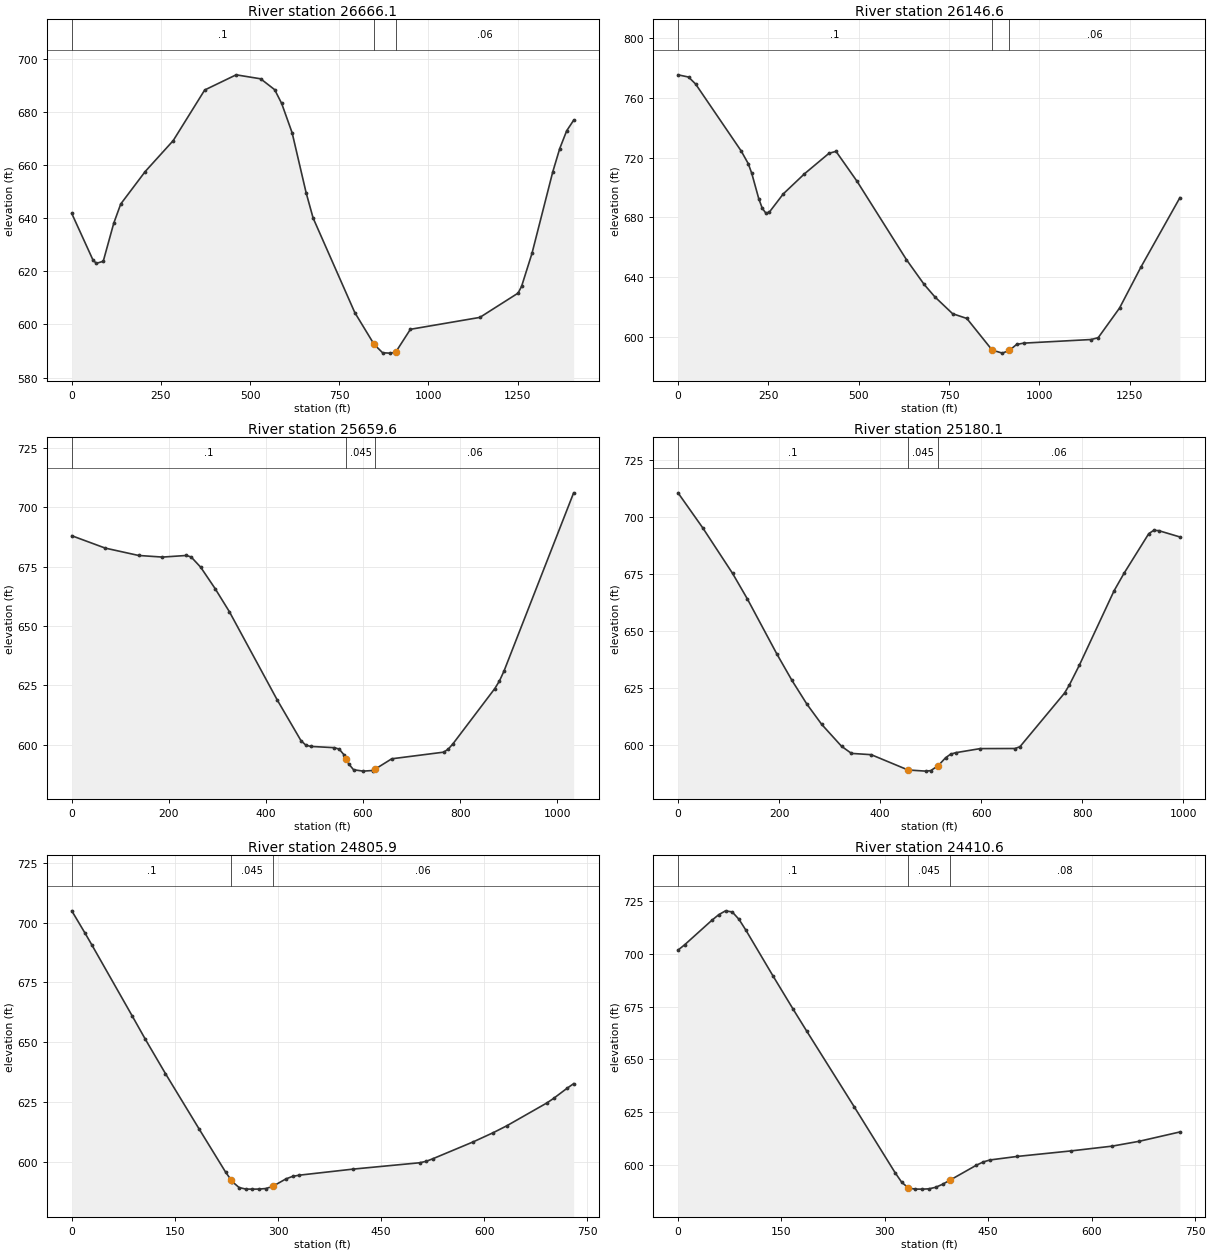
Type RM Length L Ch R = 1 ,26666.1 ,524,519.6,515.1
XS GIS Cut Line= 3
      1722477.97      586451.001     1721964.565      586892.075
     1721755.023      587591.912
#Sta/Elev= 30
       0   641.8    58.9  624.44    68.7     623    88.3   623.8   117.7   638.1
   137.3  645.35     206  657.59   284.5  669.23   372.8  688.28     461  693.99
   529.7  692.49     569   688.4   588.6  683.22     618  672.15   657.2   649.6
   676.8  640.08   793.7  604.48   847.9   592.5   871.7  589.35   891.1  589.21
   907.9  589.48   949.6  598.18  1144.4  602.66  1251.5   611.8  1261.3  614.31
  1290.5  626.73  1348.9  657.48  1368.4  666.23  1387.9  672.93  1407.4  676.89
#Mann= 3 , 0 , 0
       0      .1       0   847.9    .045       0   907.9     .06       0
Bank Sta=847.9,907.9
XS Rating Curve= 0 ,0
Exp/Cntr=0.3,0.1

Type RM Length L Ch R = 1 ,26146.6 ,491.2,487,482.8
XS GIS Cut Line= 3
     1721764.665      586225.528     1721456.061      586719.911
     1721302.743      587510.937
#Sta/Elev= 30
       0  775.53    29.1  774.05    48.6  769.39   174.8  724.48   194.3     716
     204  709.52   223.4   692.5   233.1  686.08   242.8  682.91   252.5  683.46
   291.4  695.77   349.7  709.16   417.7  722.93   437.1  724.23   495.4  704.13
   631.9  651.67   681.1     635   710.5  626.73   759.7  615.42     799  612.24
   869.1  591.05   897.2     589   916.9  590.84   936.5  594.79   956.2   595.7
  1142.9  598.12  1162.5  599.35  1221.5  619.21  1280.4  646.55  1388.5  693.19
#Mann= 3 , 0 , 0
       0      .1       0   869.1    .045       0   916.9     .06       0
Bank Sta=869.1,916.9
XS Rating Curve= 0 ,0
Exp/Cntr=0.3,0.1

Type RM Length L Ch R = 1 ,25659.6 ,486.9,479.4,472
XS GIS Cut Line= 3
     1720968.462      586422.387     1720897.131      587146.939
     1720867.164      587451.328
#Sta/Elev= 30
       0  688.01    68.9   682.8   137.7  679.69   186.9  679.01   236.1  679.69
     246  679.05   265.6  674.74   295.2  665.76   324.7     656   423.1  618.86
   472.2  601.65   482.1  599.77   491.9  599.22   541.1  598.68     551  598.06
   560.8  595.68   564.8  594.11   570.6  591.84   580.5  589.38   600.2   588.8
   619.8  589.06   624.8  589.62   659.2     594   766.3   596.8   775.8  598.12
   785.4  600.35   871.4  623.58     881  626.78   890.5  631.01  1033.9  706.09
#Mann= 3 , 0 , 0
       0      .1       0   564.8    .045       0   624.8     .06       0
Bank Sta=564.8,624.8
XS Rating Curve= 0 ,0
Exp/Cntr=0.3,0.1

Type RM Length L Ch R = 1 ,25180.1 ,384.6,374.2,363.7
XS GIS Cut Line= 3
     1720419.308      586541.637     1720477.502      587491.248
     1720480.072      587533.193
#Sta/Elev= 30
       0  710.59      49  695.23   107.9  675.33   137.3   664.1   196.2  639.77
   225.6   628.4     255  618.06   284.4  609.16   323.7  599.56   343.3  596.45
   382.5  595.88   455.3  589.18   490.4  588.68   500.2  588.89   515.3  591.14
   529.6  594.53   539.4  596.08   549.3  596.74   598.3  598.55     667  598.59
   676.8  599.37     765  622.85   774.8   626.5   794.5  635.14   863.1  667.68
   882.7   675.3   931.8  692.72   941.6  694.15   951.4  694.03   993.4  691.26
#Mann= 3 , 0 , 0
       0      .1       0   455.3    .045       0   515.3     .06       0
Bank Sta=455.3,515.3
XS Rating Curve= 0 ,0
Exp/Cntr=0.3,0.1

Type RM Length L Ch R = 1 ,24805.9 ,404.3,395.3,386.4
XS GIS Cut Line= 2
     1720007.849      586742.905     1720220.357      587441.194
#Sta/Elev= 30
       0  704.99    19.5  695.56    29.2  690.73    87.6  661.15     107  651.23
   136.2  636.89   184.9  613.83   223.8   595.6   232.1  592.21   233.6   591.6
   243.3  589.18     253  588.52   262.8   588.5   272.5  588.52   282.2  588.75
   292.1  589.63   311.4  592.77   321.2  593.84   330.9  594.34   408.8  596.87
   506.1  599.54   515.8  600.17   525.5  601.26   583.9  608.29   613.1  612.15
   632.6     615     691  624.58   700.7  626.46   720.2  630.69   729.9  632.65
#Mann= 3 , 0 , 0
       0      .1       0   232.1    .045       0   292.1     .06       0
Bank Sta=232.1,292.1
XS Rating Curve= 0 ,0
Exp/Cntr=0.3,0.1

Type RM Length L Ch R = 1 ,24410.6 ,398.3,392.7,387.1
XS GIS Cut Line= 2
     1719561.474       586853.87     1719906.889      587494.707
#Sta/Elev= 30
       0  701.92     9.8   704.5    49.2  716.11      59  718.72    68.9  720.57
    78.7  720.03    88.5  716.51    98.4  711.41   137.7   689.7   167.2  673.75
   186.9  663.33   255.8   627.4   314.8  596.27   324.6  591.62     334  589.04
   334.5   588.9   344.3  588.42   354.2  588.41     364  588.55   373.8  589.29
   383.7  590.71     394  592.58   432.9  599.79   442.7  601.31   452.5  602.26
   491.9  603.93   570.6  606.58   629.6  608.82     669  611.13     728  615.56
#Mann= 3 , 0 , 0
       0      .1       0     334    .045       0     394     .08       0
Bank Sta=334,394
XS Rating Curve= 0 ,0
Exp/Cntr=0.3,0.1