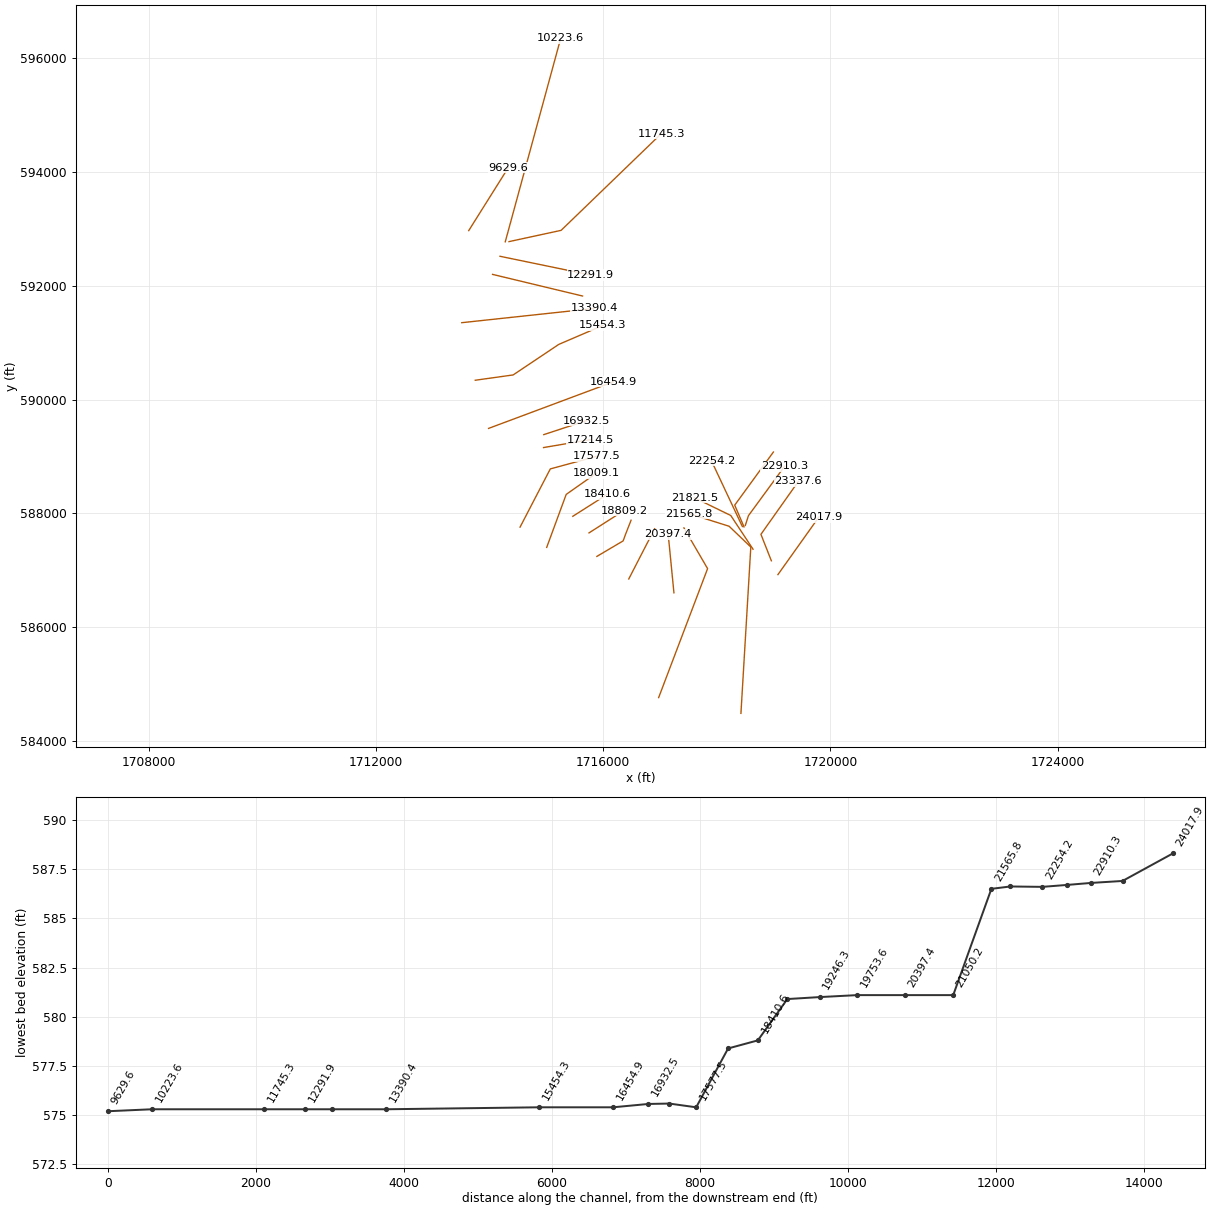
HEC-RAS study EightenmC1.prj: EightenmC1

--- EightenmC1.g01 (geometry) --- (continued)

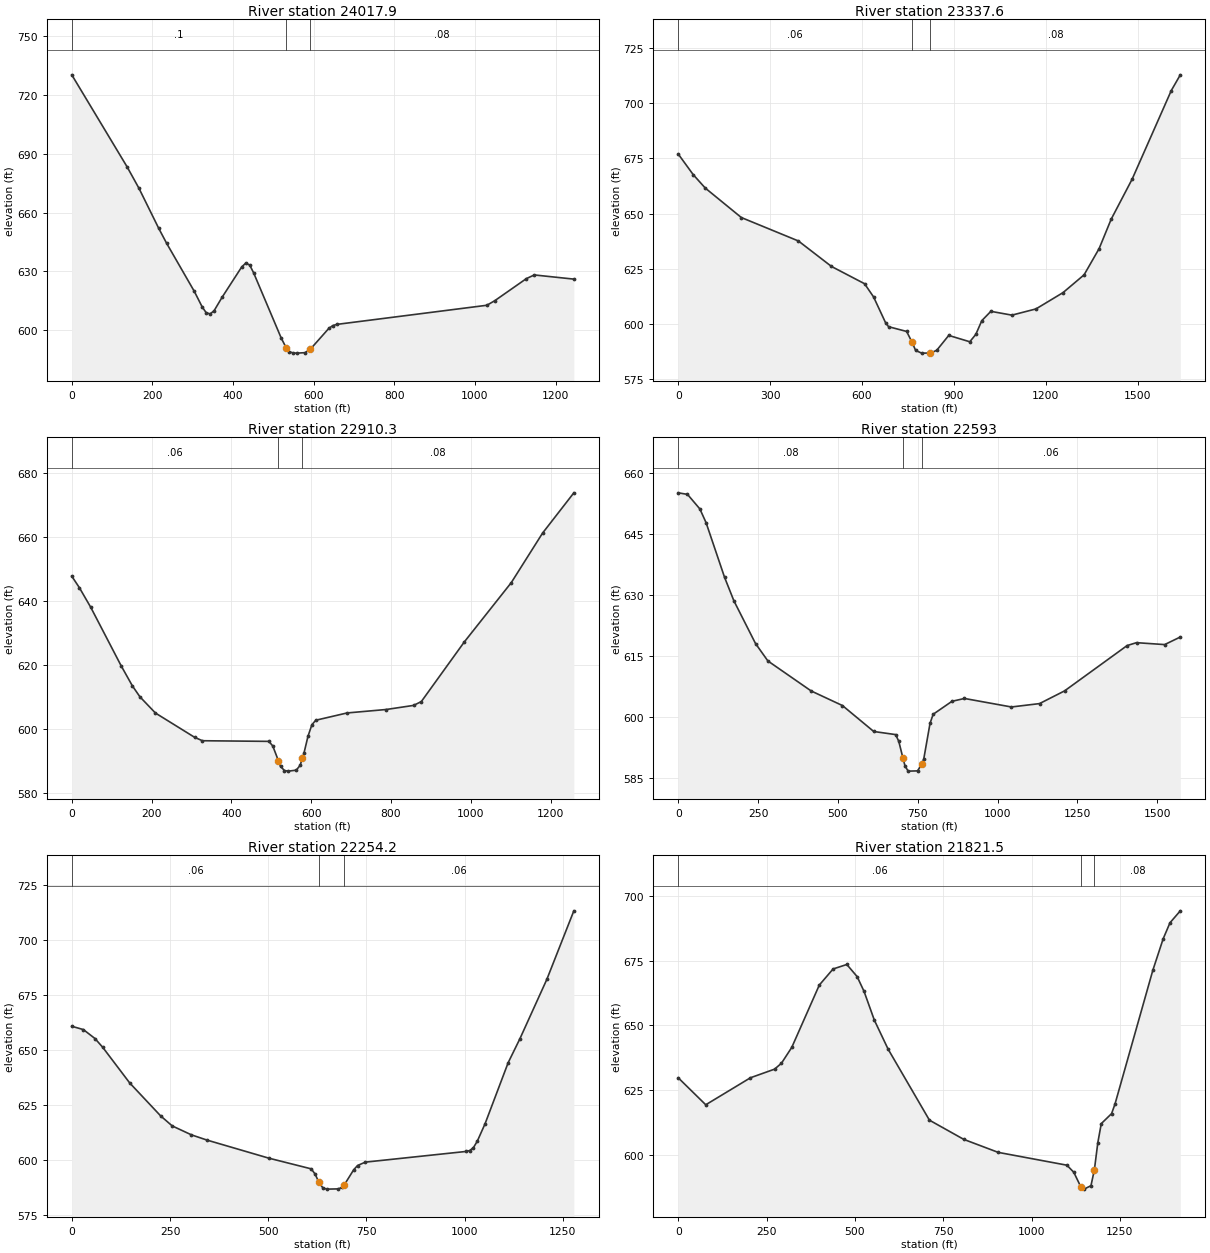
Type RM Length L Ch R = 1 ,24017.9 ,676.3,680.3,684.3
XS GIS Cut Line= 2
     1719074.925      586922.353     1719797.261      587936.593
#Sta/Elev= 30
       0  730.29   137.3  683.31   166.7  672.38   215.7  651.95   235.3  644.32
   303.9  619.81   323.6   611.8   333.4  608.93   343.2   608.3     353  609.94
   372.6  616.73   421.6  632.31   431.4  634.19   441.2  633.27     451  629.28
   519.6  595.93   531.6  591.09   539.2   589.1     549  588.36   558.9   588.3
   578.5  588.54   591.6  590.28   637.3  600.87   647.1  602.32   656.9  602.95
  1029.5  612.72  1049.1  615.05  1127.5  626.32  1147.1  628.19  1245.2  626.06
#Mann= 3 , 0 , 0
       0      .1       0   531.6    .045       0   591.6     .08       0
Bank Sta=531.6,591.6
XS Rating Curve= 0 ,0
Exp/Cntr=0.3,0.1

Type RM Length L Ch R = 1 ,23337.6 ,431.7,427.3,422.9
XS GIS Cut Line= 3
     1718959.419      587165.467     1718775.946      587630.762
     1719433.946      588560.175
#Sta/Elev= 30
       0  676.94      49   667.6    88.3  661.54     206  648.22   392.3  637.62
   500.2   626.1   608.2  618.29   637.6  612.32   676.9  600.62   686.7  598.85
   745.6   596.7   763.1  591.85     775   588.1   794.7   586.9   823.1  586.94
   843.8  588.18     883  594.91   951.7  592.04   971.4  595.38     991   601.6
  1020.5   605.8  1089.2  604.08  1167.7  606.89  1256.1  614.27  1324.8  622.31
  1373.9  634.18  1413.1  647.43  1481.8  665.62  1609.5  705.67  1638.9  712.76
#Mann= 3 , 0 , 0
       0     .06       0   763.1    .045       0   823.1     .08       0
Bank Sta=763.1,823.1
XS Rating Curve= 0 ,0
Exp/Cntr=0.3,0.1

Type RM Length L Ch R = 1 ,22910.3 ,319,317.3,316.4
XS GIS Cut Line= 3
     1718500.965      587786.904     1718556.041      587958.664
     1719193.409      588828.184
#Sta/Elev= 30
       0  647.79      19  644.21    47.5  638.07   123.4  619.84   151.9  613.48
   170.9  610.04   209.8  604.97   307.8  597.39   327.4  596.31     494  596.11
   503.8  594.68   517.9  590.08   523.4  588.26   533.2  586.98     543   586.8
   562.6   587.1   572.4   588.6   577.9  590.79   582.2  592.51     592  597.66
   601.8   601.3   611.6  602.72     690     605     788  606.08   856.6  607.36
   876.2  608.56     984  627.23  1101.7  645.78  1180.1  661.27  1258.5  673.87
#Mann= 3 , 0 , 0
       0     .06       0   517.9    .045       0   577.9     .08       0
Bank Sta=517.9,577.9
XS Rating Curve= 0 ,0
Exp/Cntr=0.3,0.1

Type RM Length L Ch R = 1 ,22593   ,288.4,338.8,389.5
XS GIS Cut Line= 3
     1718478.283      587760.977      1718314.75      588143.884
     1718995.414      589078.237
#Sta/Elev= 30
       0  655.03      29  654.65    67.8  651.07    87.2   647.7   145.2  634.26
   174.3  628.52   242.1  618.02   280.8  613.75   416.4  606.38   514.3   602.8
   612.3  596.43   680.9  595.67   690.7  594.01   703.9  589.86   710.3  587.95
   720.1   586.7   749.4  586.76   763.9  588.52     769   589.7   788.6  598.44
   798.4  600.66   857.2  603.84   896.4  604.54  1043.4  602.45  1131.5  603.28
  1209.9   606.4  1405.8  617.53  1435.2  618.24  1523.4  617.77  1572.4  619.63
#Mann= 3 , 0 , 0
       0     .08       0   703.9    .045       0   763.9     .06       0
Bank Sta=703.9,763.9
XS Rating Curve= 0 ,0
Exp/Cntr=0.3,0.1

Type RM Length L Ch R = 1 ,22254.2 ,402.4,432.6,461.8
XS GIS Cut Line= 2
     1718449.116      587767.455     1717904.842      588923.581
#Sta/Elev= 30
       0  660.59    29.5  659.09      59  655.03    78.6  651.07   147.4  634.85
   226.1  619.89   255.6  615.32   304.7  611.25     344  608.89   501.3  600.68
   609.4  595.81   619.3  593.44   629.1  589.63   638.9  587.22   648.8   586.6
   678.2  586.71   688.1  587.38   693.1  588.41   717.6  595.42   727.4  597.33
     747  598.86  1002.6   603.7  1012.4  604.09  1022.3  605.46  1032.1   608.4
  1051.8  616.28  1110.7  644.07  1140.2   654.8    1209  681.87  1277.8  713.04
#Mann= 3 , 0 , 0
       0     .06       0   629.1    .045       0   693.1     .06       0
Bank Sta=629.1,693.1
XS Rating Curve= 0 ,0
Exp/Cntr=0.3,0.1

Type RM Length L Ch R = 1 ,21821.5 ,248.4,255.7,263
XS GIS Cut Line= 3
      1718637.11      587368.872     1718244.938      587961.876
     1717606.501      588272.922
#Sta/Elev= 30
       0  629.74    77.9  619.29   204.5  629.76   272.7  633.09   292.2  635.39
   321.4  641.53   399.3  665.66   438.3  671.89   477.2  673.63   506.4  668.92
   525.9  663.22   555.1  652.06   594.1  640.82     711  613.33   808.2  605.89
   905.5  600.86  1100.1  595.89  1119.6  593.15    1139  587.63  1148.7  586.62
  1168.2  587.95  1177.9  594.13  1187.6   604.6  1197.4  611.99  1226.6  615.87
  1236.3  619.61  1343.3  671.37  1372.5  683.55  1391.9  689.79  1421.1  694.41
#Mann= 3 , 0 , 0
       0     .06       0    1139    .045       0  1177.9     .08       0
Bank Sta=1139,1177.9
XS Rating Curve= 0 ,0
Exp/Cntr=0.3,0.1

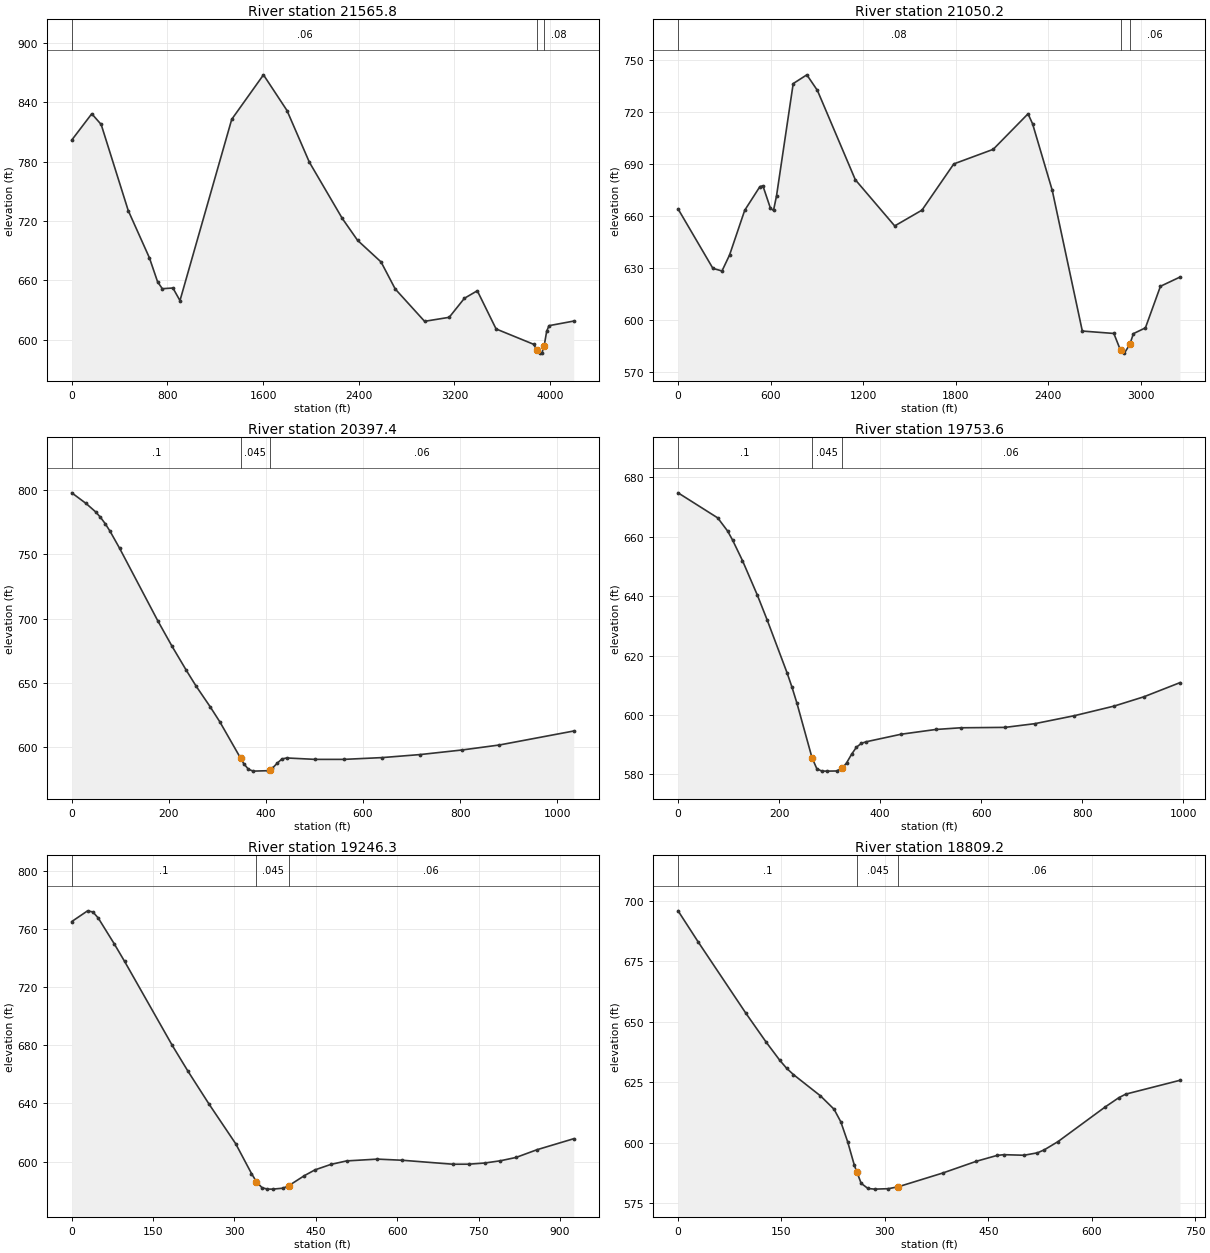
Type RM Length L Ch R = 1 ,21565.8 ,550.2,515.7,481.6
XS GIS Cut Line= 4
     1718424.042       584482.05     1718597.882      587407.591
     1718215.358      587772.888     1717512.015      587994.241
#Sta/Elev= 30
       0  801.88   167.2  828.45   245.9  817.66   472.1  730.64   649.1  682.91
   717.9  658.52   757.3  651.62   845.8  652.33   904.8   639.6  1337.5  822.82
    1603  867.82  1799.7  831.76  1986.6  779.55    2262  722.66  2389.8  700.54
  2586.5  678.62  2704.5  651.38  2950.3  618.65    3156   622.7  3283.3  641.94
  3391.1  649.54  3548.1  610.94  3862.7   595.4  3889.3  589.45  3911.9   586.5
  3931.5  586.65  3949.3  593.26  3970.9  608.46  3990.5  614.25    4197   618.9
#Mann= 3 , 0 , 0
       0     .06       0  3889.3    .045       0  3949.3     .08       0
Bank Sta=3889.3,3949.3
XS Rating Curve= 0 ,0
Exp/Cntr=0.3,0.1

Type RM Length L Ch R = 1 ,21050.2 ,672.3,652.8,632.8
XS GIS Cut Line= 3
     1716976.216      584759.431     1717837.367      587027.505
     1717420.519      587742.947
#Sta/Elev= 30
       0  664.31   225.9     630   284.8   628.5     334  637.75   432.2  663.53
   530.4  677.16     550  677.66   599.2  664.62   618.8  663.45   638.4  671.85
   746.5  736.63   834.9  741.68   903.6  732.65  1149.2  681.14  1404.6   654.5
  1581.4  663.61  1787.6  690.27    2043  698.68  2268.9  719.18  2298.4  713.44
    2426  675.01  2620.9  593.84  2825.4  592.45  2868.6  582.71  2893.6   581.1
  2928.6  586.09  2952.1  592.34    3030  595.69  3127.4  619.67  3254.1  624.99
#Mann= 3 , 0 , 0
       0     .08       0  2868.6    .045       0  2928.6     .06       0
Bank Sta=2868.6,2928.6
XS Rating Curve= 0 ,0
Exp/Cntr=0.3,0.1

Type RM Length L Ch R = 1 ,20397.4 ,669.6,643.8,617.9
XS GIS Cut Line= 3
     1717245.175      586602.664     1717173.843      587327.214
     1717143.875      587631.603
#Sta/Elev= 30
       0  797.96    29.5  789.66    49.2  783.12      59  778.95    68.9  773.94
    78.7  768.12    98.4  754.86   177.1  698.31   206.6  678.37   236.1  659.56
   255.8  647.54   285.3  631.15     305  619.51   348.1  590.98   354.2  586.97
     364   582.5   373.9   581.1   403.4  581.43   408.1  582.35   413.2  583.34
   423.1  587.27   432.9  590.55   442.7  591.36   501.8  590.25   560.8  590.26
   639.5  591.65   718.2  594.03   804.5   597.6     881  601.48  1033.9  612.36
#Mann= 3 , 0 , 0
       0      .1       0   348.1    .045       0   408.1     .06       0
Bank Sta=348.1,408.1
XS Rating Curve= 0 ,0
Exp/Cntr=0.3,0.1

Type RM Length L Ch R = 1 ,19753.6 ,532.9,507.3,481.7
XS GIS Cut Line= 3
     1716450.146       586845.67      1716886.14      587691.278
     1716905.398      587728.629
#Sta/Elev= 30
       0  674.79    78.5  666.35    98.1  661.92   107.9  658.89   127.5  651.97
   156.9  640.37   176.6  631.89   215.8  614.17   225.6   609.3   235.4  603.89
     265  585.68   274.6  581.91   284.4  581.12   294.2   581.1   313.9  581.15
     325  582.11   333.5  583.86   343.3  586.74   353.1  589.17   362.9  590.46
   372.7     591   441.4  593.52     510  595.12   559.1  595.69   647.3  595.83
   706.2  597.08   784.6  599.77   863.1     603     922  606.13   993.4  610.89
#Mann= 3 , 0 , 0
       0      .1       0     265    .045       0     325     .06       0
Bank Sta=265,325
XS Rating Curve= 0 ,0
Exp/Cntr=0.3,0.1

Type RM Length L Ch R = 1 ,19246.3 ,435.5,437.1,438.7
XS GIS Cut Line= 4
     1715889.433       587242.65     1716351.211      587515.053
     1716395.326      587635.414     1716490.817      587878.547
#Sta/Elev= 30
       0  765.11    29.2  772.49      39  771.69    48.7  767.61      78  749.99
    97.5  737.65   185.2  679.97   214.4  662.06   253.4  639.36   302.2  612.29
   331.4  591.75   340.4  586.16   350.9  581.94   360.7  581.03   370.4     581
   389.9  581.67   400.4  583.44   428.9  590.27   448.4  594.24   477.6  597.99
   506.9  600.42   563.6  601.65   609.4  600.87     703  598.13     732  598.16
   761.1  598.95   790.1  600.49   819.1  602.79   857.8  608.11   925.5  615.68
#Mann= 3 , 0 , 0
       0      .1       0   340.4    .045       0   400.4     .06       0
Bank Sta=340.4,400.4
XS Rating Curve= 0 ,0
Exp/Cntr=0.3,0.1

Type RM Length L Ch R = 1 ,18809.2 ,398.7,398.6,398.5
XS GIS Cut Line= 2
      1715750.76       587655.75     1716364.316       588047.71
#Sta/Elev= 30
       0  695.84    29.5  682.86    98.4  653.54   127.9  641.57   147.6  634.09
   157.4  630.85   167.3  628.22   206.6  619.41   226.3   613.9   236.1  608.68
     246  600.48   255.8   590.7   259.5  587.91   265.6   583.3   275.5  581.16
   285.3   580.9     305  581.08   319.5  581.88   383.7  587.53   432.9  592.42
   462.4  594.79   472.3  595.13   501.8  594.89   521.4   595.9   531.3  597.14
     551   600.5   619.8  614.88   639.5  618.68   649.4  620.13   728.1  625.85
#Mann= 3 , 0 , 0
       0      .1       0   259.5    .045       0   319.5     .06       0
Bank Sta=259.5,319.5
XS Rating Curve= 0 ,0
Exp/Cntr=0.3,0.1

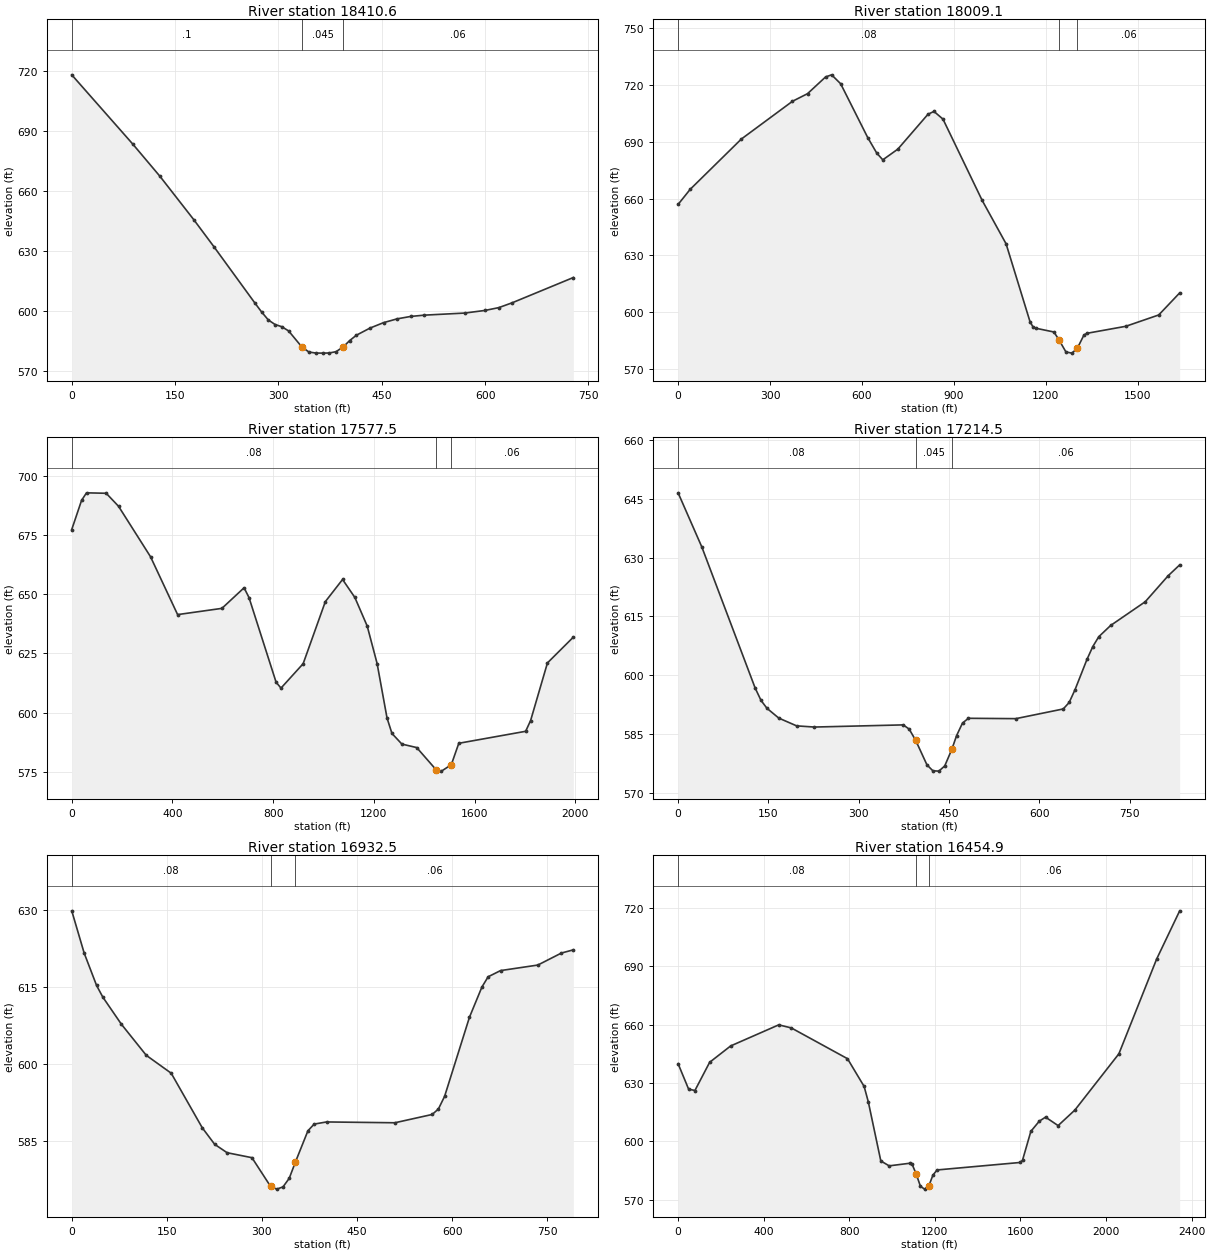
Type RM Length L Ch R = 1 ,18410.6 ,399.4,401.5,403.6
XS GIS Cut Line= 2
     1715465.829       587947.82     1716080.454      588337.973
#Sta/Elev= 30
       0  718.25    88.5  683.58   127.9  667.45   177.1  645.68   206.6  632.01
   265.6  604.01   275.5  599.45   285.3  595.43   295.1  593.14     305  592.02
   314.8  589.92     334  581.89   344.3  579.34   354.2  578.85     364   578.8
   373.8  578.87   383.7  579.54     394  581.92   403.4   585.1   413.2  587.79
   432.9  591.35   452.5  594.07   472.2  595.97   491.9  597.18   511.6  597.83
   570.6  598.88   600.1  600.21   619.8   601.6   639.5  604.06     728  616.68
#Mann= 3 , 0 , 0
       0      .1       0     334    .045       0     394     .06       0
Bank Sta=334,394
XS Rating Curve= 0 ,0
Exp/Cntr=0.3,0.1

Type RM Length L Ch R = 1 ,18009.1 ,446.8,431.6,416.4
XS GIS Cut Line= 3
     1715006.069      587400.848     1715349.119      588332.243
     1715876.769      588703.274
#Sta/Elev= 30
       0  656.98    39.3  664.93   206.4  691.52   373.4  711.49   422.6  715.51
   481.5  724.35   501.2  725.47   530.7  720.76   619.1  692.31   648.6   684.1
   668.3  680.54   717.4   686.2   815.7  704.61   835.3  706.13   864.8  702.06
   992.6  659.15  1070.8  636.17  1148.9  595.03  1158.7  592.24  1168.5  591.53
  1227.1  589.55  1243.6  585.38  1266.2  579.01  1285.8  578.39  1303.6     581
  1324.9  587.92  1334.6  588.86  1461.7  592.57  1569.2  598.56  1637.6  610.22
#Mann= 3 , 0 , 0
       0     .08       0  1243.6    .045       0  1303.6     .06       0
Bank Sta=1243.6,1303.6
XS Rating Curve= 0 ,0
Exp/Cntr=0.3,0.1

Type RM Length L Ch R = 1 ,17577.5 ,368.2,363,357.9
XS GIS Cut Line= 4
     1714537.155      587756.808     1715069.275       588780.74
     1715743.012      588963.784     1715878.272      589000.532
#Sta/Elev= 30
       0  677.26    39.1  689.57    58.7  692.73   136.9  692.54   185.8  687.07
   312.9  665.79   420.5  641.39   596.5  644.02   684.5   652.7   704.1  648.57
   811.7  612.88   831.2  610.41   919.2   620.7  1007.3  646.87  1075.7   656.2
  1124.6  648.61  1173.6  636.56  1212.9  620.77  1252.3  597.81  1271.9  591.28
  1311.3   586.8  1370.3  585.33  1447.6  575.94  1468.6   575.4  1507.6   578.1
  1537.4  587.14  1802.9  592.19  1822.6  596.72  1889.5  621.02  1992.3  631.88
#Mann= 3 , 0 , 0
       0     .08       0  1447.6    .045       0  1507.6     .06       0
Bank Sta=1447.6,1507.6
XS Rating Curve= 0 ,0
Exp/Cntr=0.3,0.1

Type RM Length L Ch R = 1 ,17214.5 ,275.6,282,288.3
XS GIS Cut Line= 3
      1714950.96      589156.595      1715668.82      589277.679
     1715772.141      589295.107
#Sta/Elev= 30
       0  646.49    39.4  632.69   127.9  596.77   137.7   593.6   147.6  591.59
   167.2   589.1   196.8  587.12   226.3  586.82   373.8  587.37   383.7  586.29
   394.5  583.42   413.2  577.18     423  575.68   432.9  575.59   442.7  576.91
   454.5  581.15   462.4  584.64   472.2  587.84     482  589.05   560.8  588.96
   639.5  591.43   649.3  593.08   659.1  596.36   678.8  604.03   688.6  607.34
   698.5  609.84   718.2   612.7   775.6  618.74   813.7  625.37   832.8  628.13
#Mann= 3 , 0 , 0
       0     .08       0   394.5    .045       0   454.5     .06       0
Bank Sta=394.5,454.5
XS Rating Curve= 0 ,0
Exp/Cntr=0.3,0.1

Type RM Length L Ch R = 1 ,16932.5 ,475.3,477.6,479.9
XS GIS Cut Line= 3
     1714955.005      589383.968     1715653.701       589613.08
     1715706.887       589630.52
#Sta/Elev= 30
       0  629.92    19.6  621.67    39.2  615.34      49  613.07    78.4  607.76
   117.6   601.7   156.9  598.21   205.9  587.55   225.5  584.32   245.1  582.68
   284.3  581.71   313.7   576.1   323.5  575.57   333.3  576.01   343.1  577.68
   352.9  580.87   372.6  586.96   382.4  588.27     402  588.69   509.8  588.53
   568.6  590.15   578.4  591.21   588.2  593.68   627.5  609.16   647.1  615.04
   656.9  617.04   676.5  618.25   735.3  619.33   772.6  621.68   791.3   622.3
#Mann= 3 , 0 , 0
       0     .08       0   313.7    .045       0   352.9     .06       0
Bank Sta=313.7,352.9
XS Rating Curve= 0 ,0
Exp/Cntr=0.3,0.1

Type RM Length L Ch R = 1 ,16454.9 ,989.6,1000.6,1011.7
XS GIS Cut Line= 5
     1713983.257      589493.278     1714287.134      589606.642
     1715034.952      589885.621     1715509.463      590062.641
     1716179.412      590312.571
#Sta/Elev= 30
       0   639.9    49.1  626.83    78.6  626.12   147.4  640.62   245.7  649.04
   470.3  659.88   528.7  658.32   791.6  642.48   869.4  628.19   888.9  620.28
   947.3   589.9   986.2  587.37  1083.6  588.72  1093.3  588.24  1112.8  583.16
  1132.2  576.92  1151.7   575.4  1171.2   576.9  1190.7  582.57  1210.2  585.26
  1599.7  589.12  1609.5  590.25  1648.5  605.11  1687.7  610.32  1717.1  612.42
  1775.9  608.07  1854.2  616.06  2059.9     645  2236.2  693.69    2344  718.52
#Mann= 3 , 0 , 0
       0     .08       0  1112.8    .045       0  1171.2     .06       0
Bank Sta=1112.8,1171.2
XS Rating Curve= 0 ,0
Exp/Cntr=0.3,0.1

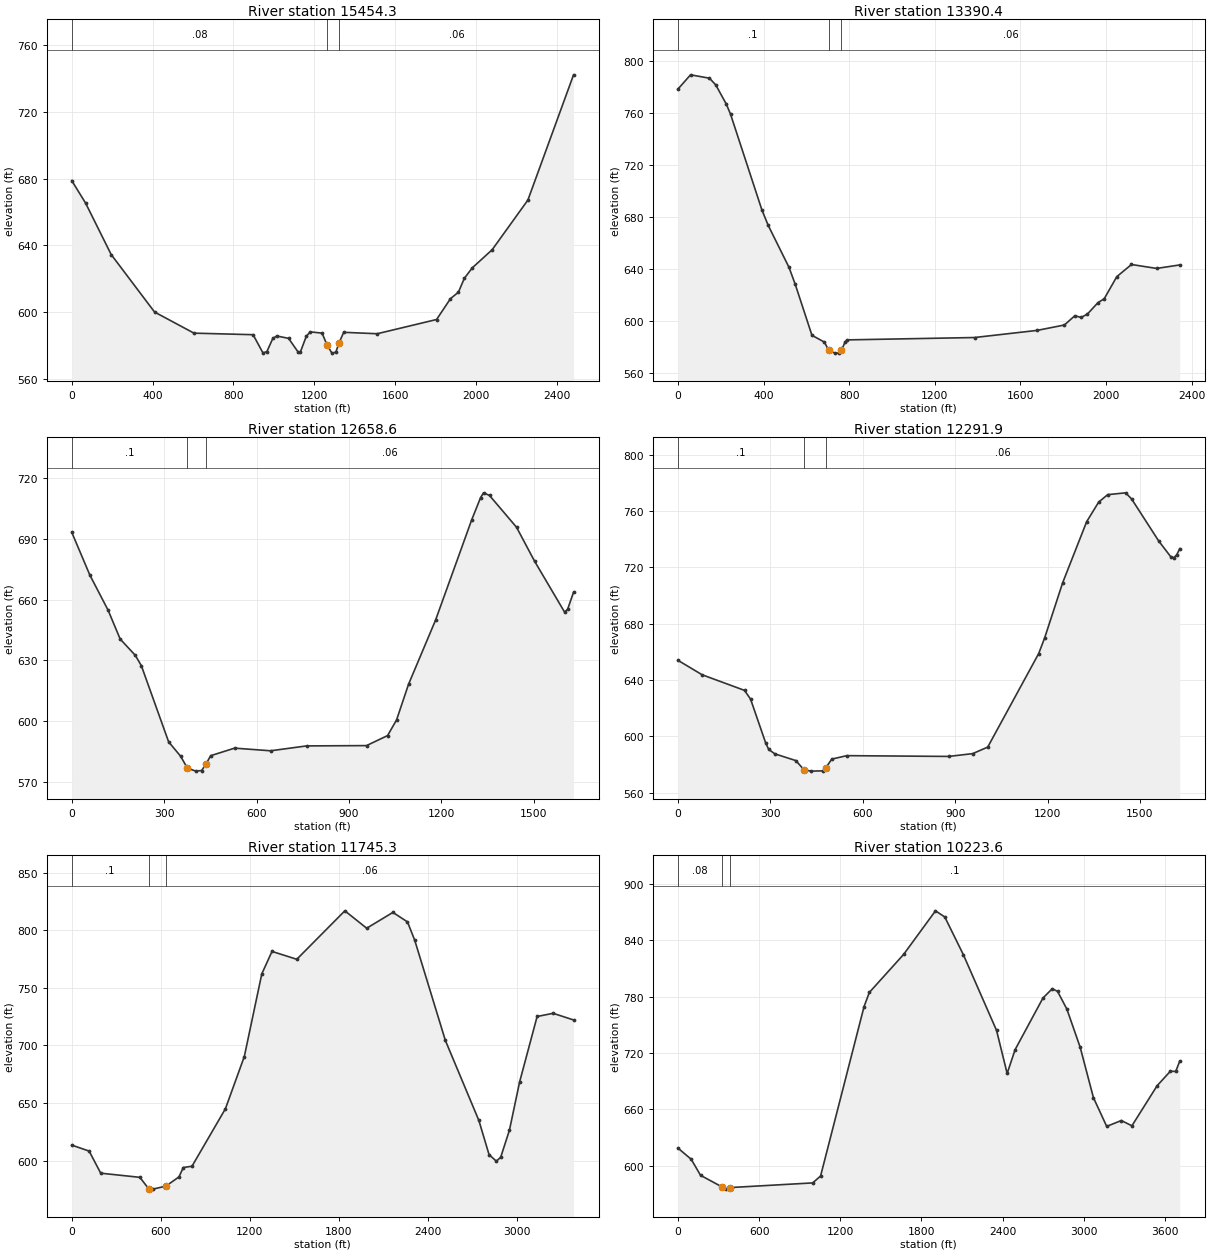
Type RM Length L Ch R = 1 ,15454.3 ,2091.4,2063.9,2011
XS GIS Cut Line= 4
     1713749.271      590340.409      1714415.98      590433.498
     1715218.239      590970.181     1715994.468       591303.68
#Sta/Elev= 30
       0  678.84    68.3  665.41   195.1  634.52   409.8  600.04   604.9  587.38
   897.4  586.45   946.2  575.52   965.7  576.33   994.9  584.19  1014.4  585.69
  1072.9  584.26  1121.7  575.79  1131.4  576.08  1160.7   585.5  1180.2  588.15
  1238.7   587.4  1262.9  580.42  1287.4   575.4  1306.9     576  1322.9  581.63
  1345.9  587.88  1511.6  587.03  1805.4  595.56  1874.2  608.07  1913.5  611.95
  1942.9   620.3  1982.2  626.55  2080.5  637.41  2257.3   667.2  2483.2  742.29
#Mann= 3 , 0 , 0
       0     .08       0  1262.9    .045       0  1322.9     .06       0
Bank Sta=1262.9,1322.9
XS Rating Curve= 0 ,0
Exp/Cntr=0.3,0.1

Type RM Length L Ch R = 1 ,13390.4 ,748.3,731.8,715.3
XS GIS Cut Line= 5
      1713511.92      591352.338       1713834.4      591386.974
     1714627.997       591472.21     1715131.556      591526.295
     1715842.518      591602.656
#Sta/Elev= 30
       0  778.02      59     789   147.4  786.41   176.9  781.24     226  766.55
   245.7  758.83   392.5  685.17   421.7  673.43     519  641.14   548.2  628.08
   626.1  588.99   684.5  583.75   703.8  577.64   733.2   575.3   752.6   575.3
   763.8  577.41   781.8  584.18   791.6  585.47  1385.5  587.28  1677.9  592.75
  1805.3   596.9  1854.2  604.02  1883.6  602.68    1913  605.31    1962  614.03
  1991.4  617.05  2050.2  634.02  2118.7  643.36  2236.2  640.33    2344  643.02
#Mann= 3 , 0 , 0
       0      .1       0   703.8    .045       0   763.8     .06       0
Bank Sta=703.8,763.8
XS Rating Curve= 0 ,0
Exp/Cntr=0.3,0.1

Type RM Length L Ch R = 1 ,12658.6 ,365,366.7,368.6
XS GIS Cut Line= 4
     1714053.383      592201.623      1714368.75      592125.884
     1715144.844      591939.496     1715637.296      591821.227
#Sta/Elev= 30
       0   693.3      59  672.08   117.9  654.84   157.2  640.55   206.4   632.5
     226  627.37   314.5  589.76   353.5  582.65     375  576.87   402.2   575.3
   421.7  575.61     435   578.6   450.9  582.92   528.7  586.66   645.6  585.35
   762.4  587.76     957  587.91  1025.2  592.86  1054.4  600.57  1093.3   618.2
  1180.9  649.85  1297.8  699.23    1327  710.37  1336.8   712.8  1356.2  711.49
  1443.9   695.8  1502.3  679.07  1599.7  653.92  1609.5  655.16    1629  663.69
#Mann= 3 , 0 , 0
       0      .1       0     375    .045       0     435     .06       0
Bank Sta=375,435
XS Rating Curve= 0 ,0
Exp/Cntr=0.3,0.1

Type RM Length L Ch R = 1 ,12291.9 ,488.8,546.6,600.1
XS GIS Cut Line= 4
     1714184.676      592520.062     1714502.308      592454.471
     1715283.978      592293.055     1715779.969      592190.632
#Sta/Elev= 30
       0  654.03    78.6  643.75   216.2  632.66   235.9  626.43     285  595.27
   294.8  590.74   314.5  587.59   382.7  582.79   408.8   576.4   431.4   575.3
   470.3  575.49   480.1  577.69   499.5  583.84   548.2  586.29   879.2  585.74
     957  587.74  1005.7  592.36  1171.2  658.81  1190.7  670.01  1249.1  709.15
    1327  752.51    1366  766.41  1395.2  771.69  1453.6  772.99  1473.1  768.56
  1560.8  738.79  1599.7  727.66  1609.5  726.85  1619.2   728.9    1629  733.29
#Mann= 3 , 0 , 0
       0      .1       0   408.8    .045       0   480.1     .06       0
Bank Sta=408.8,480.1
XS Rating Curve= 0 ,0
Exp/Cntr=0.3,0.1

Type RM Length L Ch R = 1 ,11745.3 ,1510,1521.7,1536.6
XS GIS Cut Line= 3
     1714342.824        592777.9      1715259.73      592975.958
     1717020.485       594674.52
#Sta/Elev= 30
       0  613.52   117.3  608.32   195.4  589.14   459.3  585.54   517.8  575.79
   547.2   575.3   635.1  577.91   723.1  585.91   752.4  594.06     811  595.18
  1036.3  645.03    1164  690.43  1281.9   762.2  1350.7  781.65  1517.8  774.82
    1842  816.89  1989.4  801.78  2166.2  815.53  2264.5  807.28  2313.6  791.25
  2519.9   704.4  2745.9  634.92  2814.7  605.26  2863.8  599.56  2893.3     603
  2952.2  626.49    3021  668.44  3138.9  725.16    3247  727.93  3384.6  722.15
#Mann= 3 , 0 , 0
       0      .1       0   517.8    .045       0   635.1     .06       0
Bank Sta=517.8,635.1
XS Rating Curve= 0 ,0
Exp/Cntr=0.3,0.1

Type RM Length L Ch R = 1 ,10223.6 ,610.3,594,578.6
XS GIS Cut Line= 5
      1714277.21      592774.719     1714362.514      593087.634
     1714572.441      593857.695     1714705.645      594346.319
     1715252.586       596352.63
#Sta/Elev= 30
       0  618.97    98.3  607.04   167.1  590.02   326.5   577.6   353.5   575.3
   386.5  576.96     996  581.91  1054.4  589.24  1375.7  769.35  1414.7  784.42
  1668.2  824.86  1903.6  871.19  1972.3  864.66  2109.6  824.56  2354.8  744.07
  2433.3  698.28  2492.2  723.66  2698.1  778.51  2766.8  788.39    2806  785.49
  2874.7  766.68  2972.8  726.18  3070.9  672.55    3169  642.01  3276.9  648.23
  3355.4  642.66  3541.7  685.26  3639.8  700.71    3679   700.4  3708.5  711.35
#Mann= 3 , 0 , 0
       0     .08       0   326.5    .045       0   386.5      .1       0
Bank Sta=326.5,386.5
XS Rating Curve= 0 ,0
Exp/Cntr=0.3,0.1

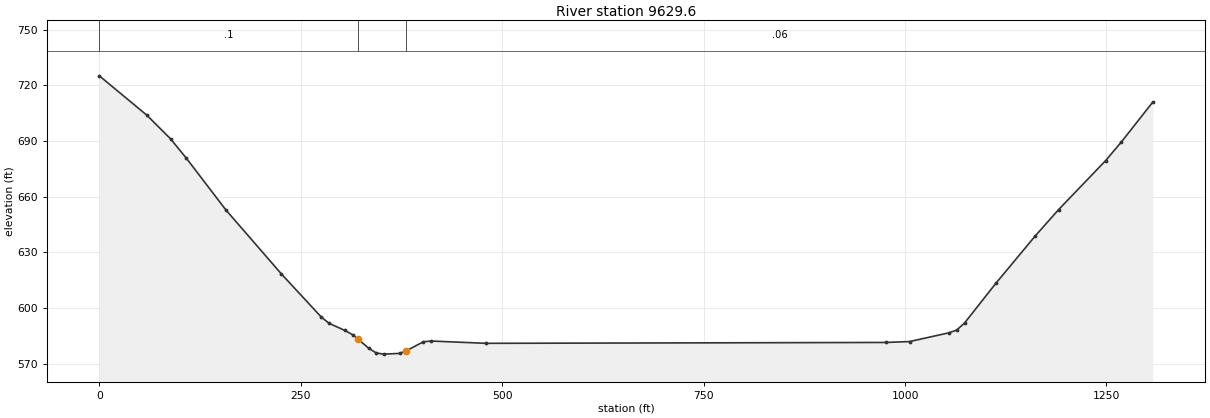
Type RM Length L Ch R = 1 ,9629.6  ,608.7,611,612.2
XS GIS Cut Line= 4
     1713633.926      592971.099     1713806.533      593245.689
     1714231.307      593921.433     1714329.735      594078.015
#Sta/Elev= 30
       0  725.15      59  703.92    88.4   691.2   108.1   680.7   157.2  652.82
     226  618.39   275.2   595.3     285  591.83   304.7  587.96   314.5  585.61
   320.8  583.42   334.1  578.44   343.8   575.8   353.5   575.2     373  575.61
   380.8  576.97   402.2  581.86   411.9  582.26   480.1  581.02   976.5  581.49
  1005.7  581.98  1054.4  586.68  1064.1  588.15  1073.8  591.95  1112.8  613.42
  1161.4  638.79  1190.6  653.09    1249   679.5  1268.5  689.54  1307.4  710.98
#Mann= 3 , 0 , 0
       0      .1       0   320.8    .045       0   380.8     .06       0
Bank Sta=320.8,380.8
XS Rating Curve= 0 ,0
Exp/Cntr=0.3,0.1