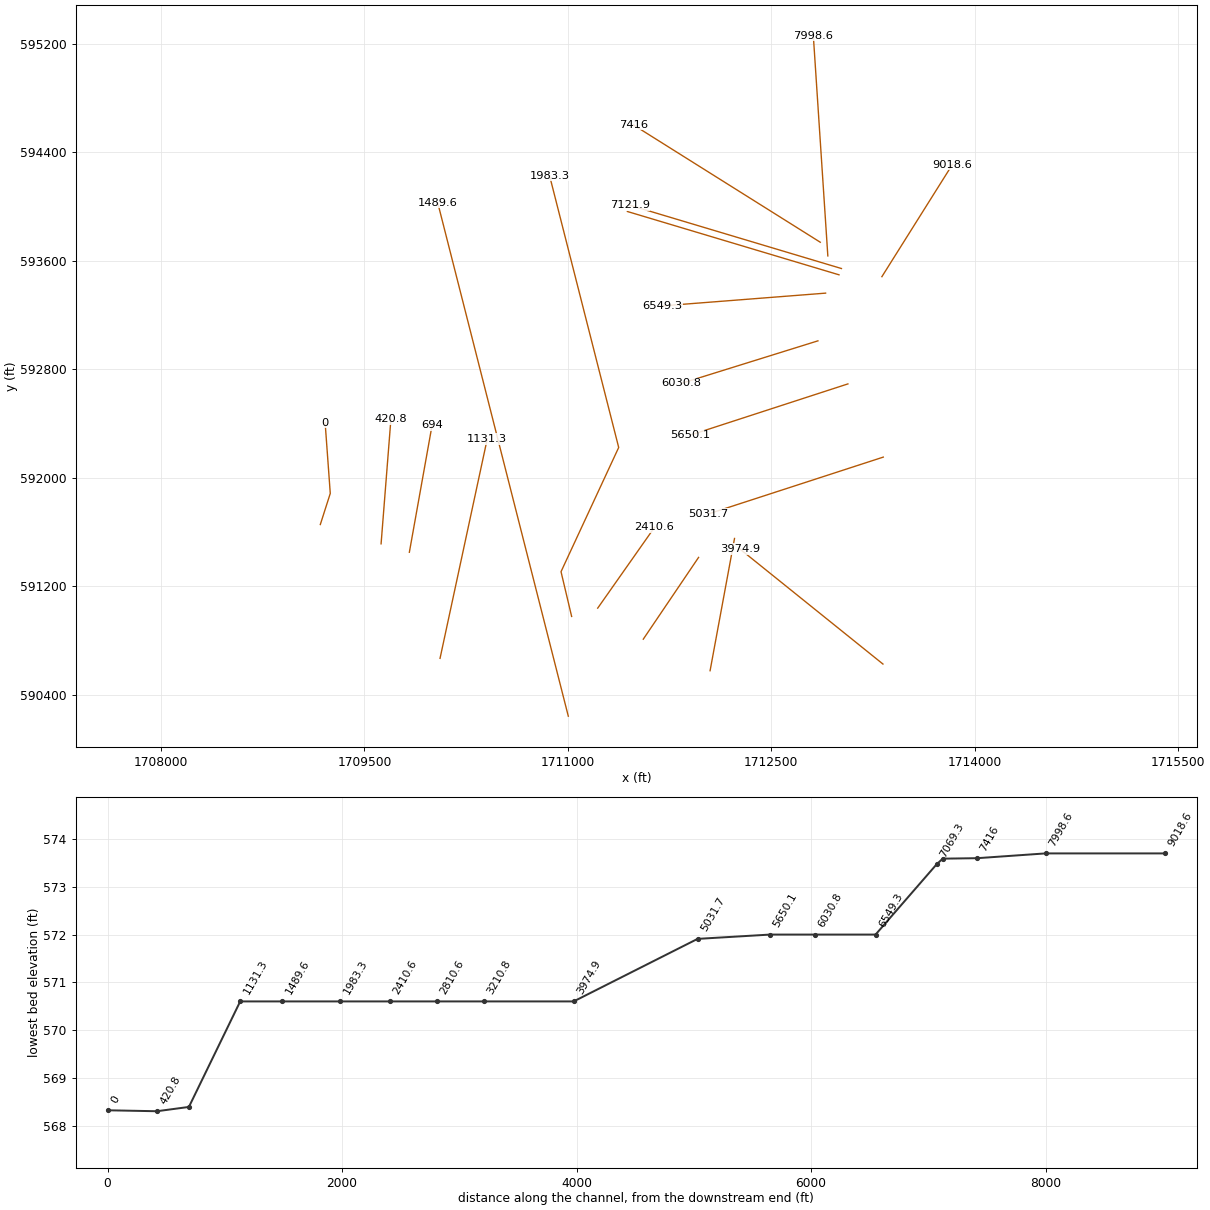
HEC-RAS study EightenmC1.prj: EightenmC1

--- EightenmC1.g01 (geometry) --- (continued)

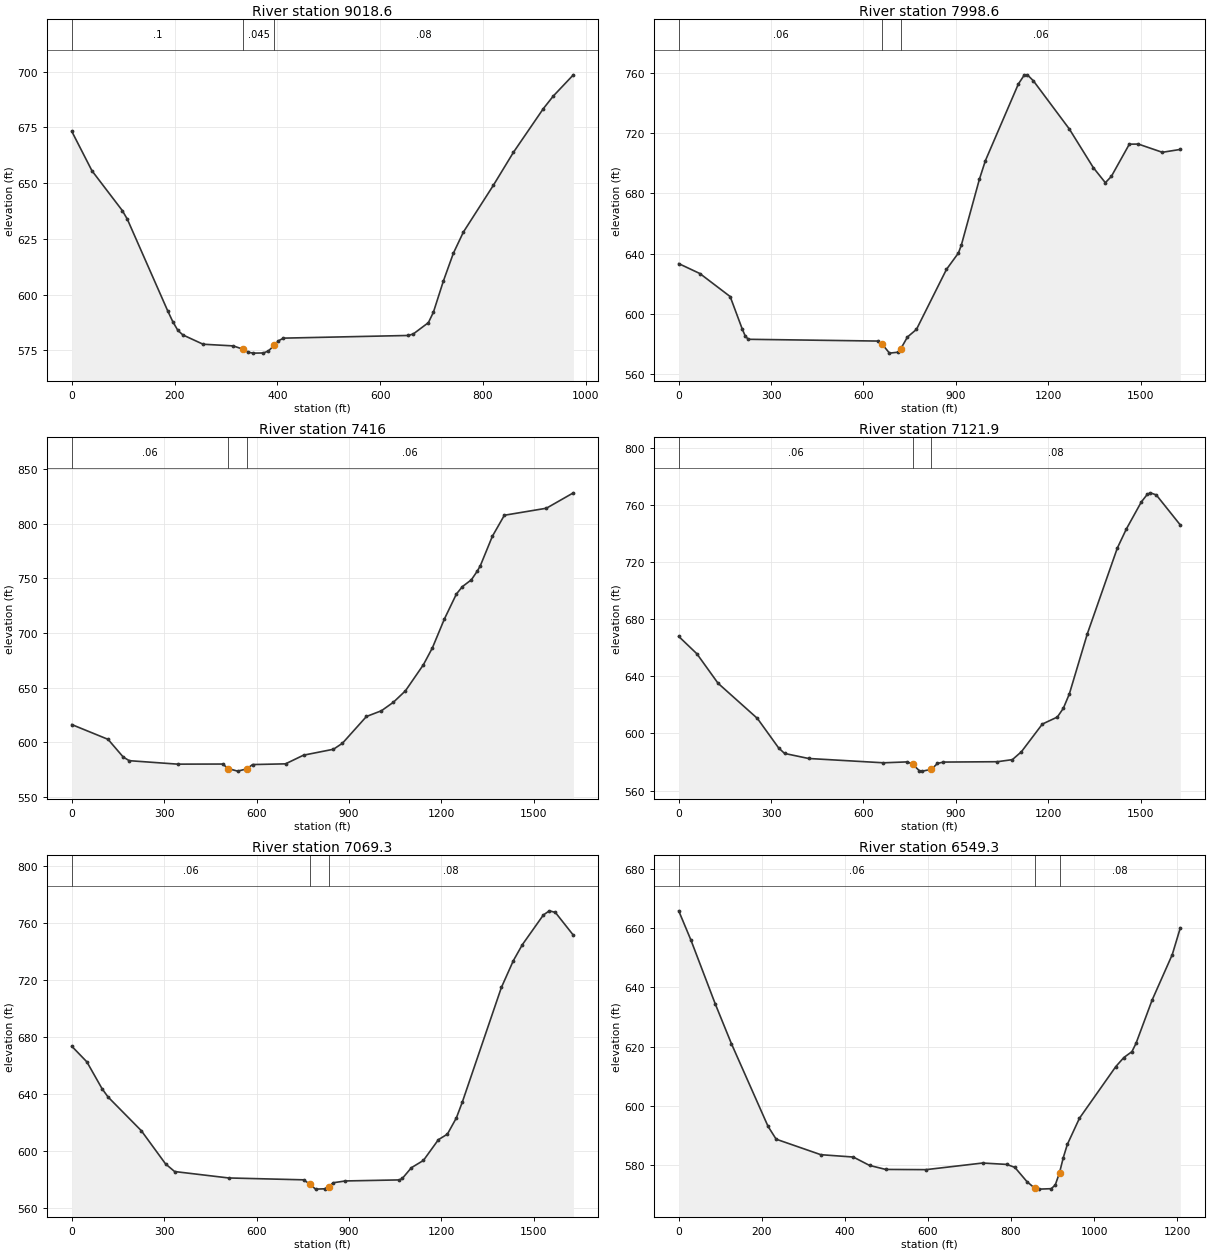
Type RM Length L Ch R = 1 ,9018.6  ,992.5,1020,1048.5
XS GIS Cut Line= 3
     1713316.033      593482.066      1713488.64      593756.656
     1713835.509      594308.467
#Sta/Elev= 30
       0  673.29    39.3  655.58    98.3  637.73   108.1  633.86   186.7  592.69
   196.6  587.84   206.4  583.94   216.2  581.87   255.5   577.7   314.5  576.94
   333.7   575.4   343.8  574.06   353.5   573.7     373  573.77   382.7  574.68
   393.7  577.15   402.2  579.21   411.9  580.43   655.1  581.63   664.8  582.34
     694  587.39   703.7  592.04   723.2   606.1   742.6  618.55   762.1  628.06
   820.5  649.08   859.4  663.83   917.7  683.48   937.2  689.16   976.1  698.64
#Mann= 3 , 0 , 0
       0      .1       0   333.7    .045       0   393.7     .08       0
Bank Sta=333.7,393.7
XS Rating Curve= 0 ,0
Exp/Cntr=0.3,0.1

Type RM Length L Ch R = 1 ,7998.6  ,539.9,582.6,625.4
XS GIS Cut Line= 4
     1712917.354      593635.145     1712896.037      593958.778
     1712843.578      594755.215     1712810.292      595260.575
#Sta/Elev= 30
       0   633.3    68.8  626.68   167.1  611.36   206.4  589.72   216.2  585.05
     226  582.91   645.6  581.74   660.4  579.73   684.5   573.7   713.7  574.35
   720.4  576.33   742.9  584.45   772.1   589.5   869.4   629.4   908.4  640.36
   918.1   645.8   976.5  689.46     996  701.87    1103  752.86  1122.5   758.9
  1132.2  758.97  1151.7  755.02  1268.6  722.88  1346.5  697.17  1385.5  687.15
  1404.9  691.32  1463.4  712.81  1492.6  712.87  1570.5   707.4    1629  709.31
#Mann= 3 , 0 , 0
       0     .06       0   660.4    .045       0   720.4     .06       0
Bank Sta=660.4,720.4
XS Rating Curve= 0 ,0
Exp/Cntr=0.3,0.1

Type RM Length L Ch R = 1 ,7416    ,281.1,294,306.5
XS GIS Cut Line= 4
     1712861.688      593735.988     1712587.007      593908.449
     1711911.037      594332.862     1711482.116      594602.164
#Sta/Elev= 30
       0   616.2   117.9  602.67   167.1  586.51   186.7  583.16   343.8  579.99
   489.8  580.08   508.3  575.95   538.5   573.6   568.3  575.62   587.1  579.61
   694.2  580.26   752.6  588.18     850  593.62   879.2  599.14     957  623.57
  1005.7  628.82  1044.6  636.62  1083.6  647.04    1142  670.93  1171.2  686.37
  1210.2  712.79  1249.1  735.56  1268.6  742.37  1297.8  748.61  1317.3   756.7
    1327  761.57    1366  788.44  1404.9  807.64  1541.3  814.05    1629  828.15
#Mann= 3 , 0 , 0
       0     .06       0   508.3    .045       0   568.3     .06       0
Bank Sta=508.3,568.3
XS Rating Curve= 0 ,0
Exp/Cntr=0.3,0.1

Type RM Length L Ch R = 1 ,7121.9  ,52.3,52.6,55.1
XS GIS Cut Line= 4
     1713017.785      593542.111     1712707.061      593635.079
     1711942.392      593863.864     1711457.189      594009.034
#Sta/Elev= 30
       0  668.05      59  655.87   127.8  635.19   255.5  610.55   324.3  589.92
   343.8  585.99   421.7  582.46     665  579.43   742.9  580.07   760.8  578.24
   781.8  573.79   791.6  573.59   820.8  574.86   840.2  578.98   859.7  579.94
  1034.9  580.19  1083.6  581.65  1112.8  587.15  1180.9  606.58  1229.6  611.51
  1249.1  617.66  1268.6  627.73    1327  669.89  1424.4  729.98  1453.6  743.31
  1502.3  762.31  1521.8  767.67  1531.6  768.71    1551  767.22    1629  746.14
#Mann= 3 , 0 , 0
       0     .06       0   760.8    .045       0   820.8     .08       0
Bank Sta=760.8,820.8
XS Rating Curve= 0 ,0
Exp/Cntr=0.3,0.1

Type RM Length L Ch R = 1 ,7069.3  ,503.8,520,534.1
XS GIS Cut Line= 4
      1712999.77      593495.772     1712689.045      593588.739
     1711924.376      593817.525     1711439.173      593962.695
#Sta/Elev= 30
       0  673.77    49.1  662.78    98.3  643.99   117.9  638.13     226  614.46
   304.7  591.16   334.1  585.81   509.3  581.31   752.6     580   773.8  576.91
   791.6  573.47   820.8  573.69   833.8  575.26     850  577.98   888.9  579.21
  1064.1  579.94  1073.8  581.05    1103  588.51    1142  593.61  1190.7  608.17
  1219.9  612.07  1249.1  623.49  1268.6   634.7  1395.2  714.99  1434.2  733.87
  1463.4  745.06  1531.6  765.88    1551  768.78  1570.5  767.66    1629  751.66
#Mann= 3 , 0 , 0
       0     .06       0   773.8    .045       0   833.8     .08       0
Bank Sta=773.8,833.8
XS Rating Curve= 0 ,0
Exp/Cntr=0.3,0.1

Type RM Length L Ch R = 1 ,6549.3  ,508.3,518.6,528.7
XS GIS Cut Line= 3
     1712900.957      593360.628     1712433.076      593324.089
     1711696.783      593266.589
#Sta/Elev= 30
       0  665.83    29.3  656.01      88  634.45   127.1  620.98   215.1  593.17
   234.6  588.84   342.2  583.61   420.4  582.82   459.5  579.99   498.5  578.64
   595.6  578.57   731.7   580.8     790  580.33   809.4  579.33   838.6  574.51
   856.9  572.36   867.7     572   896.9  572.15   906.6  573.38   916.9  577.53
     926  582.63   935.8   587.1   964.9   595.9  1052.4  613.31  1071.8  616.37
  1091.2  618.35    1101  621.11  1139.8  635.72  1188.4  651.08  1207.8  660.12
#Mann= 3 , 0 , 0
       0     .06       0   856.9    .045       0   916.9     .08       0
Bank Sta=856.9,916.9
XS Rating Curve= 0 ,0
Exp/Cntr=0.3,0.1

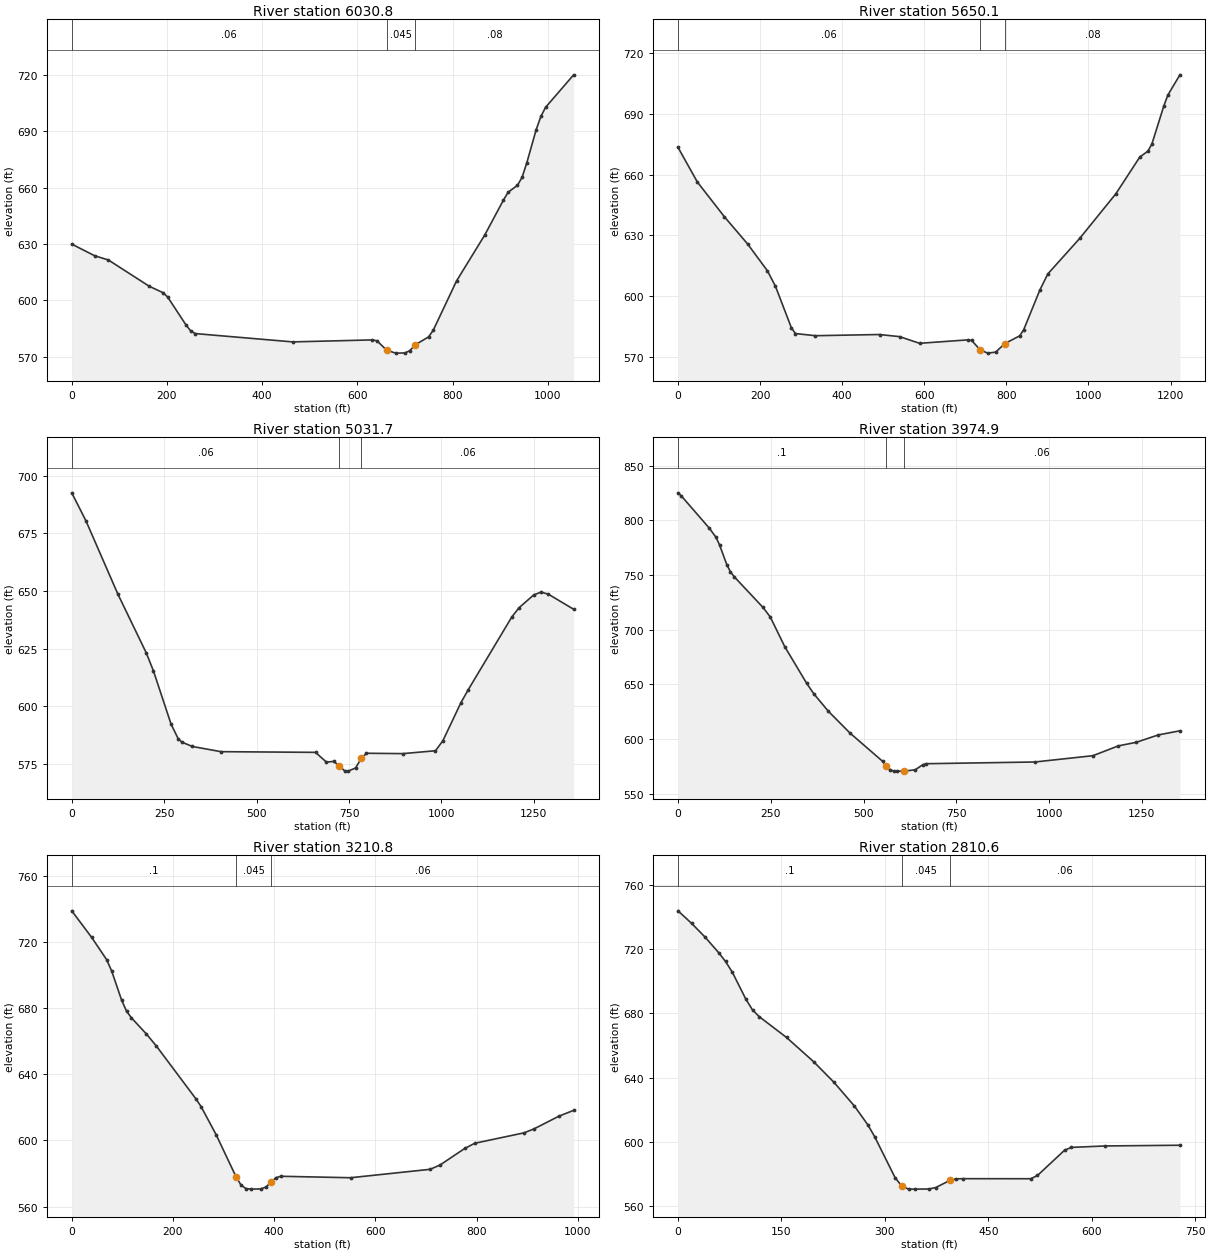
Type RM Length L Ch R = 1 ,6030.8  ,380.1,380.6,381.2
XS GIS Cut Line= 3
     1712844.427      593008.808     1712532.861       592911.73
     1711837.818      592695.168
#Sta/Elev= 30
       0  629.97      48  623.78    76.8  621.54   163.2  607.48     192  604.11
   201.6  601.77     240  586.97   249.6   583.9   259.2   582.4   464.1  577.97
   631.3  579.03   641.2  578.56   661.6  573.54   680.5     572   700.2   572.1
     710  573.31   721.6  576.43   749.4  580.61   759.2   584.1   808.4  610.43
   867.4  634.74   906.8  653.37   916.6  657.52   936.3  661.22   946.1  665.56
     956  673.29   975.6  690.83   985.5  697.85   995.3  702.69  1054.3  719.97
#Mann= 3 , 0 , 0
       0     .06       0   661.6    .045       0   721.6     .08       0
Bank Sta=661.6,721.6
XS Rating Curve= 0 ,0
Exp/Cntr=0.3,0.1

Type RM Length L Ch R = 1 ,5650.1  ,618.5,618.4,618.3
XS GIS Cut Line= 3
     1713065.394      592691.195     1712886.055      592632.913
       1711902.4      592313.245
#Sta/Elev= 30
       0  673.39    47.1  656.34   113.1  639.19   169.7  625.77   217.8  612.59
   237.4  604.95   276.4   584.4   286.2  581.64   334.9  580.59     491  581.17
   539.8  580.13   588.6  576.84   705.7  578.53   715.5  578.25   736.1  573.62
   754.5     572     774  572.49   796.1  576.69   832.6  580.53   842.3  583.55
   881.4  602.98   900.9  611.01   978.9  628.58  1066.8  650.55  1125.3   668.7
  1144.8  671.52  1154.6  675.07  1183.8   693.9  1193.6  699.24  1222.9  709.17
#Mann= 3 , 0 , 0
       0     .06       0   736.1    .045       0   796.1     .08       0
Bank Sta=736.1,796.1
XS Rating Curve= 0 ,0
Exp/Cntr=0.3,0.1

Type RM Length L Ch R = 1 ,5031.7  ,1097.6,1056.9,1032
XS GIS Cut Line= 3
      1713326.25      592151.308     1712970.437      592035.676
     1712035.193      591731.741
#Sta/Elev= 30
       0   692.6    38.4  680.44   124.7  648.69   201.5  623.19   220.6  615.52
   268.6   592.3   287.8  585.98   297.4  584.52   326.2   582.6   403.6  580.35
   659.3  580.05   688.8  575.83   708.5  576.12   723.2   574.2     738  572.07
   747.8  571.91   767.5  573.28   783.2  577.44     797  579.66   895.3   579.5
   983.8  580.75  1003.5  585.02  1052.7  601.62  1072.3  607.19  1190.4  638.81
    1210   642.8  1249.4  648.31    1269  649.54  1288.7  648.68  1357.5   642.1
#Mann= 3 , 0 , 0
       0     .06       0   723.2    .045       0   783.2     .06       0
Bank Sta=723.2,783.2
XS Rating Curve= 0 ,0
Exp/Cntr=0.3,0.1

Type RM Length L Ch R = 1 ,3974.9  ,817.2,764.1,695.1
XS GIS Cut Line= 3
      1713323.81      590625.115     1713236.625      590695.249
       1712269.7      591473.069
#Sta/Elev= 30
       0  825.31     9.3  822.34    83.9  793.15   102.6  784.52   111.9  777.64
   131.4  759.69   141.2  753.05     151  748.69   229.2  720.38   248.7  711.66
   287.8  684.44   346.4  651.17   365.9  641.41     405  625.48   463.7  605.39
   551.6  579.54   561.5  575.51   571.1     572   580.9  570.62   590.7   570.6
   610.2   570.6   639.5  571.84   659.1  576.34   668.8  577.39     962  578.97
  1118.3  584.72  1186.7   593.7  1235.6  597.01  1294.2  603.71  1352.8  607.52
#Mann= 3 , 0 , 0
       0      .1       0   561.5    .045       0   610.2     .06       0
Bank Sta=561.5,610.2
XS Rating Curve= 0 ,0
Exp/Cntr=0.3,0.1

Type RM Length L Ch R = 1 ,3210.8  ,418.8,400.2,381.6
XS GIS Cut Line= 3
     1712048.874      590575.808     1712181.168      591291.687
     1712229.116      591551.152
#Sta/Elev= 30
       0  738.85    39.4  722.75    68.9  709.35    78.7  702.62    98.4  684.98
   108.2  678.21     118  674.13   147.6  664.37   167.2  657.12     246  624.93
   255.8  620.36   285.3  603.54   324.6  578.11   334.5  573.06   344.3  570.92
   354.2   570.6   373.8  570.73   383.7  571.84     394  574.89   403.4  577.49
   413.2  578.37   550.9  577.49   708.3  582.58     728  585.22   776.9  595.24
   796.4  598.32   894.1  604.65   913.7  607.05   962.5  614.66   991.9  618.24
#Mann= 3 , 0 , 0
       0      .1       0   324.6    .045       0     394     .06       0
Bank Sta=324.6,394
XS Rating Curve= 0 ,0
Exp/Cntr=0.3,0.1

Type RM Length L Ch R = 1 ,2810.6  ,400.8,400,399.2
XS GIS Cut Line= 2
     1711556.168      590808.504     1711964.014      591411.534
#Sta/Elev= 30
       0   743.7    19.7  735.91    39.4  727.28      59  717.66    68.9  712.21
    78.7  705.58    98.4  688.76   108.2  681.95     118  677.82   157.4  664.93
   196.8  649.83   226.3     637   255.8  622.31   275.5   610.5   285.3  603.16
   314.8  577.77   324.6  572.44   334.5  570.62   344.3   570.6     364  570.69
   373.8  571.57     394  575.97   403.4  576.99   413.2   577.1   511.6  577.07
   521.4  579.09   560.8  594.85   570.6  596.56   619.8  597.46     728   597.9
#Mann= 3 , 0 , 0
       0      .1       0   324.6    .045       0     394     .06       0
Bank Sta=324.6,394
XS Rating Curve= 0 ,0
Exp/Cntr=0.3,0.1

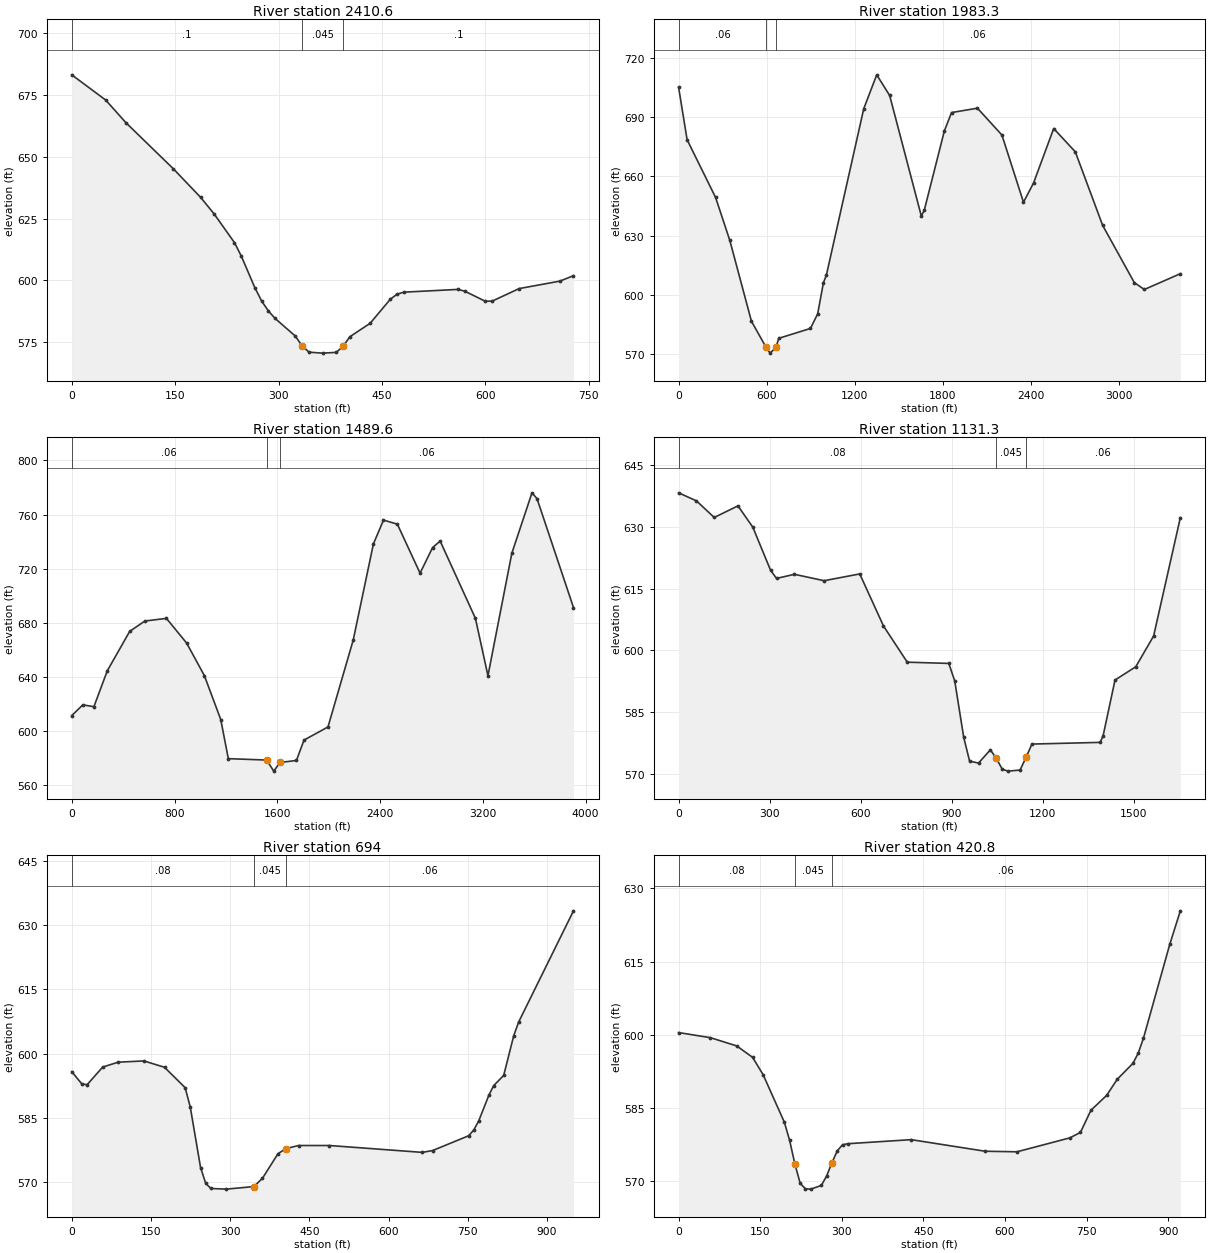
Type RM Length L Ch R = 1 ,2410.6  ,419.2,427.3,435.3
XS GIS Cut Line= 2
     1711220.178      591037.422     1711638.845      591632.991
#Sta/Elev= 30
       0  683.16    49.2  672.97    78.7  663.77   147.6   645.1   186.9  633.63
   206.6   626.9   236.1  615.29     246  609.85   265.6  597.11   275.5  591.69
   285.3  587.66   295.1  584.61   324.6  577.45     334   573.6   344.3  570.98
     364   570.6   383.7   570.9     394  573.44   403.4  577.21   432.9  582.65
   462.4  592.45   472.2  594.47     482  595.26   560.8  596.38   570.6   595.6
   600.1  591.58     610  591.64   649.3  596.72   708.3  599.72     728  601.93
#Mann= 3 , 0 , 0
       0      .1       0     334    .045       0     394      .1       0
Bank Sta=334,394
XS Rating Curve= 0 ,0
Exp/Cntr=0.3,0.1

Type RM Length L Ch R = 1 ,1983.3  ,462.7,493.7,524.7
XS GIS Cut Line= 4
     1711027.745      590976.272     1710949.567      591306.217
     1711374.893      592222.371     1710865.351      594226.003
#Sta/Elev= 30
       0     705    58.1  678.45   251.9  649.29   348.9  627.56     496  586.74
   595.7  573.53   623.5   570.6   662.7   573.5   682.3  578.09     898  583.08
   947.1  590.47   986.3  606.22  1005.9  609.88  1260.9  694.17  1349.2  711.28
  1437.3  700.83  1652.9  639.89  1672.5   642.7  1809.7   682.9  1858.6   692.2
    2035  694.42  2201.6  680.86  2348.6  646.87  2417.2  656.61  2554.3  684.14
  2701.3  672.37  2887.5   635.2    3103  606.27  3171.6  602.77  3416.6  610.74
#Mann= 3 , 0 , 0
       0     .06       0   595.7    .045       0   662.7     .06       0
Bank Sta=595.7,662.7
XS Rating Curve= 0 ,0
Exp/Cntr=0.3,0.1

Type RM Length L Ch R = 1 ,1489.6  ,387.3,358.3,320
XS GIS Cut Line= 6
     1711003.213      590240.552     1710958.328      590417.054
     1710918.585      590573.331     1710736.663      591288.695
     1710351.806       592802.04     1710040.487      594026.215
#Sta/Elev= 30
       0  611.62    86.3  619.54   172.5  618.18     277  644.76   451.6  673.86
   569.7  681.44     737   683.4   894.5  665.15  1032.3  641.16  1160.1  608.68
    1219  579.81    1517  578.78  1572.6   570.6  1621.6  576.99  1749.3  578.48
  1808.2  593.52  1994.8  603.22  2191.3  667.38  2348.4  738.34    2427  755.97
    2535  752.96  2711.6  716.78  2809.5  735.71  2868.2  740.48  3142.4  683.49
  3240.3  641.05  3426.4  731.56    3583   776.1  3622.2  771.83  3906.2  691.38
#Mann= 3 , 0 , 0
       0     .06       0    1517    .045       0  1621.6     .06       0
Bank Sta=1517,1621.6
XS Rating Curve= 0 ,0
Exp/Cntr=0.3,0.1

Type RM Length L Ch R = 1 ,1131.3  ,427.3,437.3,456.5
XS GIS Cut Line= 3
     1710057.234      590667.147      1710246.72      591547.814
     1710405.209      592284.418
#Sta/Elev= 30
       0  638.27    58.8  636.32   117.5  632.28   195.8   635.1   244.8   629.9
   303.5  619.41   323.1  617.46   381.9  618.46   479.8   616.9   597.3  618.55
   675.6  605.89     754  597.09     891  596.79   910.6  592.49     940  578.85
   959.5  573.03   988.9  572.56    1028  575.78  1047.6   573.7  1067.2  571.06
  1086.2   570.6  1125.9  570.86  1146.2  574.04    1165  577.18  1390.1  577.59
  1399.9  579.26    1439  592.75  1507.5  595.99  1566.2  603.45  1654.3  632.23
#Mann= 3 , 0 , 0
       0     .08       0  1047.6    .045       0  1146.2     .06       0
Bank Sta=1047.6,1146.2
XS Rating Curve= 0 ,0
Exp/Cntr=0.3,0.1

Type RM Length L Ch R = 1 ,694     ,268.2,273.3,278.3
XS GIS Cut Line= 3
     1709830.995      591449.604     1709965.088      592199.128
     1709998.351      592385.053
#Sta/Elev= 30
       0  595.78    19.5  592.86    29.3  592.77    58.6  596.85    87.9  597.99
   136.7  598.28   175.7   596.8   214.8  592.04   224.5  587.51     244  573.41
   253.8  569.72   263.6  568.54   292.9  568.39   345.1  568.99   361.2  570.92
   390.5  576.63   405.1  577.82   429.5  578.56   488.1  578.56   663.8  576.96
   683.3  577.38   751.7  580.83   761.4  582.17   770.9  584.32   789.8  590.23
   799.2  592.54   818.1   594.9     837  604.11   846.4  607.35   950.3  633.28
#Mann= 3 , 0 , 0
       0     .08       0   345.1    .045       0   405.1     .06       0
Bank Sta=345.1,405.1
XS Rating Curve= 0 ,0
Exp/Cntr=0.3,0.1

Type RM Length L Ch R = 1 ,420.8   ,431.2,420.8,416.4
XS GIS Cut Line= 3
     1709622.433       591511.61     1709680.536      592247.938
     1709694.973      592430.898
#Sta/Elev= 30
       0  600.42    58.3  599.38   106.9  597.68   136.1  595.33   155.5  591.75
   194.4  582.03   204.1  578.29   213.8  573.42   223.5  569.49   233.2  568.35
     243   568.3   262.4  569.06   272.1     571   281.8   573.7   291.6  576.15
   301.3   577.4     311  577.62   427.6  578.45   563.7  576.07     622  575.96
   719.2  578.82   738.6  579.94   757.9  584.48   786.9  587.55   806.2  590.84
   835.2  594.12   844.9  596.22   854.5  599.29   902.8  618.53   922.2   625.4
#Mann= 3 , 0 , 0
       0     .08       0   213.8    .045       0   281.8     .06       0
Bank Sta=213.8,281.8
XS Rating Curve= 0 ,0
Exp/Cntr=0.3,0.1

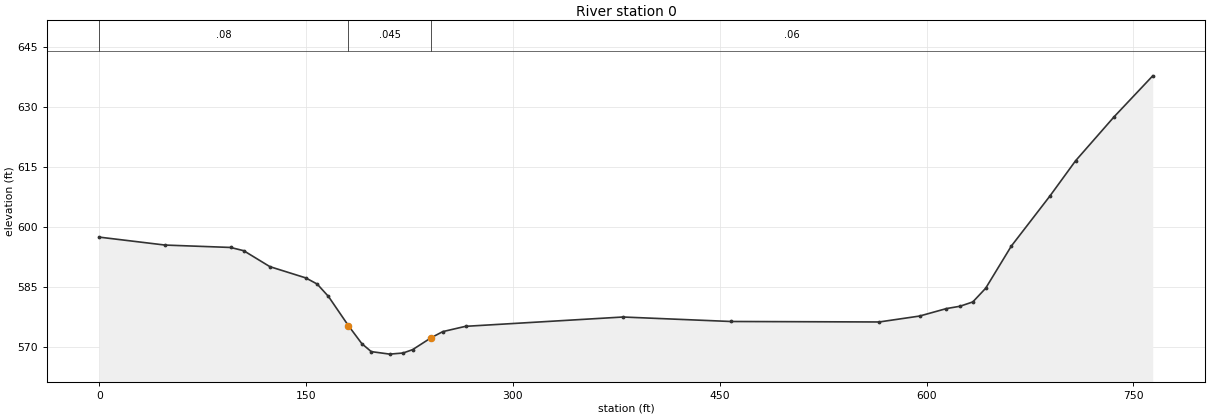
Type RM Length L Ch R = 1 ,0       ,1.7,0,0
XS GIS Cut Line= 6
     1709174.216      591654.159     1709238.506      591854.759
     1709247.723      591883.523     1709244.733      591924.615
      1709219.89      592265.861      1709209.74      592405.272
#Sta/Elev= 30
       0  597.57    47.6  595.59    95.2  594.99   104.7  594.18   123.7  590.19
   149.7  587.38     158  585.84   166.2  582.73   180.6  575.46   190.4  570.93
   197.2  568.95   210.6  568.32   220.3   568.6   227.2  569.44   240.6  572.41
   249.1  573.95   265.6  575.27   379.8   577.6     458  576.48   565.6  576.36
   594.9  577.84   614.4  579.71   624.2  580.29   633.5  581.37   642.8  584.78
   661.4  595.32   689.4  607.84     708  616.65     736  627.67     764   637.9
#Mann= 3 , 0 , 0
       0     .08       0   180.6    .045       0   240.6     .06       0
Bank Sta=180.6,240.6
XS Rating Curve= 0 ,0
Exp/Cntr=0.3,0.1

Chan Stop Cuts=-1
Use User Specified Reach Order=0
Composite Channel Slope=5